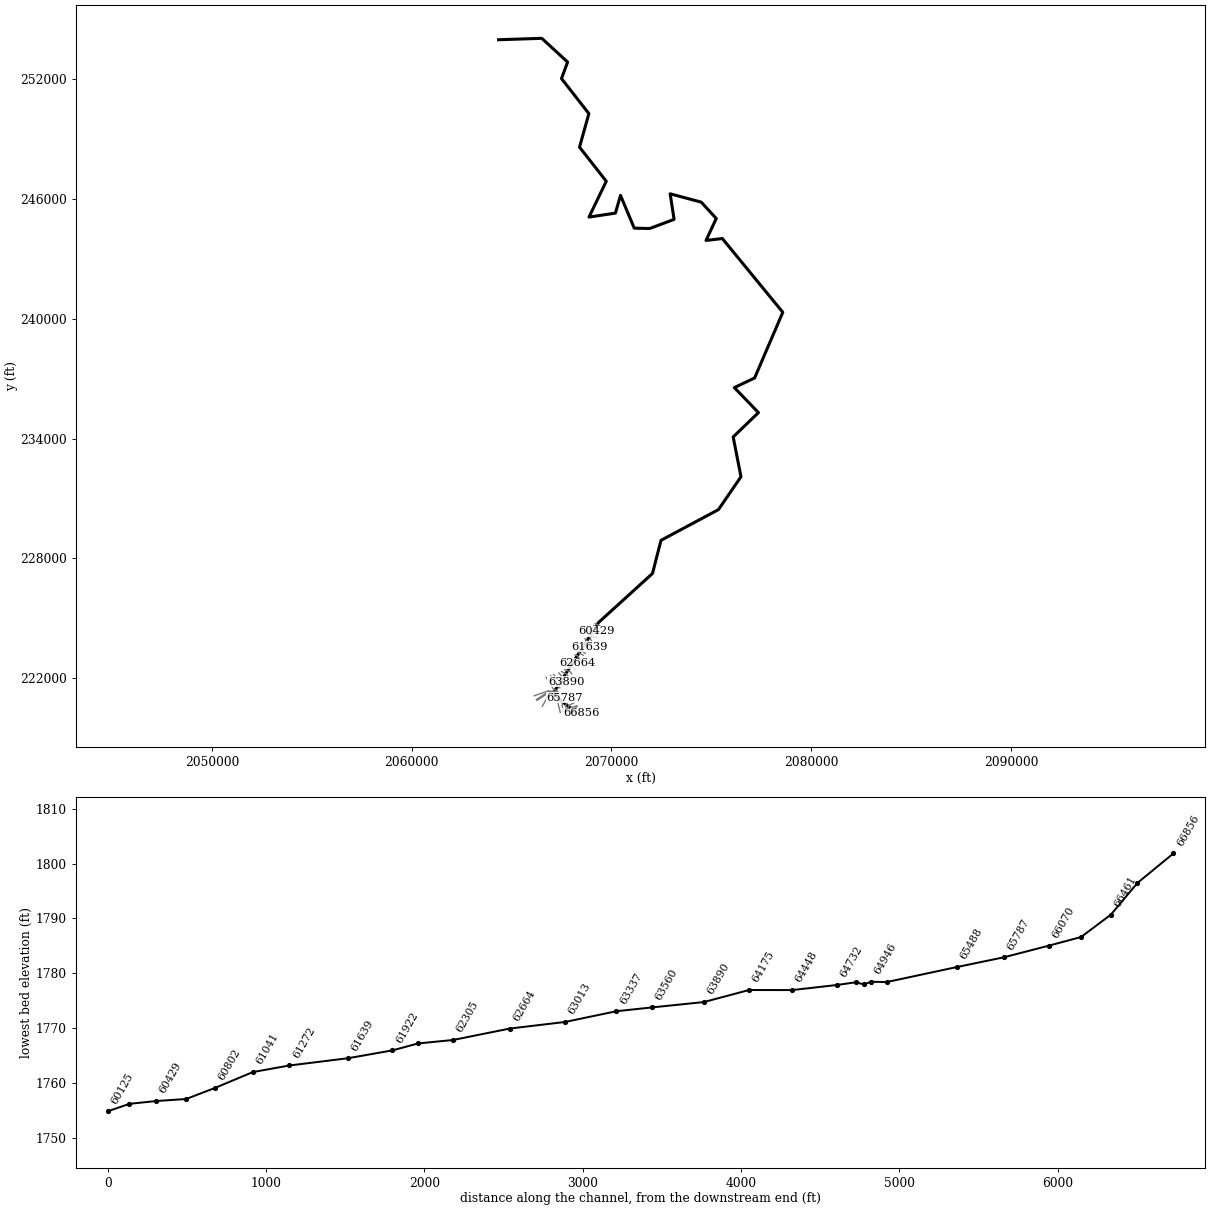
--- WOLFCK.prj (project) ---

Proj Title=WOLFCK
Current Plan=p01
Default Exp/Contr=0,0
English Units
Geom File=g01
Flow File=f01
Plan File=p01
Background Map Layer=Inundation Boundary (01pct Value_0)
BEGIN DESCRIPTION:
Stream Name: Wolf Creek
Flood Zone: Approximate
Monroe County, West Virginia
HEC-RAS Version: 5.0.7
Vertical Datum: NAVD88
Projection: NAD 1983 StatePlane West Virginia S FIPS 4702 (US Feet)
LiDAR: 2016, 1-meter
Land Use: 2016 NLCD
Hydrologic Method:
SIR2010-5033 regression equations
General Notes- Stream is in the Karst.Profile shows a depression at cross section 49586,49900 but no pond exists , this depression is due to the karst in the area.
For this hydrologic study, all flows were assumed to occur on the surface without any storage. Disconnects in the
30-meter hydrologic DEM were hydroconditioned using LiDAR, imagery, and dye tracer data (WVDEP, 2013).
END DESCRIPTION:
DSS File=dss
DSS Export Rating Curves= 0
DSS Export Rating Curve Sorted= 0
DSS Export Volume Flow Curves= 0
DXF OffsetX= 0
DXF OffsetY= 0
DXF ScaleX= 0
DXF ScaleY= 0

--- WOLFCK.p01 (plan) ---

Plan Title=Floodplain
Program Version=5.07
Short Identifier=Floodplain
Geom File=g01
Flow File=f01
Subcritical Flow
K Sum by GR= 0
Std Step Tol= 0.01
Critical Tol= 0.01
Num of Std Step Trials= 20
Max Error Tol= 0.3
Flow Tol Ratio= 0.001
Split Flow NTrial= 30
Split Flow Tol= 0.02
Split Flow Ratio= 0.02
Log Output Level= 0
Friction Slope Method= 1
Unsteady Friction Slope Method= 2
Unsteady Bridges Friction Slope Method= 1
Parabolic Critical Depth
Global Vel Dist= 0 , 0 , 0
Global Log Level= 0
CheckData=True
Encroach Param=-1 ,0,0, 0
Computation Interval=0.1SEC
Output Interval=1MIN
Instantaneous Interval=Max Profile
Mapping Interval=1HOUR
Computation Time Step Use Courant=        0
Computation Time Step Use Time Series=    0
Computation Time Step Count To Double=0
Computation Time Step Max Doubling=0
Computation Time Step Max Halving=0
Computation Time Step Residence Courant=0
Run HTab= 0
Run UNet= 0
Run Sediment= 0
Run PostProcess= 0
Run WQNet= 0
Run RASMapper=-1
UNET Theta= 0
UNET Theta Warmup= 0
UNET ZTol= 0
UNET ZSATol= 0
UNET MxIter= 0
UNET Max Iter WO Improvement= 0
UNET MaxInSteps= 0
UNET DtIC= 0
UNET DtMin= 0
UNET MaxCRTS= 0
UNET WFStab= 0
UNET SFStab= 0
UNET WFX= 1
UNET SFX= 1
UNET 1D Methodology=Finite Difference
UNET DSS MLevel= 1
UNET Pardiso=0
UNET DZMax Abort= 0
UNET Use Existing IB Tables= 0
UNET Froude Reduction=False
UNET Froude Limit= 0
UNET Froude Power= 0
UNET D1 Cores= 0
UNET D2 Coriolis=0
UNET D2 Cores= 0
UNET D2 Theta= 1
UNET D2 Theta Warmup= 1
UNET D2 Z Tol= 0.01
UNET D2 Volume Tol= 0.01
UNET D2 Max Iterations= 20
UNET D2 Equation= 0
UNET D2 RampUpFraction=0.1
UNET D2 TimeSlices= 1
UNET D2 BCVolumeCheck=0
UNET D1D2 MaxIter= 0
UNET D1D2 ZTol=0.01
UNET D1D2 QTol=0.1
UNET D1D2 MinQTol=1
DSS File=dss
Write IC File= 0
Write IC File at Fixed DateTime=0
Write IC File at Sim End=0
Echo Input=False
Echo Parameters=False
Echo Output=False
Write Detailed= 0
HDF Write Warmup=0
HDF Write Time Slices=0
HDF Flush=0
HDF Face Node Velocities=0
HDF Compression= 1
HDF Chunk Size= 1
HDF Spatial Parts= 1
HDF Use Max Rows=0
HDF Fixed Rows= 1
Calibration Method= 0
Calibration Iterations= 20
Calibration Max Change=0.05
Calibration Tolerance=0.2
Calibration Maximum=1.5
Calibration Minimum=0.5
Calibration Optimization Method= 1
WQ AD Non Conservative
WQ ULTIMATE=-1
WQ Max Comp Step=1HOUR
WQ Output Interval=15MIN
WQ Output Selected Increments= 0
WQ Output face flow=0
WQ Output face velocity=0
WQ Output face area=0
WQ Output face dispersion=0
WQ Output cell volume=0
WQ Output cell surface area=0
WQ Output cell continuity=0
WQ Output cumulative cell continuity=0
WQ Output face conc=0
WQ Output face dconc_dx=0
WQ Output face courant=0
WQ Output face peclet=0
WQ Output face adv mass=0
WQ Output face disp mass=0
WQ Output cell mass=0
WQ Output cell source sink temp=0
WQ Output nsm pathways=0
WQ Output nsm derived pathways=0
WQ Output MaxMinRange=-1
WQ Daily Max Min Mean=-1
WQ Daily Range=0
WQ Daily Time=0
WQ Create Restart=0
WQ Fixed Restart=0
WQ System Summary=0
WQ Write To DSS=0
WQ Use Fixed Temperature=0
Sorting and Armoring Iterations= 10
XS Update Threshold= 0.02
Bed Roughness Predictor= 0
Hydraulics Update Threshold= 0.02
Energy Slope Method= 1
Volume Change Method= 1
Sediment Retention Method= 0
XS Weighting Method= 0
Number of US Weighted Cross Sections= 1
Number of DS Weighted Cross Sections= 1
Upstream XS Weight=0
Main XS Weight=1
Downstream XS Weight=0
Number of DS XS's Weighted with US Boundary= 1
Upstream Boundary Weight= 1
Weight of XSs Associated with US Boundary= 0
Number of US XS's Weighted with DS Boundary= 1
Downstream Boundary Weight= 0.5
Weight of XSs Associated with DS Boundary= 0.5
Percentile Method= 0
Sediment Output Level= 3
Mass or Volume Output= 0
Output Increment Type= 1
Profile and TS Output Increment= 1
XS Output Flag= 0
XS Output Increment= 10
Write Gradation File= 0
Read Gradation Hotstart= 0
Write HDF5 File= 1
Write Binary Output= 1
Write DSS Sediment File= 0
SV Curve= 0
Specific Gage Flag= 0

--- WOLFCK.f01 (steady flow) ---

Flow Title=Flow
Program Version=5.07
Number of Profiles= 6
Profile Names=01pct,10pct,04pct,02pct,0_2pct,01plus
River Rch & RM=WOLFCK,Main            ,66856
     776     415     549     659    1080    1150
River Rch & RM=WOLFCK,Main            ,64849
    1070     579     761     910    1480    1580
River Rch & RM=WOLFCK,Main            ,64732
    1180     640     840    1000    1620    1740
River Rch & RM=WOLFCK,Main            ,57787
    1340     732     958    1140    1840    1980
River Rch & RM=WOLFCK,Main            ,57343
    1420     776    1010    1210    1950    2100
River Rch & RM=WOLFCK,Main            ,53357
    1560     854    1120    1330    2130    2300
River Rch & RM=WOLFCK,Main            ,52612
    1630     897    1170    1390    2230    2410
River Rch & RM=WOLFCK,Main            ,48013
    2010    1120    1450    1720    2750    2980
River Rch & RM=WOLFCK,Main            ,47783
    2210    1230    1600    1900    3020    3270
River Rch & RM=WOLFCK,Main            ,40534
    2460    1380    1780    2110    3350    3640
River Rch & RM=WOLFCK,Main            ,40159
    2710    1520    1960    2320    3670    4000
River Rch & RM=WOLFCK,Main            ,38034
    2920    1640    2120    2510    3950    4320
River Rch & RM=WOLFCK,Main            ,31840
    3810    2170    2780    3280    5140    5640
River Rch & RM=WOLFCK,Main            ,31458
    3830    2180    2800    3300    5170    5670
River Rch & RM=WOLFCK,Main            ,29257
    4740    2720    3480    4090    6370    7020
River Rch & RM=WOLFCK,Main            ,28891
    4990    2870    3660    4300    6690    7380
River Rch & RM=WOLFCK,Main            ,16585
    5500    3170    4040    4750    7360    8130
Boundary for River Rch & Prof#=WOLFCK,Main            , 1
Up Type= 0
Dn Type= 3
Dn Slope=0.017
Boundary for River Rch & Prof#=WOLFCK,Main            , 2
Up Type= 0
Dn Type= 3
Dn Slope=0.017
Boundary for River Rch & Prof#=WOLFCK,Main            , 3
Up Type= 0
Dn Type= 3
Dn Slope=0.017
Boundary for River Rch & Prof#=WOLFCK,Main            , 4
Up Type= 0
Dn Type= 3
Dn Slope=0.017
Boundary for River Rch & Prof#=WOLFCK,Main            , 5
Up Type= 0
Dn Type= 3
Dn Slope=0.017
Boundary for River Rch & Prof#=WOLFCK,Main            , 6
Up Type= 0
Dn Type= 3
Dn Slope=0.017
DSS Import GetInterval= 0
DSS Import GetPeak= 0
DSS Import FillOption= 0

--- WOLFCK.g01 (geometry) ---

Geom Title=Geometry
Program Version=5.07

River Reach=WOLFCK          ,Main
Reach XY= 30
     2068227.236220302.0390000052067046.61400002221187.481999993
2069359.83200002224793.9039999992072054.27599999227244.425000012
2072480.49200004228905.0160000182075356.36000001230443.209999993
2076483.61700004232090.2060000152076092.99200004234083.479000017
2077358.18300003235302.0119999952076152.66999999 236555.26700002
2077167.21000004237038.1229999962078576.71599999 240328.05400002
2075550.45700002 244021.630000012074733.40000001243926.144000009
2075246.63700002245025.319000021     2074494.685245844.547000006
2072938.69500002246262.2989999952073135.09200004244980.832000017
     2071911.134244522.9319999962071140.60500002244542.724000007
2070453.97299999246183.349000007     2070198.764245294.460000008
2068876.28200004245097.1220000092069741.73300004246890.308000013
2068402.32300001 248599.336000012068871.07300004250279.023000002
2067500.63100004252033.5800000132067805.53500003252861.488000005
     2066514.303254049.6390000132064348.92862818253979.915987745

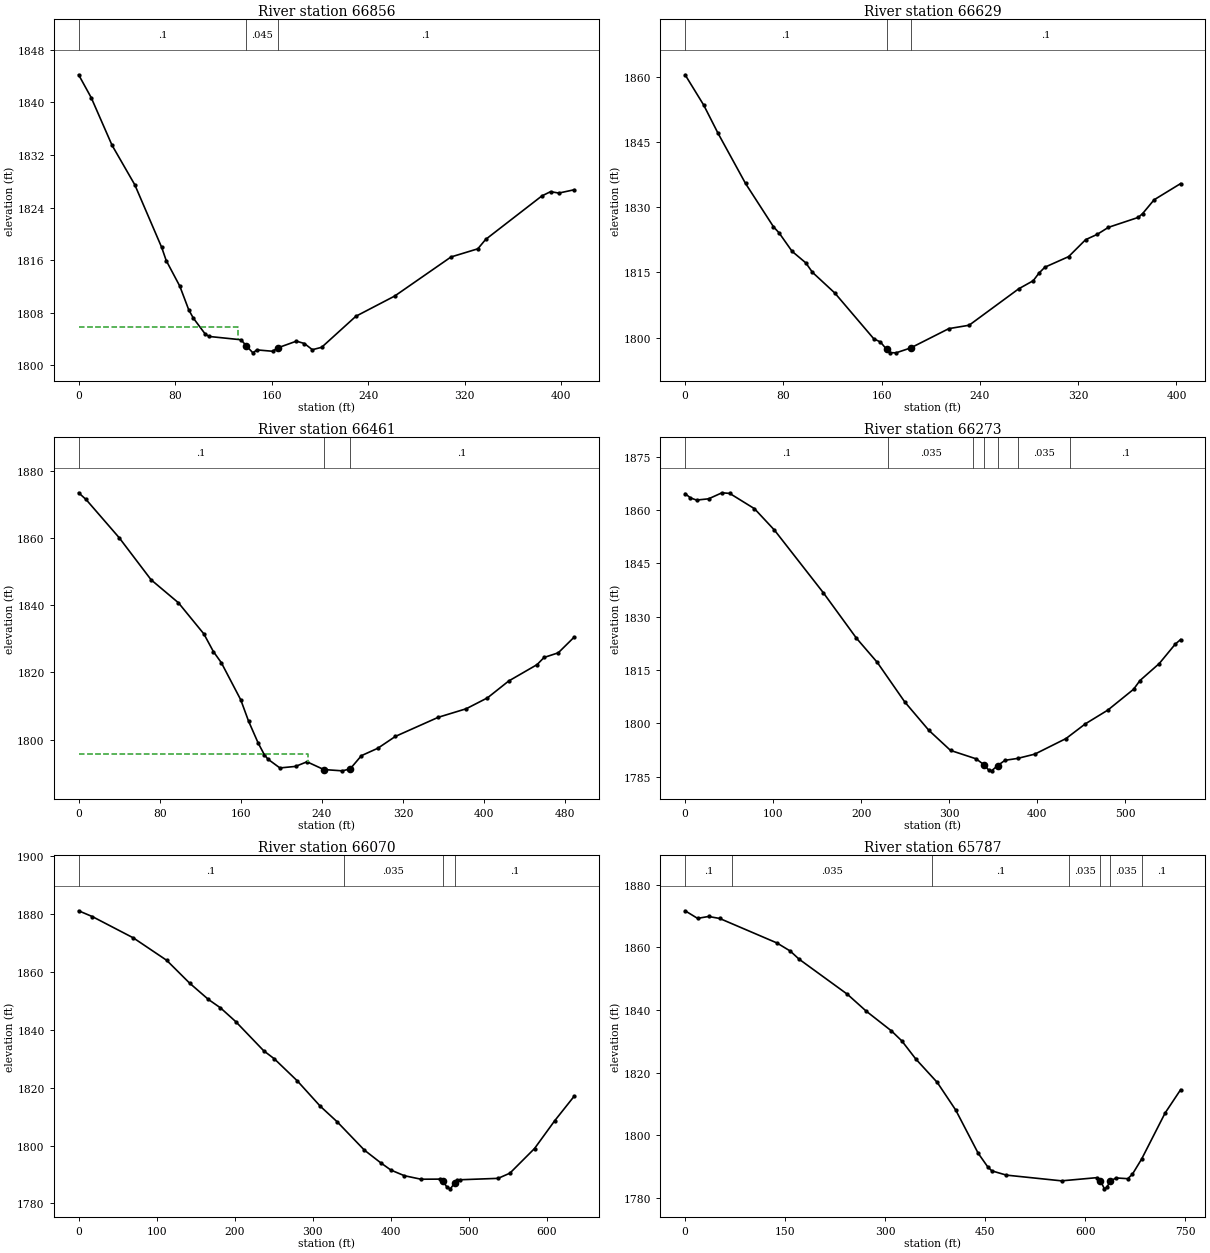
Type RM Length L Ch R = 1 ,66856   ,217.1,227.5,241.8
XS GIS Cut Line= 4
     2068095.921      220259.277     2068180.556      220305.935
      2068314.02      220310.275     2068479.312      220237.141
#Sta/Elev= 30
       0 1844.21    10.4 1840.74    27.7 1833.48    46.6 1827.45    68.9 1817.91
    72.6 1815.93    83.9 1812.02    91.3 1808.42    95.1 1807.16   105.1  1804.7
   108.4 1804.36   134.7 1803.86     1391802.939   144.5 1801.87   147.8 1802.32
   160.8 1802.11     1651802.619   180.6 1803.65   187.2 1803.29   193.8 1802.35
   201.5 1802.71   229.9 1807.44   262.1 1810.52   308.8 1816.47     331 1817.71
   337.5 1819.14   384.1 1825.76   391.3 1826.41   398.2  1826.2   410.9  1826.7
#Mann= 3 ,-1 , 0
       0      .1       0     139    .045       0     165      .1       0
#XS Ineff= 2 , 0
          132.45 1805.87
Permanent Ineff=
       F       F
Bank Sta=139,165
XS Rating Curve= 0 ,0
Exp/Cntr=0.3,0.1

Type RM Length L Ch R = 1 ,66629   ,170.4,167.5,149.2
XS GIS Cut Line= 2
     2067995.966       220309.29     2068287.632      220587.935
#Sta/Elev= 30
       0 1860.56    15.1  1853.6    26.9 1847.03    49.2 1835.51    71.9 1825.55
    76.5 1824.13    87.1 1819.87    98.2 1817.23   103.7 1815.03   121.9 1810.26
   153.6 1799.72     159 1798.98     1641797.306   167.2 1796.52   171.7 1796.48
   183.61797.608   214.7 1802.06   231.2 1802.84   271.6 1811.24   283.4  1813.1
   288.1 1814.86   292.9 1816.22   312.2 1818.65   326.1 1822.57   335.4 1823.77
   344.6  1825.4   368.9 1827.69   372.5 1828.59   381.8 1831.75   403.4 1835.49
#Mann= 3 ,-1 , 0
       0      .1       0     164    .045       0   183.6      .1       0
Bank Sta=164,183.6
XS Rating Curve= 0 ,0
Exp/Cntr=0.3,0.1

Type RM Length L Ch R = 1 ,66461   ,188.6,188.6,192.9
XS GIS Cut Line= 3
      2067873.57      220358.769     2067969.185      220515.136
     2068256.382      220619.185
#Sta/Elev= 30
       0  1873.4     7.3 1871.41      40 1860.03    71.5 1847.51    98.4 1840.69
   123.5 1831.43   132.9 1826.17   140.7 1822.88   159.9 1811.81   167.6 1805.47
   177.1 1798.94   183.3 1795.41   186.8 1794.15   198.5 1791.56   213.9 1792.02
   225.2 1793.39   241.81791.082   260.1  1790.7   267.81791.286   278.9 1795.22
     295 1797.41   312.4 1800.94   354.7 1806.63   382.2 1809.16   403.2 1812.41
   424.1 1817.41   452.1 1822.29     459 1824.42     473  1825.8   488.7 1830.47
#Mann= 3 ,-1 , 0
       0      .1       0   241.8    .045       0   267.8      .1       0
#XS Ineff= 2 , 0
          226.12 1795.81
Permanent Ineff=
       F       F
Bank Sta=241.8,267.8
XS Rating Curve= 0 ,0
Exp/Cntr=0.3,0.1

Type RM Length L Ch R = 1 ,66273   ,189.8,203,204.4
XS GIS Cut Line= 3
     2067785.028      220361.373     2067868.273      220636.664
     2068115.757      220757.206
#Sta/Elev= 30
       0 1864.65     6.1 1863.44      13 1862.83    26.7 1863.18    41.9 1864.88
    50.7  1864.7    78.8  1860.4   101.5 1854.37     157 1836.75   194.6 1823.96
   218.3 1817.14   249.5 1806.01   276.9 1798.01   301.5 1792.36   330.6 1789.99
     3401788.231   345.2 1786.71   348.1 1786.61     3551788.077   363.4 1789.58
   377.6  1790.1   397.2 1791.31   432.7  1795.7   454.6 1799.83   480.2 1803.71
   509.4 1809.56   516.7 1812.03   538.6 1816.81   556.8 1822.28   562.9 1823.57
#Mann= 7 ,-1 , 0
       0      .1       0     230    .035       0   327.6      .1       0
     340    .045       0     355      .1       0   377.6    .035       0
   437.6      .1       0
Bank Sta=340,355
XS Rating Curve= 0 ,0
Exp/Cntr=0.3,0.1

Type RM Length L Ch R = 1 ,66070   ,271.9,283.3,281.1
XS GIS Cut Line= 3
     2067701.695      220343.144     2067713.401      220662.405
     2067912.761      220906.846
#Sta/Elev= 30
       0 1881.05    17.6 1879.04    70.1 1871.69   112.8 1863.95   142.3 1856.04
   166.3 1850.43   181.7 1847.54   201.4 1842.75   237.2 1832.69   250.7 1829.94
   280.2 1822.31   309.5 1813.59   331.2  1808.2   366.1 1798.41   387.1 1794.02
   400.1 1791.52   417.4 1789.57   438.7 1788.36   463.6  1788.4     4671787.686
   472.1 1785.51   476.3 1785.04     4821787.167   484.8 1787.98     489 1788.18
   537.4 1788.66   552.5 1790.44   584.1 1798.96     610 1808.57   634.9 1817.02
#Mann= 4 ,-1 , 0
       0      .1       0  339.48    .035       0     467    .045       0
     482      .1       0
Bank Sta=467,482
XS Rating Curve= 0 ,0
Exp/Cntr=0.3,0.1

Type RM Length L Ch R = 1 ,65787   ,298.9,298.8,293.8
XS GIS Cut Line= 3
     2067579.299       220309.29     2067531.191      220721.873
       2067645.4      221028.808
#Sta/Elev= 30
       0 1871.65    18.7 1869.23    35.2 1869.83    51.8  1869.2   137.6 1861.39
   157.5 1858.82     171 1856.19   243.3 1845.01   271.6 1839.61   309.4 1833.31
   324.9 1830.13   345.7 1824.39   378.1 1816.86   405.8 1808.03   439.4 1794.27
   453.6 1789.97   459.8 1788.66   481.6  1787.3   564.4 1785.47   617.8  1786.5
   622.61785.537   628.6 1782.92   632.1 1783.37   637.61785.372     646  1786.4
   663.6 1786.16   670.6 1787.59   684.4 1792.42   719.6 1807.11   742.9 1814.57
#Mann= 7 ,-1 , 0
       0      .1       0      70    .035       0     370      .1       0
  575.38    .035       0   622.6    .045       0   637.6    .035       0
  685.38      .1       0
Bank Sta=622.6,637.6
XS Rating Curve= 0 ,0
Exp/Cntr=0.3,0.1

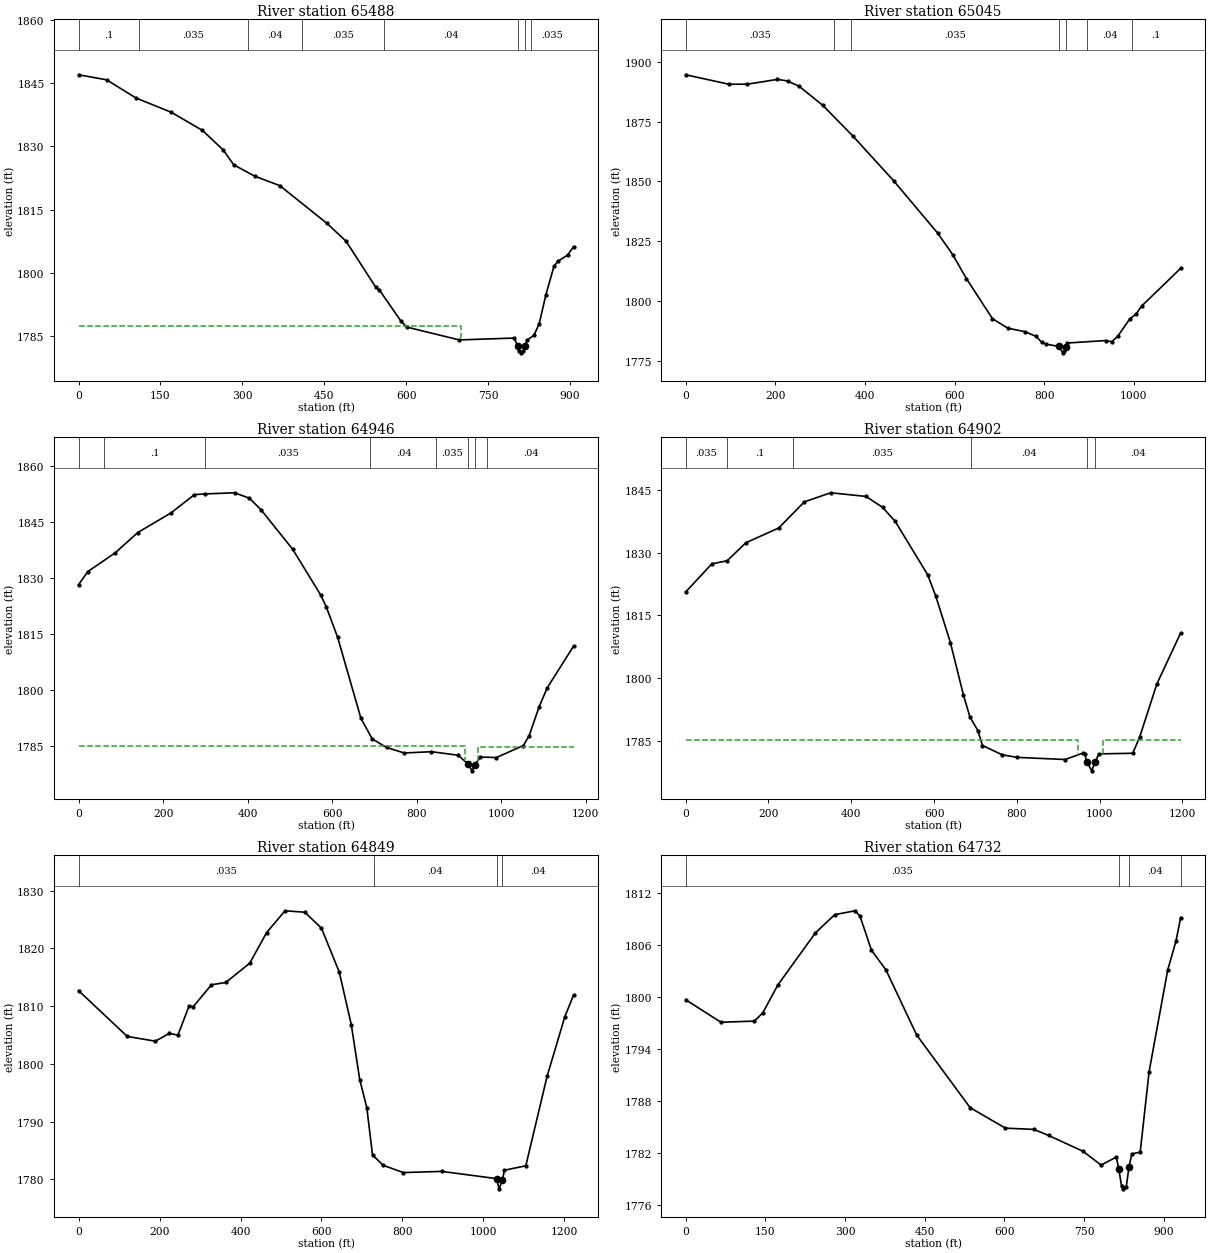
Type RM Length L Ch R = 1 ,65488   ,430.6,443,408.7
XS GIS Cut Line= 3
     2067438.674       220278.04     2067280.165      220928.113
     2067391.277      221138.183
#Sta/Elev= 30
       0 1846.98    51.3 1845.79   105.3 1841.47   169.5 1838.12   226.9  1833.8
   264.7 1829.21   284.3 1825.65   322.5 1822.98   368.7 1820.72   455.1 1811.78
     490 1807.56   544.3 1796.69   551.1 1796.01   590.5 1788.65   601.3 1787.23
   697.4 1784.19     798 1784.63  804.26 1782.83   806.6 1781.49   810.3 1781.13
   814.1  1781.5   817.8 1782.85   821.5 1784.13   834.4 1785.31   843.8 1788.03
   856.2 1794.94   870.8 1801.58   878.1 1802.83   895.7 1804.26   906.8 1806.26
#Mann= 8 ,-1 , 0
       0      .1       0     110    .035       0     310     .04       0
     410    .035       0     560     .04       0  804.26    .045       0
   817.8     .04       0  829.12    .035       0
#XS Ineff= 2 , 0
             700  1787.6
Permanent Ineff=
       F       F
Bank Sta=804.26,817.8
XS Rating Curve= 0 ,0
Exp/Cntr=0.3,0.1

Type RM Length L Ch R = 1 ,65045   ,105.4,98.6,83.8
XS GIS Cut Line= 3
     2066537.632      220585.331     2066827.468      221106.063
     2067316.624      221245.822
#Sta/Elev= 30
       0 1894.53    96.2 1890.59   137.3 1890.59   204.8 1892.61   227.3 1891.95
   253.6 1889.67   306.1 1881.73   373.4 1868.89   463.8 1850.32   562.3  1828.4
     596 1819.41   626.7 1809.33   684.7 1792.65   718.8  1788.7   756.4 1787.26
   781.3 1785.35   794.5 1782.85   804.1 1782.01   832.7 1781.08   841.7 1778.39
   845.1  1779.2   847.71780.917   851.9  1782.5   937.8 1783.52   951.1 1783.02
   964.4 1785.36   990.9  1792.5  1005.4 1794.67  1017.4 1797.89  1104.7 1813.69
#Mann= 7 ,-1 , 0
       0    .035       0     330      .1       0     370    .035       0
   832.7    .045       0   847.7    .035       0  895.96     .04       0
  995.96      .1       0
Bank Sta=832.7,847.7
XS Rating Curve= 0 ,0
Exp/Cntr=0.5,0.3

Type RM Length L Ch R = 1 ,64946   ,41.7,43.9,73.9
XS GIS Cut Line= 6
     2066274.611       220884.81     2066871.311      221281.629
     2067121.962      221246.907      2067168.62      221265.353
     2067188.152      221291.395     2067304.254      221267.523
#Sta/Elev= 30
       0 1828.22    21.7 1831.68      87 1836.74     140 1842.13   218.8 1847.38
   273.9 1852.26     300 1852.45   368.8 1852.75   403.9 1851.31   431.5 1848.22
   506.4 1837.66   573.4 1825.31   586.3 1822.14   612.8 1814.13   667.9 1792.47
   694.7 1786.97   728.7 1784.69   770.2 1783.22   834.7 1783.56   897.6 1782.63
   921.41780.282   930.7 1778.45   937.21780.033   950.6 1782.14   988.2    1782
  1052.4 1785.22    1066 1787.89  1089.5 1795.59  1108.8 1800.67  1170.9 1811.77
#Mann= 8 ,-1 , 0
       0    .035       0      60      .1       0     300    .035       0
     690     .04       0   846.6    .035       0   921.4    .045       0
   937.2    .035       0   966.6     .04       0
#XS Ineff= 2 , 0
          914.08  1785.1  944.25         1784.94
Permanent Ineff=
       F       F
Bank Sta=921.4,937.2
XS Rating Curve= 0 ,0
Exp/Cntr=0.5,0.3

Type RM Length L Ch R = 1 ,64902   ,53.7,53.1,35.7
XS GIS Cut Line= 6
     2066243.361      220929.081     2066847.528      221324.915
     2067096.355      221290.093     2067143.013      221308.539
     2067159.289       221328.07     2067299.263      221284.667
#Sta/Elev= 30
       0 1820.61    62.9 1827.29   100.3 1828.05   145.3 1832.34   224.7 1835.85
   286.5 1842.08   350.2 1844.25   435.6 1843.38   475.8 1840.76   506.2 1837.42
   584.6  1824.7   604.2 1819.58   639.4 1808.54   670.9 1796.04   686.7 1790.77
   705.7 1787.57   716.9    1784     765 1781.77   801.4 1781.17   916.4 1780.66
   960.5 1782.21   963.8 1782.01   968.8 1780.16   980.8 1777.96   988.9 1780.11
   998.4    1782  1079.9 1782.15  1096.8 1786.04    1138 1798.63  1195.7 1810.84
#Mann= 6 ,-1 , 0
       0    .035       0     100      .1       0     260    .035       0
     690     .04       0   968.8    .045       0   988.9     .04       0
#XS Ineff= 2 , 0
          947.61 1785.42 1007.22         1785.42
Permanent Ineff=
       F       F
Bank Sta=968.8,988.9
XS Rating Curve= 0 ,0
Exp/Cntr=0.5,0.3

Type RM Length L Ch R = 1 ,64849   ,120.6,117.6,94
XS GIS Cut Line= 4
     2066133.826      221117.349     2066820.313      221361.924
     2067179.471      221329.372     2067306.424      221288.139
#Sta/Elev= 30
       0 1812.68   120.2 1804.75   189.6 1803.93   224.4 1805.28   245.3 1804.98
   273.2 1810.06   283.6 1809.93   328.2  1813.7   363.7  1814.1   422.9 1817.45
   464.7 1822.75     510 1826.52   558.8 1826.27     600 1823.51   644.1 1815.88
   673.7  1806.8   694.6 1797.27     712 1792.44   726.2 1784.22   752.4 1782.43
   802.3 1781.17   897.4 1781.37  1032.5 1780.12    1039 1778.35    1047 1779.88
  1052.2 1781.58  1104.9 1782.34  1157.4 1797.82  1201.3 1808.16  1222.9 1811.93
#Mann= 4 ,-1 , 0
       0    .035       0  728.75     .04       0  1032.5    .045       0
    1047     .04       0
Bank Sta=1032.5,1047
XS Rating Curve= 0 ,0
Exp/Cntr=0.3,0.1

Type RM Length L Ch R = 1 ,64732   ,285,283.8,277.7
XS GIS Cut Line= 3
     2066727.576      222041.829     2067083.985      221471.516
     2067310.764      221345.648
#Sta/Elev= 30
       0 1799.71    66.3 1797.11   129.3 1797.24   145.2  1798.2   173.5 1801.42
   244.3 1807.44   280.6 1809.54   318.8 1809.99   328.2 1809.36   349.8 1805.43
   376.9 1803.17   434.9 1795.63   535.5 1787.24     602 1784.87   655.4 1784.73
   683.2 1784.03   748.3 1782.19   782.1  1780.6   810.7 1781.53   815.21780.196
   820.7 1778.15   823.1 1777.86   829.5  1778.1   834.61780.392     840  1781.9
   855.7  1782.1   872.5 1791.41   907.5 1803.14   923.3 1806.55   931.9 1809.21
#Mann= 4 ,-1 , 0
       0    .035       0   815.2    .045       0   834.6     .04       0
  931.89      .1       0
Bank Sta=815.2,834.6
XS Rating Curve= 0 ,0
Exp/Cntr=0.3,0.1

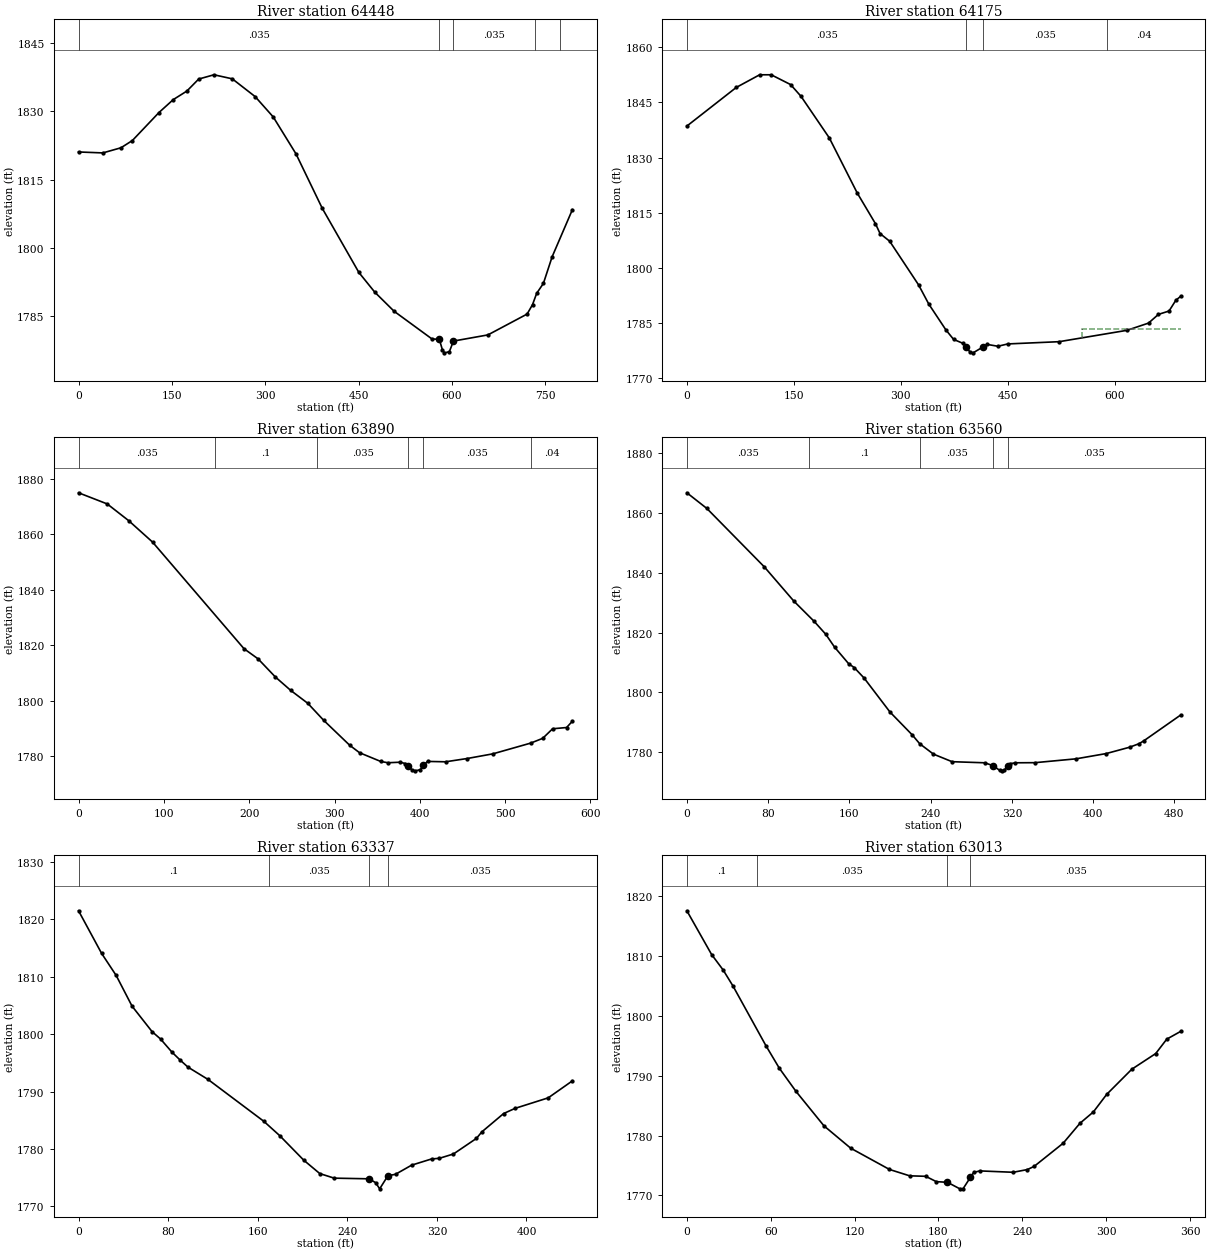
Type RM Length L Ch R = 1 ,64448   ,273.6,272.3,263.9
XS GIS Cut Line= 4
     2066958.639      222131.338     2067154.794      221729.503
     2067356.726      221588.857     2067423.178        221513.4
#Sta/Elev= 30
       0 1821.07      39 1820.86    68.2 1821.99    86.5 1823.58   129.3 1829.74
   152.2 1832.57   174.1 1834.45   193.1 1837.09   217.7 1838.03   247.1 1837.14
   283.9 1833.23   312.9 1828.77   349.4 1820.68   391.8 1808.67   450.6 1794.59
   476.1 1790.27   507.1 1786.08   568.1 1779.98   579.91779.899   584.9 1777.57
   588.1 1776.93     596 1777.17   602.61779.516     658 1780.87     721 1785.45
   729.7 1787.52   736.4 1790.01   747.2 1792.19   761.2 1798.03   793.8  1808.4
#Mann= 5 ,-1 , 0
       0    .035       0   579.9    .045       0   602.6    .035       0
  733.24     .04       0  773.24     .12       0
Bank Sta=579.9,602.6
XS Rating Curve= 0 ,0
Exp/Cntr=0.3,0.1

Type RM Length L Ch R = 1 ,64175   ,281.4,285.7,274.8
XS GIS Cut Line= 2
     2067107.945      222176.477     2067580.167      221669.533
#Sta/Elev= 30
       0 1838.56    69.3 1849.06   102.1  1852.5   118.3  1852.5   145.5 1849.84
   160.1 1846.65   199.8 1835.35     239 1820.37   264.6 1812.02     271 1809.35
   284.5 1807.27     325 1795.42   339.4 1790.18   363.5 1783.14   374.2 1780.59
   387.6  1779.5   392.1 1778.43   397.2 1777.16   401.5 1776.94     4151778.485
   421.3 1779.23   436.3 1778.73   450.3 1779.36   522.2 1779.97   617.4 1783.06
   647.6 1785.02   661.5 1787.39   676.4  1788.3     686 1791.24   692.8 1792.31
#Mann= 4 ,-1 , 0
       0    .035       0   392.1    .045       0     415    .035       0
     590     .04       0
#XS Ineff= 2 , 0
                          554.08         1783.46
Permanent Ineff=
       F       F
Bank Sta=392.1,415
XS Rating Curve= 0 ,0
Exp/Cntr=0.3,0.1

Type RM Length L Ch R = 1 ,63890   ,311.5,329.4,323.2
XS GIS Cut Line= 2
     2067364.889      222266.755     2067728.733      221816.568
#Sta/Elev= 30
       0 1875.02    33.6    1871    58.9 1864.93    86.7 1857.25   193.9 1818.79
   210.4 1815.13   230.7 1808.58   248.7 1803.74   268.7 1799.09   287.3 1792.96
   317.7 1783.99   329.3 1781.28   354.2 1778.12   362.6 1777.66   376.9 1777.85
     383 1777.38   385.91776.465   390.7 1775.13   394.7 1774.74   400.6 1775.16
   404.21776.688     409 1778.14   430.1    1778   455.4 1779.18   485.6 1780.87
     530 1784.75     544 1786.46   555.6 1789.91     572 1790.36   578.8 1792.65
#Mann= 6 ,-1 , 0
       0    .035       0     160      .1       0     280    .035       0
   385.9    .045       0   404.2    .035       0     530     .04       0
Bank Sta=385.9,404.2
XS Rating Curve= 0 ,0
Exp/Cntr=0.3,0.1

Type RM Length L Ch R = 1 ,63560   ,216.3,222.8,227.5
XS GIS Cut Line= 4
     2067500.306      222332.727     2067711.372      222231.065
     2067827.474      222107.367     2067893.664      222058.539
#Sta/Elev= 30
       0 1866.74    19.7 1861.49    76.2 1841.98   105.3 1830.52   125.4 1823.71
   136.7 1819.44   145.4 1815.13   159.3 1809.57   164.7 1808.31   174.5 1804.78
     200 1793.41   221.9 1785.77   229.2 1782.83   242.8 1779.34   261.1 1776.82
   293.2 1776.45   301.21775.528   307.8 1773.97   310.1 1773.76   312.5 1774.01
   316.21775.447   318.6 1776.17   323.4 1776.45   342.7 1776.49   383.2 1777.78
   412.9 1779.54   435.8 1781.65   445.2 1782.84   449.9 1783.81   486.2 1792.44
#Mann= 5 ,-1 , 0
       0    .035       0     120      .1       0     230    .035       0
   301.2    .045       0   316.2    .035       0
Bank Sta=301.2,316.2
XS Rating Curve= 0 ,0
Exp/Cntr=0.3,0.1

Type RM Length L Ch R = 1 ,63337   ,320.2,324.2,292.3
XS GIS Cut Line= 3
     2067649.611      222436.894     2067957.683      222305.935
     2068006.511      222211.534
#Sta/Elev= 30
       0 1821.48    20.6 1814.06    33.6 1810.22    47.8 1804.87    65.7 1800.43
    73.2 1799.16    83.5 1796.85    90.5 1795.53    97.7 1794.26   115.6 1792.12
   165.5 1784.82   179.7 1782.32   201.1 1778.06   215.4 1775.73   228.3 1774.93
   259.51774.815   265.3 1774.14   268.9 1773.07   276.21775.334   283.1 1775.61
   297.4 1777.19   315.2 1778.27   322.3 1778.39   334.8 1779.14   355.3 1781.85
   360.1 1782.98   379.6 1786.18   389.8 1787.08   419.4 1788.91     441 1791.87
#Mann= 4 ,-1 , 0
       0      .1       0     170    .035       0   259.5    .045       0
   276.2    .035       0
Bank Sta=259.5,276.2
XS Rating Curve= 0 ,0
Exp/Cntr=0.3,0.1

Type RM Length L Ch R = 1 ,63013   ,340.1,349.1,341.6
XS GIS Cut Line= 2
     2067858.942      222657.497     2068161.676      222475.205
#Sta/Elev= 30
       0 1817.46    17.7 1810.17    25.9 1807.61      33 1804.92    56.6 1794.96
    66.2  1791.2    78.1 1787.35    98.1 1781.61   117.2 1777.89     145 1774.34
   159.4 1773.28   170.9  1773.2   178.5 1772.31   186.51772.198   195.2 1771.13
   197.6 1771.11   202.91773.027   205.3 1773.85   209.6  1774.1   233.5 1773.87
   243.6 1774.32   248.5 1774.85   269.3 1778.72   281.3 1782.04   290.9 1783.93
   300.4 1786.85   318.4 1791.05   335.5 1793.66   343.4 1796.06   353.4 1797.36
#Mann= 4 ,-1 , 0
       0      .1       0      50    .035       0   186.5    .045       0
   202.9    .035       0
Bank Sta=186.5,202.9
XS Rating Curve= 0 ,0
Exp/Cntr=0.3,0.1

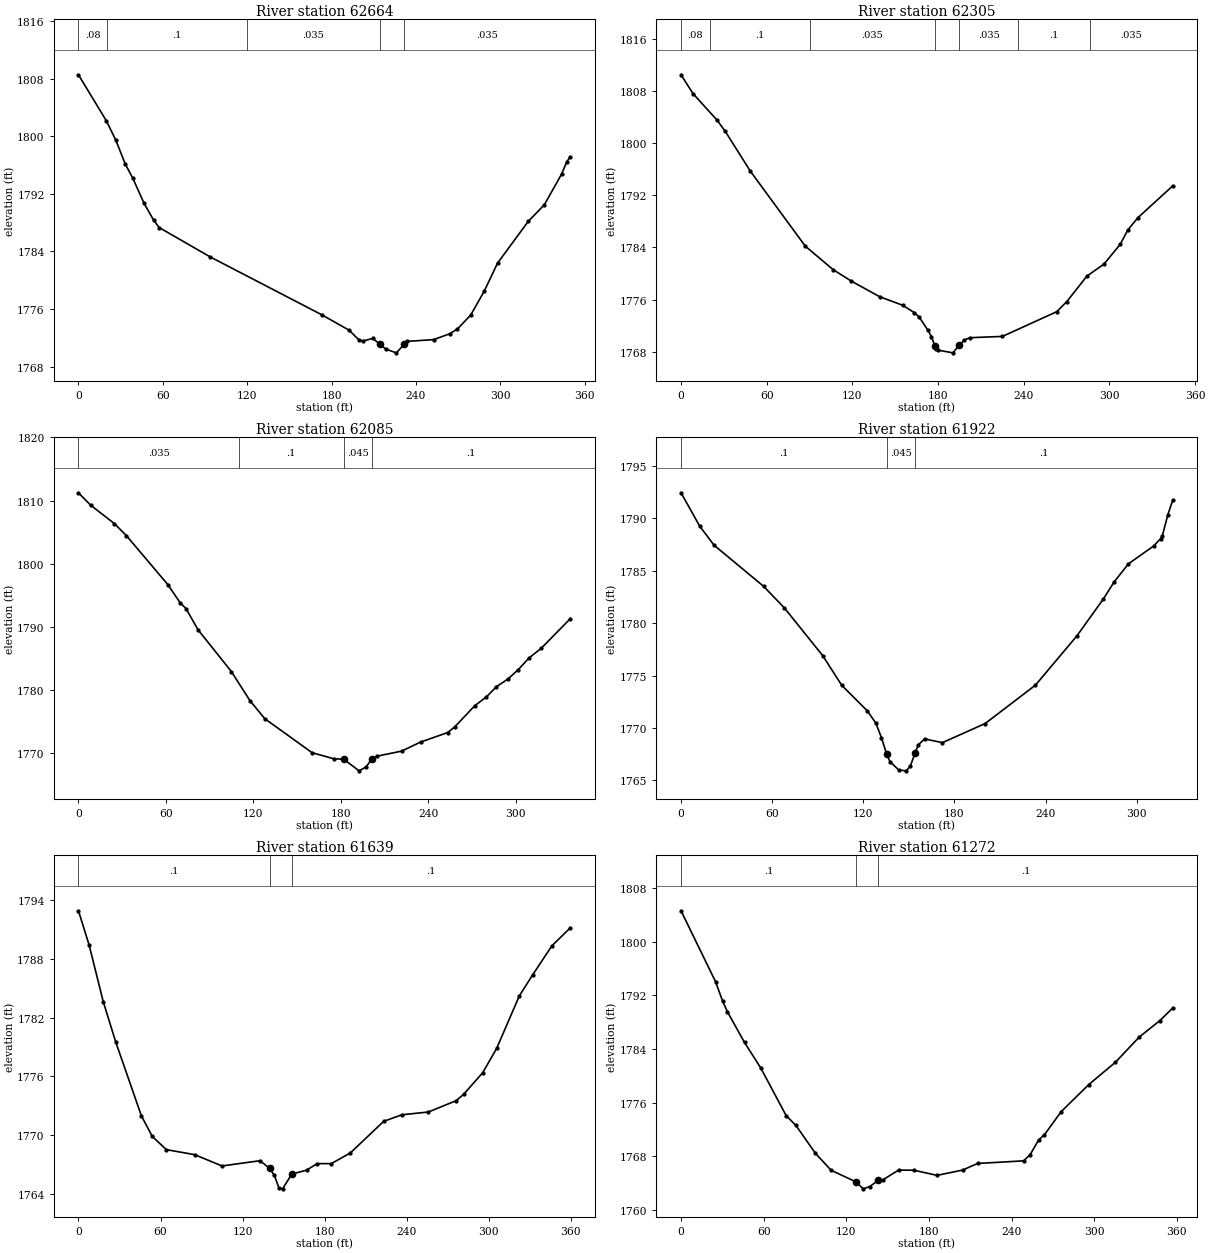
Type RM Length L Ch R = 1 ,62664   ,359.9,358.9,342.4
XS GIS Cut Line= 3
     2067982.639      222873.426     2068133.464      222840.874
     2068302.735      222743.218
#Sta/Elev= 30
       0 1808.55    19.8 1802.17    26.6 1799.45    33.3 1796.14    38.7 1794.16
    46.7 1790.67    53.4 1788.37    57.4 1787.32    93.7 1783.24   173.3 1775.17
   192.5 1773.05   199.5 1771.69   202.1 1771.55   209.3 1771.91   214.1 1771.15
   218.5 1770.43   226.1 1769.91   231.71771.125   233.6  1771.5   252.6 1771.75
   263.9 1772.55   269.4 1773.21     279 1775.18   288.6  1778.5     298 1782.37
   319.8 1788.17   331.3 1790.49   343.5 1794.73   347.2 1796.44   349.7 1797.17
#Mann= 5 ,-1 , 0
       0     .08       0      20      .1       0     120    .035       0
   214.1    .045       0   231.7    .035       0
Bank Sta=214.1,231.7
XS Rating Curve= 0 ,0
Exp/Cntr=0.3,0.1

Type RM Length L Ch R = 1 ,62305   ,210.6,220.5,227.1
XS GIS Cut Line= 3
     2068177.952       223165.31     2068313.586      223111.056
     2068422.093       222945.04
#Sta/Elev= 30
       0 1810.47     8.4 1807.58    25.2 1803.52    30.9 1801.82    48.5  1795.7
      87 1784.19   106.6 1780.57   119.2 1778.83   139.2 1776.42   155.1 1775.13
   163.5 1773.97   166.9 1773.27     173 1771.25   175.4 1770.29   177.7 1768.93
   178.7 1768.42   180.1 1768.23   190.4 1767.82   194.81768.986   198.3 1769.77
   202.2 1770.14   225.1 1770.34   263.1 1774.13   270.2 1775.69   284.2 1779.58
   296.2 1781.44   307.6 1784.47   312.8 1786.64   319.9 1788.54   344.4 1793.44
#Mann= 7 ,-1 , 0
       0     .08       0      20      .1       0      90    .035       0
   177.7    .045       0   194.8    .035       0  236.08      .1       0
  286.08    .035       0
Bank Sta=177.7,194.8
XS Rating Curve= 0 ,0
Exp/Cntr=0.3,0.1

Type RM Length L Ch R = 1 ,62085   ,164,162.7,159.8
XS GIS Cut Line= 3
     2068307.075      223320.474     2068405.817       223246.69
     2068594.619      223145.778
#Sta/Elev= 30
       0 1811.23     8.3 1809.28    24.7 1806.34    32.9 1804.44    61.3 1796.69
    69.7 1793.83    73.8 1792.88      82 1789.54   104.9 1782.91   117.6 1778.32
   127.8 1775.45   160.2 1770.07   175.1  1769.1   181.91769.036   192.5 1767.19
   197.4 1767.83   201.1 1769.06   204.7 1769.51   221.6 1770.31   234.6 1771.74
   253.2 1773.25     258 1774.13   271.8  1777.5   279.8  1778.9   286.7 1780.52
   294.4  1781.7   301.6  1783.2   308.9 1785.04   317.3 1786.58   337.3 1791.28
#Mann= 4 ,-1 , 0
       0    .035       0     110      .1       0   181.9    .045       0
   201.1      .1       0
Bank Sta=181.9,201.1
XS Rating Curve= 0 ,0
Exp/Cntr=0.3,0.1

Type RM Length L Ch R = 1 ,61922   ,276.8,283,287.2
XS GIS Cut Line= 3
     2068443.794      223455.023     2068514.323      223367.132
     2068686.849      223245.605
#Sta/Elev= 30
       0 1792.42    12.3 1789.24    21.7 1787.43    54.3 1783.51    67.9 1781.47
    93.2 1776.91   105.8 1774.07   122.6 1771.64   128.2 1770.48   131.9 1769.09
   135.41767.495   137.5 1766.81   143.2 1766.01   148.2 1765.92   150.9 1766.36
     154 1767.59   156.2  1768.4   160.3 1768.96   172.1 1768.61   200.2 1770.43
   233.3 1774.09   260.6 1778.79     278  1782.3   285.1 1783.93   294.5 1785.65
     311 1787.34   315.7 1788.05   316.8 1788.32   320.4 1790.31   323.7 1791.75
#Mann= 3 ,-1 , 0
       0      .1       0   135.4    .045       0     154      .1       0
Bank Sta=135.4,154
XS Rating Curve= 0 ,0
Exp/Cntr=0.3,0.1

Type RM Length L Ch R = 1 ,61639   ,372.6,366.9,351.4
XS GIS Cut Line= 3
      2068532.77      223630.804     2068747.613      223555.935
     2068878.907       223570.04
#Sta/Elev= 30
       0 1792.93     7.8 1789.43    18.2  1783.6    27.2 1779.53      46 1771.96
      54 1769.84    64.3 1768.49    84.9 1767.98     105 1766.82   132.8 1767.36
   139.8 1766.57   143.3 1765.85   146.7 1764.53   149.3 1764.48     1561765.994
   166.8 1766.39   174.5 1767.06   184.9 1767.06   198.8 1768.15   223.2 1771.39
   236.6 1772.06   255.8 1772.34   276.2  1773.5   281.7 1774.16   295.6 1776.36
   305.9 1778.88   322.4 1784.23   332.3 1786.41   346.2 1789.35   359.6 1791.18
#Mann= 3 ,-1 , 0
       0      .1       0   139.8    .045       0     156      .1       0
Bank Sta=139.8,156
XS Rating Curve= 0 ,0
Exp/Cntr=0.3,0.1

Type RM Length L Ch R = 1 ,61272   ,235,230.9,223
XS GIS Cut Line= 3
     2068674.914      223982.367      2068849.61      223771.863
      2068922.31      223730.631
#Sta/Elev= 30
       0 1804.59    25.1 1794.01    30.3 1791.08    33.6 1789.58    46.1 1784.97
    57.8 1781.21    76.3 1774.09    83.4 1772.62    97.6 1768.46     109 1765.93
     1271764.213   132.3 1763.17     137  1763.5   143.31764.447   146.3 1764.47
     158 1765.97   169.1 1765.94   185.9 1765.18   204.5 1765.97   215.3 1766.95
   248.8 1767.34   253.5 1768.26   259.6 1770.43   263.9 1771.24     276 1774.66
   296.1 1778.71   315.4 1782.02   332.6 1785.76   347.7 1788.23   357.1 1790.12
#Mann= 3 ,-1 , 0
       0      .1       0     127    .045       0   143.3      .1       0
Bank Sta=127,143.3
XS Rating Curve= 0 ,0
Exp/Cntr=0.3,0.1

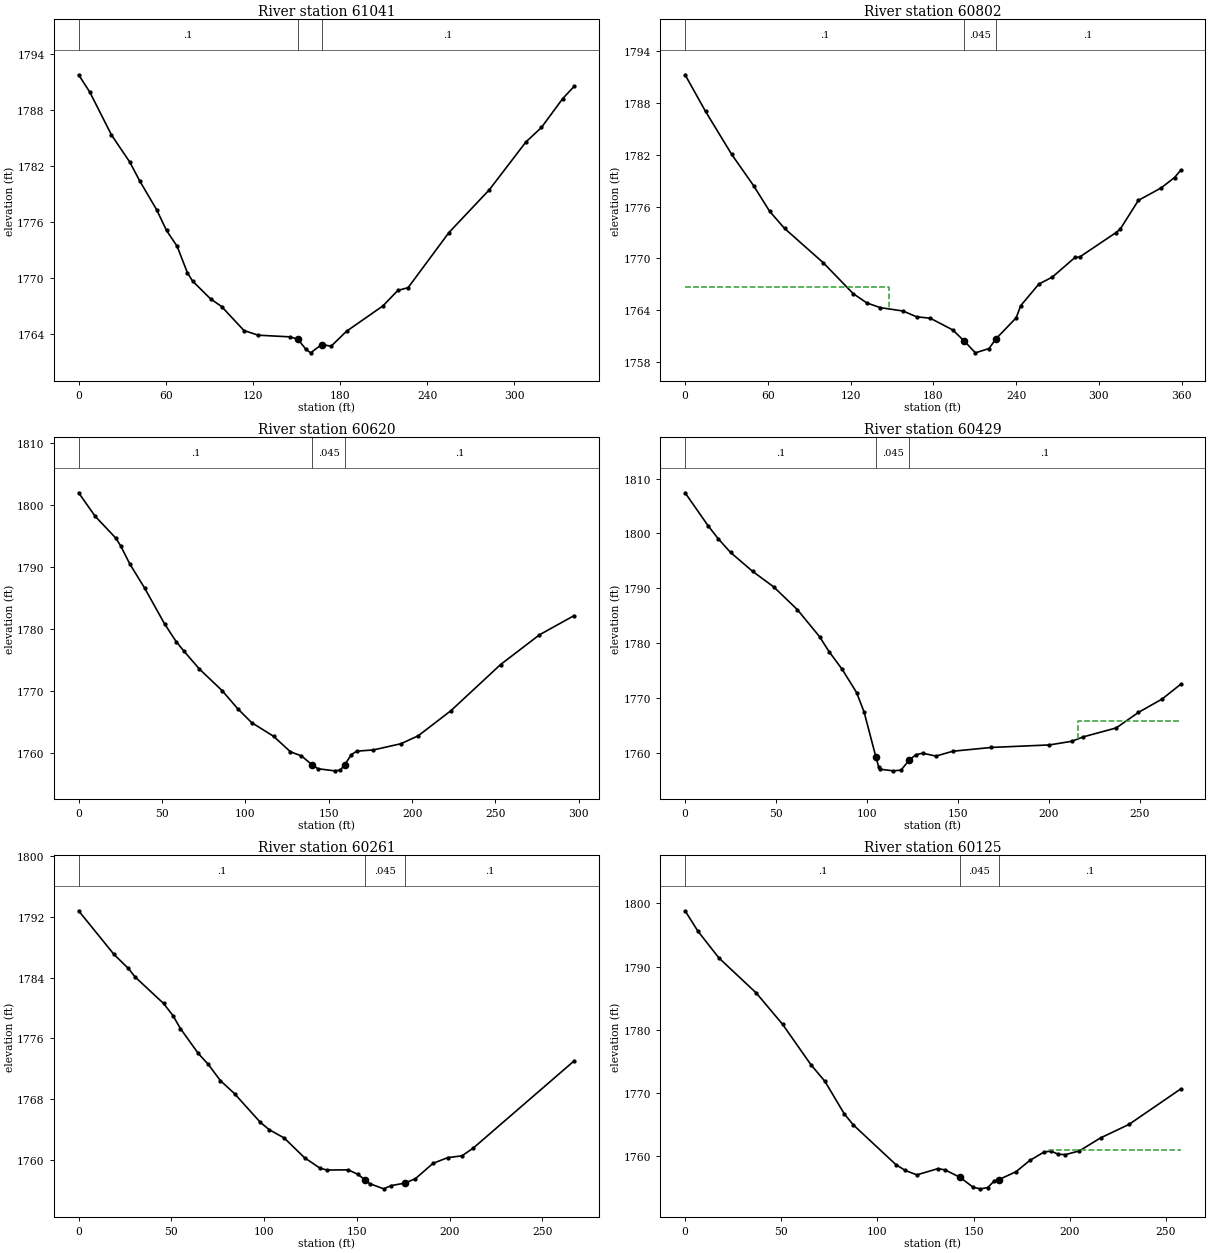
Type RM Length L Ch R = 1 ,61041   ,213.9,238.9,262.5
XS GIS Cut Line= 2
     2068891.928      224127.766     2069018.374      223810.926
#Sta/Elev= 30
       0 1791.74     7.8 1789.85    22.6  1785.3    35.3 1782.37    42.1 1780.36
    53.7 1777.29    60.5 1775.07    67.8 1773.38    74.9 1770.53    78.4 1769.66
    90.8 1767.75    98.4 1766.93   113.8 1764.36   123.6 1763.86   145.6 1763.68
   150.91763.428   156.5 1762.34   159.7 1761.97   167.31762.859   173.8 1762.68
   184.4 1764.28   209.5    1767   219.7 1768.65   226.8 1768.95   254.9 1774.85
   282.7 1779.43   307.9 1784.55   318.6  1786.1   333.2 1789.19   341.1  1790.5
#Mann= 3 ,-1 , 0
       0      .1       0   150.9    .045       0   167.3      .1       0
Bank Sta=150.9,167.3
XS Rating Curve= 0 ,0
Exp/Cntr=0.3,0.1

Type RM Length L Ch R = 1 ,60802   ,184.1,182.7,178.9
XS GIS Cut Line= 3
     2068917.969      224151.638      2069014.54      224090.874
     2069259.694      224086.968
#Sta/Elev= 30
       0 1791.26    14.8 1787.03    33.8 1782.04    49.7 1778.42    61.3 1775.46
    72.1 1773.48   100.1 1769.52   121.9 1765.93   131.8 1764.85   141.6 1764.31
     158 1763.92   167.9 1763.25   177.7 1763.09   194.1 1761.73   202.4 1760.44
   210.5 1759.08   220.4 1759.58   225.21760.667   240.1 1763.14   243.3 1764.53
   256.5 1767.04   266.3 1767.85   282.7 1770.12     286 1770.16   312.3 1772.98
   315.5  1773.4   328.7 1776.73   345.1 1778.16   354.9 1779.37   359.3 1780.21
#Mann= 3 ,-1 , 0
       0      .1       0   202.4    .045       0   225.2      .1       0
#XS Ineff= 2 , 0
          147.87 1766.74
Permanent Ineff=
       F       F
Bank Sta=202.4,225.2
XS Rating Curve= 0 ,0
Exp/Cntr=0.3,0.1

Type RM Length L Ch R = 1 ,60620   ,198.1,190.3,179.7
XS GIS Cut Line= 3
     2068973.308      224312.228     2069062.284      224264.485
     2069256.222      224234.537
#Sta/Elev= 30
       0    1802     9.9 1798.21    22.2  1794.7    25.2 1793.43    30.7 1790.49
    39.7 1786.54    51.5 1780.83    58.5 1777.94    63.1 1776.42    72.4 1773.52
    86.2 1769.98    95.4  1767.1   103.7 1764.86     117 1762.62     127 1760.13
   133.6 1759.47   140.21757.985   143.6 1757.39   153.5 1757.05   156.9 1757.17
   159.7 1758.07   163.5 1759.65   166.8 1760.23   176.8 1760.43   193.4 1761.44
   203.7 1762.72   223.3 1766.78   253.1 1774.24   276.4 1779.04   297.2 1782.15
#Mann= 3 ,-1 , 0
       0      .1       0   140.2    .045       0   159.7      .1       0
Bank Sta=140.2,159.7
XS Rating Curve= 0 ,0
Exp/Cntr=0.3,0.1

Type RM Length L Ch R = 1 ,60429   ,165.4,167.8,169.9
XS GIS Cut Line= 2
     2069044.922      224506.455     2069264.106       224344.78
#Sta/Elev= 30
       0 1807.42    12.7 1801.38    18.2 1799.04      25 1796.53    37.2 1793.06
    48.7 1790.25    61.7  1786.1    73.9 1781.17    79.2 1778.41    86.4 1775.18
    94.3 1770.95    98.4  1767.4   104.91759.189   106.5 1757.29   107.4 1756.97
   114.4 1756.68   118.7 1756.81   123.21758.646   126.9 1759.62   130.6  1759.9
   137.9 1759.37   147.2 1760.26   168.4 1760.95   200.3 1761.41   212.5 1762.07
     219 1762.89     237 1764.51   249.2 1767.34   262.2 1769.78   272.4 1772.47
#Mann= 3 ,-1 , 0
       0      .1       0   104.9    .045       0   123.2      .1       0
#XS Ineff= 2 , 0
                          215.76          1765.8
Permanent Ineff=
       F       F
Bank Sta=104.9,123.2
XS Rating Curve= 0 ,0
Exp/Cntr=0.3,0.1

Type RM Length L Ch R = 1 ,60261   ,135,136.2,137.2
XS GIS Cut Line= 2
     2069117.622      224632.323     2069346.572       224494.52
#Sta/Elev= 30
       0  1792.8      19 1787.07    26.7 1785.23    30.5 1784.07    45.8 1780.59
    50.9 1778.98    54.9 1777.28    64.5 1774.01    69.9 1772.57    76.4 1770.44
    84.1  1768.7    97.9 1764.95   102.7 1763.97   110.9 1762.86   121.8 1760.27
   130.1  1758.9   133.8 1758.65   145.4 1758.67   150.5 1758.09   154.41757.356
   156.9 1756.86   164.5 1756.17   168.4 1756.59     176 1756.93   181.6 1757.51
   191.1 1759.53     199 1760.28   206.7 1760.52   212.7 1761.52   267.2 1773.03
#Mann= 3 ,-1 , 0
       0      .1       0   154.4    .045       0     176      .1       0
Bank Sta=154.4,176
XS Rating Curve= 0 ,0
Exp/Cntr=0.3,0.1

Type RM Length L Ch R = 1 ,60125   ,130.2,129,128.1
XS GIS Cut Line= 2
     2069183.811       224734.32     2069413.846      224618.218
#Sta/Elev= 30
       0 1798.83     6.6 1795.63    17.6 1791.36      37 1785.82    50.7 1780.86
    65.4 1774.48    72.7 1771.84    82.7 1766.73    87.4 1764.96   109.6 1758.66
   114.5 1757.73   120.5 1757.03   131.5 1758.02   135.2 1757.82     1431756.637
   149.9 1755.05   153.6 1754.82   157.3 1755.01   160.9  1756.1   163.11756.275
     172 1757.51   179.3 1759.32   186.7 1760.65   190.2 1760.79     194 1760.31
   197.7 1760.23     205 1760.82   216.1 1762.89   230.8 1765.01   257.7 1770.62
#Mann= 3 ,-1 , 0
       0      .1       0     143    .045       0   163.1      .1       0
#XS Ineff= 2 , 0
                          189.16         1760.97
Permanent Ineff=
       F       F
Bank Sta=143,163.1
XS Rating Curve= 0 ,0
Exp/Cntr=0.3,0.1