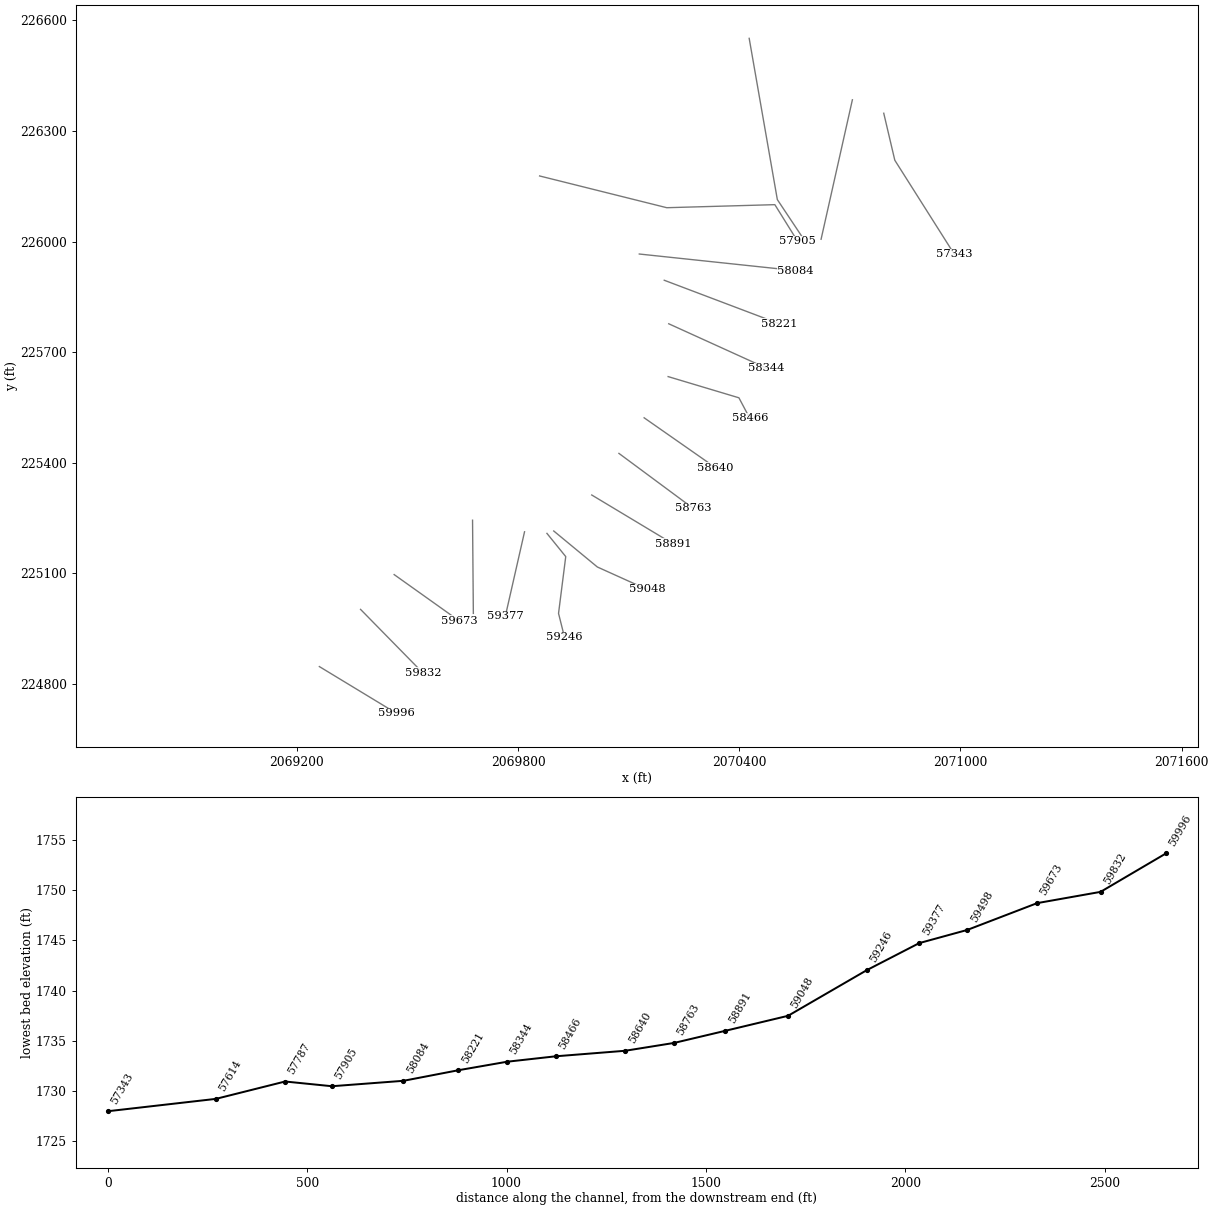
HEC-RAS study WOLFCK.prj: WOLFCK

--- WOLFCK.g01 (geometry) --- (continued)

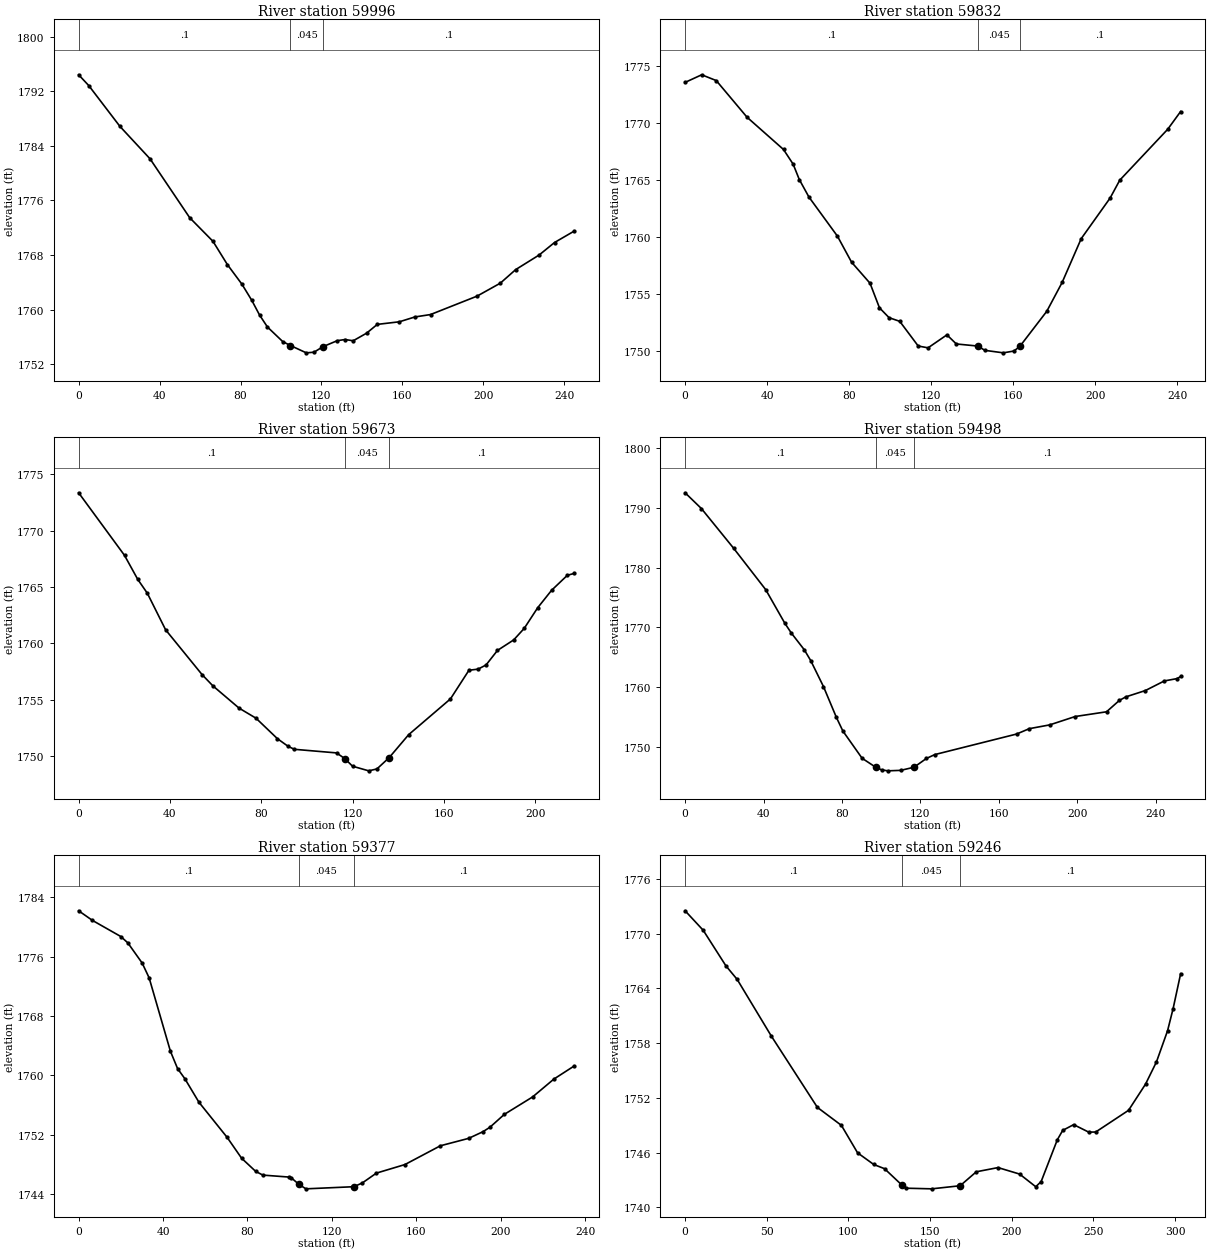
Type RM Length L Ch R = 1 ,59996   ,168,164.1,159.2
XS GIS Cut Line= 2
     2069260.851      224847.167      2069470.27      224720.214
#Sta/Elev= 30
       0  1794.4       5 1792.82    20.4 1786.84    35.3 1782.08    54.9 1773.45
    66.4 1769.99    73.5 1766.59    80.7 1763.71    85.6 1761.33    89.4  1759.2
    93.3 1757.44   100.9 1755.29   104.7 1754.72   112.5 1753.65   116.3 1753.74
   120.8 1754.56   127.8 1755.43   131.6  1755.6   135.7 1755.42   142.3 1756.53
   147.6 1757.82   158.5  1758.2   166.2 1758.91   173.9 1759.26   196.9 1761.96
   208.4 1763.86     216 1765.85   227.6 1767.99   235.2 1769.82   244.9 1771.49
#Mann= 3 ,-1 , 0
       0      .1       0   104.7    .045       0   120.8      .1       0
Bank Sta=104.7,120.8
XS Rating Curve= 0 ,0
Exp/Cntr=0.3,0.1

Type RM Length L Ch R = 1 ,59832   ,155.8,159,162.8
XS GIS Cut Line= 2
     2069372.613      225002.332     2069541.884      224829.806
#Sta/Elev= 30
       0  1773.6     8.1 1774.27    15.2 1773.76    30.2 1770.54      48  1767.7
    52.7 1766.41    55.7 1765.06    60.4 1763.52    74.3 1760.08    81.2 1757.79
    90.2 1755.94    94.8 1753.78    99.5 1752.91   104.7 1752.59   113.7 1750.42
   118.5 1750.26   127.7  1751.4   132.3  1750.6   142.81750.416   146.2 1750.04
   155.2 1749.82   160.4 1749.98   163.31750.394   176.4 1753.47   183.9 1756.01
   193.2 1759.86   207.3 1763.43     212    1765   235.4 1769.48   241.7 1771.04
#Mann= 3 ,-1 , 0
       0      .1       0   142.8    .045       0   163.3      .1       0
Bank Sta=142.8,163.3
XS Rating Curve= 0 ,0
Exp/Cntr=0.3,0.1

Type RM Length L Ch R = 1 ,59673   ,194,175.3,156.4
XS GIS Cut Line= 2
     2069463.759      225096.733     2069640.626      224970.865
#Sta/Elev= 30
       0 1773.36    20.1 1767.81    25.9 1765.68    30.1 1764.45    38.1 1761.21
    54.1 1757.23    58.8 1756.24    70.3 1754.26    77.7 1753.37    87.1 1751.55
    91.8 1750.87    94.5 1750.61     113 1750.29   116.61749.786     120 1749.11
   127.1  1748.7   130.7 1748.87   136.11749.883   144.6 1751.91   162.9 1755.08
     171 1757.62     175 1757.72   178.5 1758.09   183.5 1759.38   190.6 1760.31
   195.2 1761.33   201.1 1763.16   207.2 1764.71   214.1 1766.04   217.1 1766.21
#Mann= 3 ,-1 , 0
       0      .1       0   116.6    .045       0   136.1      .1       0
Bank Sta=116.6,136.1
XS Rating Curve= 0 ,0
Exp/Cntr=0.3,0.1

Type RM Length L Ch R = 1 ,59498   ,125.1,120.4,116.8
XS GIS Cut Line= 2
     2069676.433      225244.303     2069678.603      224991.481
#Sta/Elev= 30
       0 1792.51     8.3 1789.88    24.7 1783.26    41.1 1776.33    50.9 1770.69
    54.2 1769.06    60.8 1766.27    64.1 1764.45    70.6 1760.11    77.2 1754.95
    80.5 1752.68    90.3 1748.13    97.21746.642   100.2  1746.2   103.4 1746.03
     110 1746.11   116.81746.635   123.1  1748.1   127.4 1748.75   169.1 1752.18
   175.6 1753.08     186 1753.71     199 1755.11     215  1755.9   221.5 1757.79
   224.8 1758.39   234.8 1759.45   244.5 1761.06     251 1761.45   252.8  1761.8
#Mann= 3 ,-1 , 0
       0      .1       0    97.2    .045       0   116.8      .1       0
Bank Sta=97.2,116.8
XS Rating Curve= 0 ,0
Exp/Cntr=0.3,0.1

Type RM Length L Ch R = 1 ,59377   ,128.6,131.4,133.5
XS GIS Cut Line= 2
     2069817.492      225212.836     2069765.409      224983.886
#Sta/Elev= 30
       0 1782.18     6.5 1780.89      20 1778.71    23.3 1777.86    30.1 1775.14
    33.4 1773.15    43.5 1763.25    46.9 1760.91    50.3 1759.57      57 1756.39
    70.4 1751.64    77.2 1748.85    83.9 1747.07    87.3 1746.57    99.5 1746.31
   100.7 1746.22   104.41745.321   107.7 1744.72   130.41745.007   134.4 1745.51
   141.1 1746.84   154.6 1747.99   171.4 1750.52   184.8 1751.52   191.6 1752.42
   194.9 1753.02   201.7 1754.75   215.1  1757.1   225.2 1759.51   234.8 1761.27
#Mann= 3 ,-1 , 0
       0      .1       0   104.4    .045       0   130.4      .1       0
Bank Sta=104.4,130.4
XS Rating Curve= 0 ,0
Exp/Cntr=0.3,0.1

Type RM Length L Ch R = 1 ,59246   ,161,197.7,229.9
XS GIS Cut Line= 4
     2069878.256      225208.495     2069929.254      225145.561
     2069909.723      224991.481     2069925.999      224926.377
#Sta/Elev= 30
       0 1772.52    11.1 1770.38      25 1766.48    31.9 1764.99    52.8 1758.78
      81 1750.96    95.7 1748.99   105.6 1745.98   115.5  1744.7   122.1 1744.24
   132.81742.433   135.3  1742.1     151 1742.03   168.4 1742.37   178.3  1743.9
   191.6 1744.36   204.8 1743.65   214.7 1742.26     218 1742.83   227.9 1747.41
   231.2 1748.44   237.9 1749.07   247.1 1748.25   251.4 1748.26   271.5 1750.64
   281.9 1753.51   288.6 1755.95   295.4 1759.37   298.8  1761.8   303.4 1765.62
#Mann= 3 ,-1 , 0
       0      .1       0   132.8    .045       0   168.4      .1       0
Bank Sta=132.8,168.4
XS Rating Curve= 0 ,0
Exp/Cntr=0.3,0.1

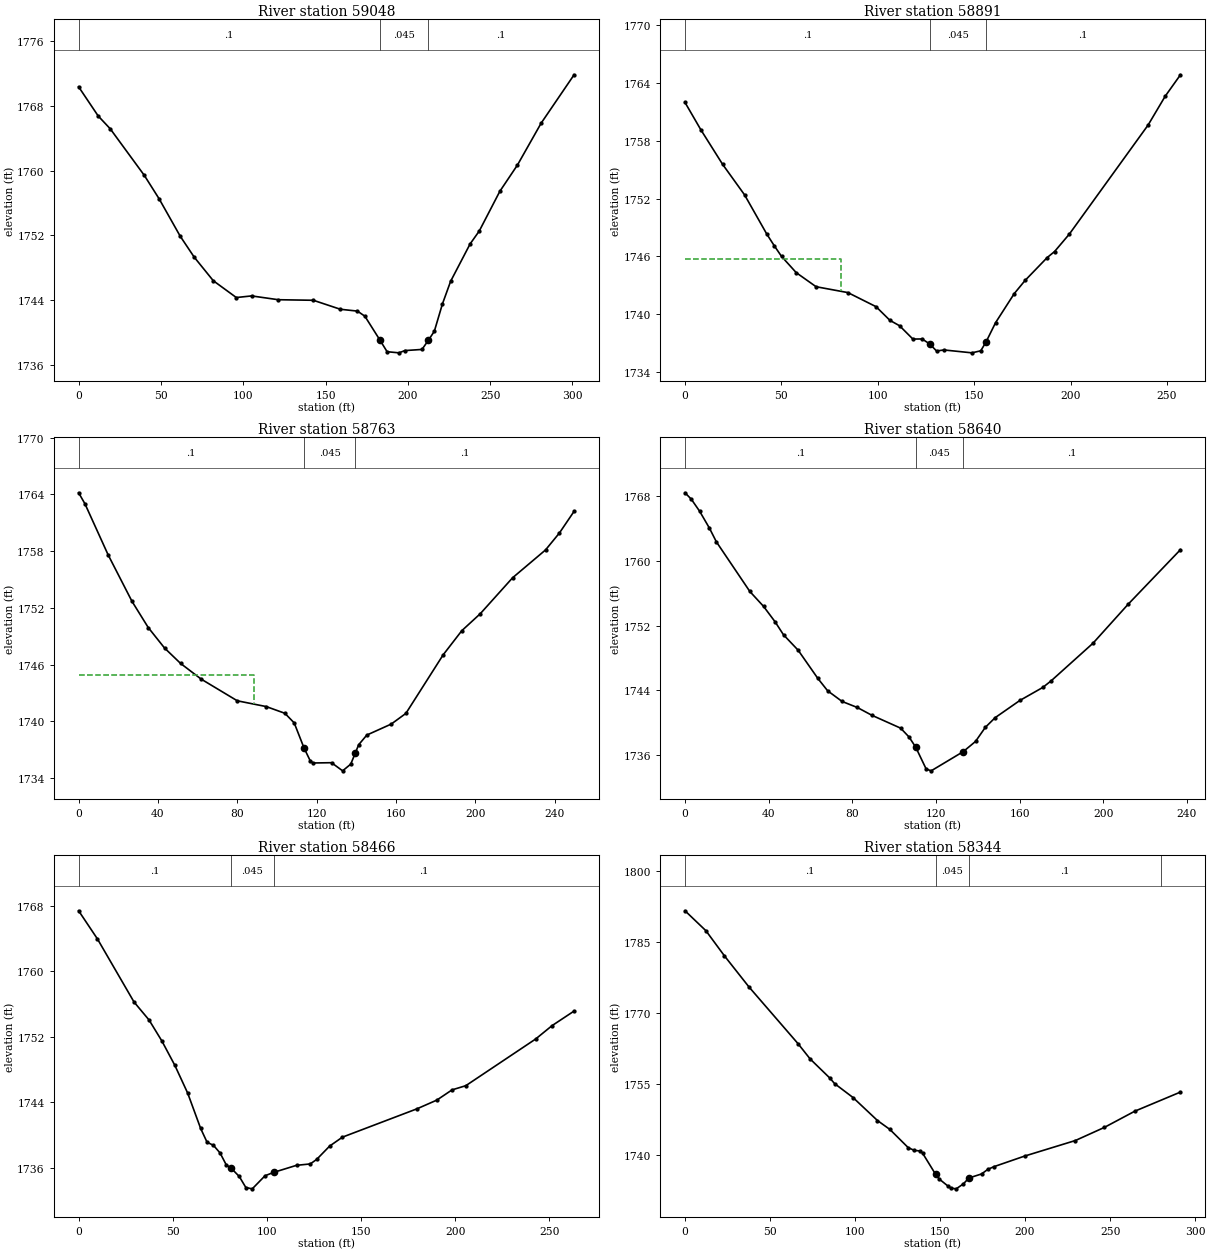
Type RM Length L Ch R = 1 ,59048   ,159.5,157,153.7
XS GIS Cut Line= 3
     2069896.702      225215.006     2070014.974      225117.349
     2070149.523      225056.586
#Sta/Elev= 30
       0 1770.38    11.9 1766.77    19.2 1765.19    39.9 1759.43    48.9 1756.53
    61.7 1751.91    70.2 1749.32    81.8  1746.4    95.8 1744.32   105.1 1744.52
   121.3 1744.05   142.6 1743.98     159 1742.87   169.4 1742.64   173.9 1742.01
   182.91739.105   187.4 1737.62   194.6 1737.48   198.2 1737.76   208.6  1737.9
   212.41739.013   216.1 1740.15     221 1743.52     226 1746.33   237.8 1750.94
   243.4 1752.55   255.9 1757.46   266.6 1760.71     281 1765.89     301 1771.87
#Mann= 3 ,-1 , 0
       0      .1       0   182.9    .045       0   212.4      .1       0
Bank Sta=182.9,212.4
XS Rating Curve= 0 ,0
Exp/Cntr=0.3,0.1

Type RM Length L Ch R = 1 ,58891   ,127.7,128.8,123.6
XS GIS Cut Line= 2
     2069999.784      225312.662     2070220.053      225180.284
#Sta/Elev= 30
       0 1761.97     8.2 1759.14    19.5 1755.55    30.9 1752.38    42.4 1748.32
    46.3  1747.1    50.1 1745.99    57.7 1744.31      68 1742.85    84.5 1742.24
    99.1 1740.78   106.3 1739.36   111.3  1738.8   118.2 1737.42     123 1737.43
   126.91736.915   130.5 1736.18   134.3 1736.29   148.8 1735.99   153.4  1736.2
   156.11737.099   161.1 1739.12   170.8 1742.14   176.4  1743.5   187.9 1745.88
   191.7  1746.5   199.4 1748.32   240.2 1759.62   249.1 1762.62     257 1764.84
#Mann= 3 ,-1 , 0
       0      .1       0   126.9    .045       0   156.1      .1       0
#XS Ineff= 2 , 0
           80.91 1745.69
Permanent Ineff=
       F       F
Bank Sta=126.9,156.1
XS Rating Curve= 0 ,0
Exp/Cntr=0.3,0.1

Type RM Length L Ch R = 1 ,58763   ,122,122.6,123.3
XS GIS Cut Line= 2
     2070073.568      225425.509     2070274.306      225276.855
#Sta/Elev= 30
       0 1764.16     3.2 1762.99    14.9 1757.59    26.9 1752.69    35.1 1749.92
    43.3 1747.76    51.4 1746.13    61.8 1744.47      80 1742.18    94.6 1741.57
     104 1740.86   108.7 1739.84   113.61737.218   116.7 1735.87   118.1 1735.61
   127.5 1735.64   133.1 1734.78   137.2 1735.49   139.51736.665   141.2 1737.54
   145.3 1738.56   157.6 1739.72     165 1740.85   183.8 1747.04   193.2 1749.59
   202.5 1751.38   218.8 1755.18   235.4 1758.12   242.4 1759.91   249.8  1762.2
#Mann= 3 ,-1 , 0
       0      .1       0   113.6    .045       0   139.5      .1       0
#XS Ineff= 2 , 0
           88.64 1744.94
Permanent Ineff=
       F       F
Bank Sta=113.6,139.5
XS Rating Curve= 0 ,0
Exp/Cntr=0.3,0.1

Type RM Length L Ch R = 1 ,58640   ,168.3,174.2,181
XS GIS Cut Line= 2
     2070141.928       225522.08     2070336.155      225386.447
#Sta/Elev= 30
       0 1768.46       3 1767.67       7 1766.17    11.7 1764.07      15 1762.38
      31 1756.23    37.6 1754.37    43.1 1752.46    47.1 1750.86    54.1 1748.95
    63.5 1745.46    68.2 1743.92    75.1  1742.6    82.4 1741.85    89.4 1740.88
   103.1 1739.29   107.1  1738.2   110.3 1736.94   115.3 1734.23   117.7    1734
     1331736.374   138.9 1737.64   143.6 1739.39   148.3 1740.59   160.1 1742.72
   171.1 1744.34   175.1 1745.16   195.1 1749.82   211.9 1754.65   236.9 1761.41
#Mann= 3 ,-1 , 0
       0      .1       0   110.3    .045       0     133      .1       0
Bank Sta=110.3,133
XS Rating Curve= 0 ,0
Exp/Cntr=0.3,0.1

Type RM Length L Ch R = 1 ,58466   ,124.1,121.8,118.1
XS GIS Cut Line= 3
     2070207.032      225633.843     2070399.089      225576.334
     2070428.386      225520.995
#Sta/Elev= 30
       0 1767.39      10 1763.95    29.4 1756.26    37.4 1754.06    44.2  1751.5
    51.1 1748.52    57.9 1745.14    64.8 1740.82    68.2 1739.14    71.6 1738.76
    75.1 1737.83    78.5 1736.33    80.81736.018    85.3 1734.96    88.8 1733.61
    92.2 1733.45      99 1735.05   103.51735.454   115.7 1736.32     123 1736.49
   126.4 1737.04   133.3 1738.67   140.1 1739.76   179.7 1743.22   190.2 1744.28
   198.3 1745.53   205.6 1746.04   242.7 1751.74   251.4 1753.37   263.1 1755.15
#Mann= 3 ,-1 , 0
       0      .1       0    80.8    .045       0   103.5      .1       0
Bank Sta=80.8,103.5
XS Rating Curve= 0 ,0
Exp/Cntr=0.3,0.1

Type RM Length L Ch R = 1 ,58344   ,118.2,122.7,123
XS GIS Cut Line= 2
     2070208.639      225777.172     2070473.959      225656.629
#Sta/Elev= 30
       0 1791.61    12.3  1787.4    23.2 1782.09    37.6 1775.54    66.4 1763.59
    73.6 1760.33    85.2 1756.29      88 1755.12    98.8 1752.19   113.2 1747.33
   120.5 1745.45   131.3  1741.6   134.9 1741.02   138.5  1740.9   139.7 1740.46
   147.41735.967   149.6 1734.96   154.5 1733.54   156.5 1733.05   159.5 1732.91
   163.7 1733.95     1671735.203   174.4 1736.05   178.1 1737.02   181.7 1737.59
   199.7 1739.82   229.6 1743.11   246.6 1745.87   264.6 1749.31   291.4 1753.34
#Mann= 4 ,-1 , 0
       0      .1       0   147.4    .045       0     167      .1       0
     280    .035       0
Bank Sta=147.4,167
XS Rating Curve= 0 ,0
Exp/Cntr=0.3,0.1

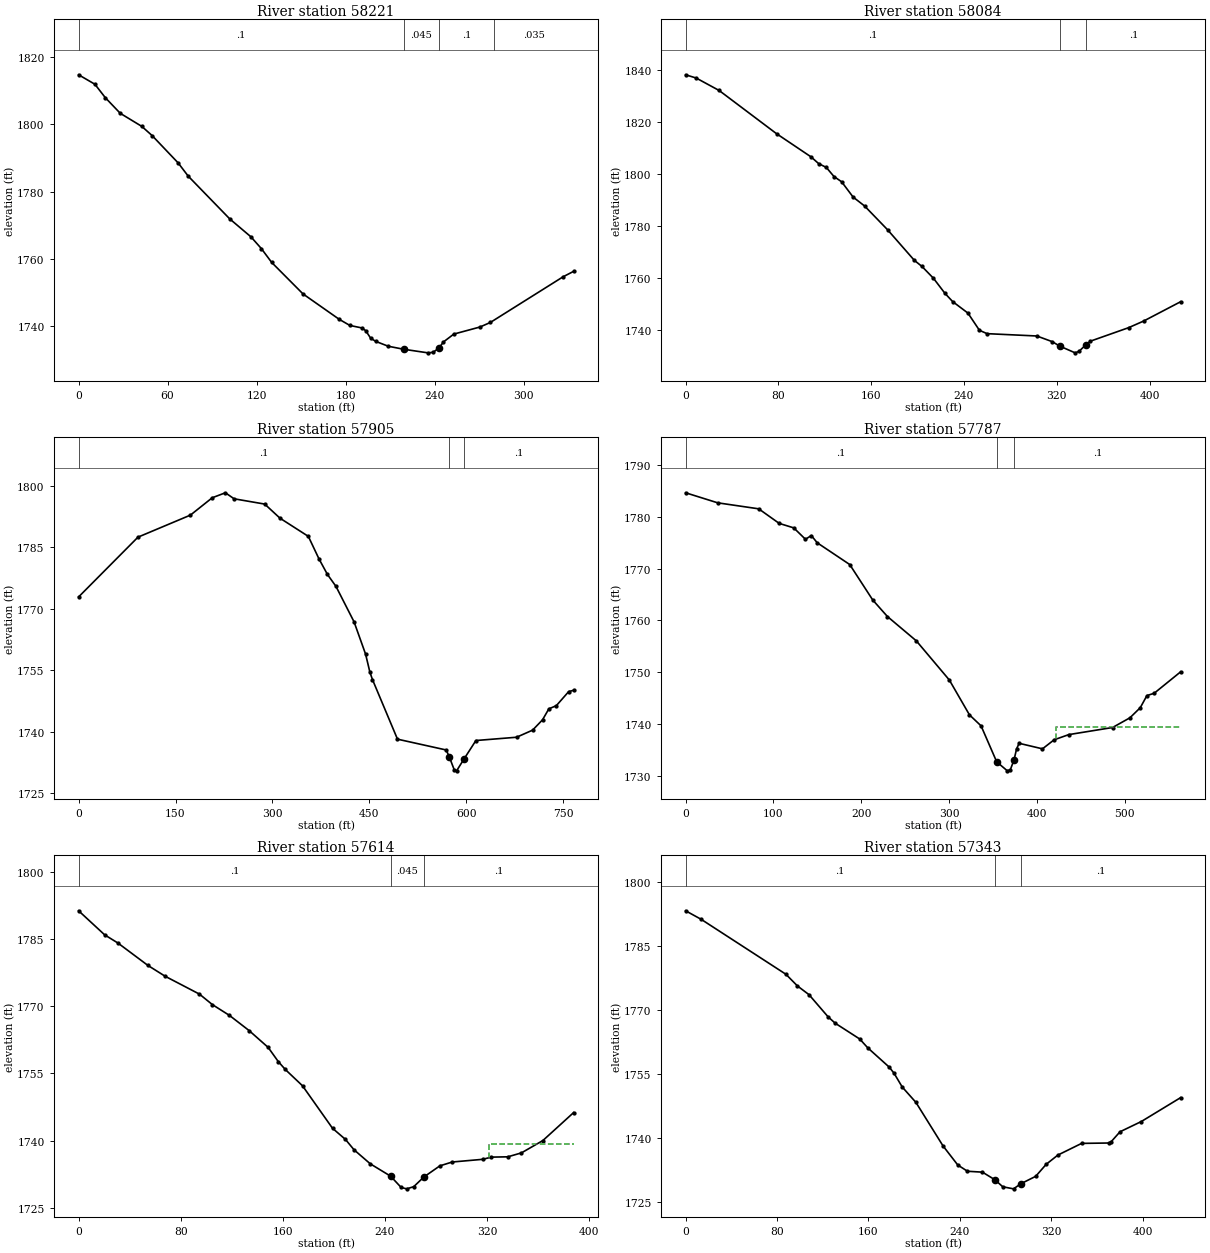
Type RM Length L Ch R = 1 ,58221   ,129.5,137.3,140.6
XS GIS Cut Line= 2
     2070196.486      225895.227     2070508.681      225777.072
#Sta/Elev= 30
       0 1814.78      11 1811.96      18 1807.97    28.1 1803.31    42.6 1799.43
    49.6 1796.68    67.1 1788.57    73.9 1784.63   101.9 1771.91   116.2 1766.57
   123.2 1763.09   130.2 1758.95   151.3 1749.59   175.7 1742.04   182.9 1740.21
     191 1739.47   193.6 1738.65   196.9 1736.43   200.4 1735.46   208.8 1734.02
   219.31733.119   235.5 1732.06     239  1732.2     2431733.524     246  1735.3
     253 1737.64   270.6 1739.74   277.6 1741.09   326.7 1754.69   333.8 1756.31
#Mann= 4 ,-1 , 0
       0      .1       0   219.3    .045       0     243      .1       0
     280    .035       0
Bank Sta=219.3,243
XS Rating Curve= 0 ,0
Exp/Cntr=0.3,0.1

Type RM Length L Ch R = 1 ,58084   ,172.5,179.4,177.7
XS GIS Cut Line= 2
     2070128.778      225966.408     2070553.169      225921.386
#Sta/Elev= 30
       0 1838.13     9.1 1836.88    28.9 1832.08    78.4 1815.43   108.1 1806.51
   114.7 1803.91   121.3 1802.43   127.9 1798.94   134.5 1796.91   144.4 1791.02
   154.3 1787.58   174.1 1778.43   197.2 1766.64   203.8 1764.28   213.7 1759.72
   223.6 1753.92   230.2 1750.77   243.4 1746.32   253.3  1739.7   259.9  1738.4
   302.8  1737.5     316 1735.33   322.51733.617   335.8 1731.01   339.1 1731.56
   345.31734.211     349 1735.51   381.9  1740.7   394.9 1743.26   426.8 1750.71
#Mann= 3 ,-1 , 0
       0      .1       0   322.5    .045       0   345.3      .1       0
Bank Sta=322.5,345.3
XS Rating Curve= 0 ,0
Exp/Cntr=0.3,0.1

Type RM Length L Ch R = 1 ,57905   ,148.8,117.5,85.1
XS GIS Cut Line= 4
2069858.36235563226178.1790382942070203.33827646226092.037992692
     2070496.543      226100.314     2070558.594      226000.596
#Sta/Elev= 30
       0 1772.92    91.9 1787.51   173.1 1792.89   206.9 1797.13   227.2 1798.34
   240.7 1796.87   288.1 1795.58   311.7 1792.14   355.6  1787.7   372.1  1782.2
   385.2  1778.4   398.4 1775.49   426.4 1766.83   444.3 1758.92   450.9 1754.54
   454.9 1752.74   493.6  1738.2     569 1735.56   573.7 1733.92   581.7 1730.62
   585.1 1730.47   596.61733.362     615 1737.87   677.9 1738.67   702.7  1740.4
   718.1 1742.92   727.9  1745.6   739.5 1746.38   758.6 1749.81   766.3 1750.14
#Mann= 3 ,-1 , 0
       0      .1       0   573.7    .045       0   596.6      .1       0
Bank Sta=573.7,596.6
XS Rating Curve= 0 ,0
Exp/Cntr=0.3,0.1

Type RM Length L Ch R = 1 ,57787   ,183.6,173.7,166.3
XS GIS Cut Line= 3
     2070426.903      226551.529     2070503.292      226114.029
     2070569.445      226014.702
#Sta/Elev= 30
       0 1784.65    36.5 1782.71    83.2 1781.55   106.5 1778.74   123.1 1777.87
   136.4 1775.67   143.1 1776.39   149.8 1774.99   186.8 1770.79     213 1763.94
   229.7 1760.75   262.6 1756.05   300.2 1748.48   323.1 1741.75   336.3 1739.63
   354.1 1732.68   366.2 1730.94   369.6 1731.14   373.9  1733.1   376.7 1735.16
   379.6 1736.26   406.2 1735.19   419.5 1736.94   436.2 1737.94     486 1739.31
   505.7 1741.18   517.5 1743.13   525.1 1745.48   533.3 1745.92   563.5 1750.07
#Mann= 3 ,-1 , 0
       0      .1       0   354.1    .045       0   373.9      .1       0
#XS Ineff= 2 , 0
                          421.11         1739.38
Permanent Ineff=
       F       F
Bank Sta=354.1,373.9
XS Rating Curve= 0 ,0
Exp/Cntr=0.3,0.1

Type RM Length L Ch R = 1 ,57614   ,253.3,271,286.6
XS GIS Cut Line= 2
     2070706.903       226384.81     2070621.962      226006.455
#Sta/Elev= 30
       0 1791.38    20.4    1786    30.8 1784.17    54.3 1779.16    67.8 1776.74
    94.7 1772.74   104.8  1770.4   118.2 1767.98   133.5 1764.61   148.5 1760.83
   156.4 1757.67   161.9  1755.9   175.4 1752.25   198.9 1742.75     209 1740.27
   215.8 1737.93   228.5  1734.8   244.41732.045   252.7 1729.51     257 1729.21
   262.5 1729.69   270.51731.862     283 1734.35   292.7 1735.21   316.6 1735.81
   323.3  1736.3   336.2 1736.37   346.9 1737.25   363.7 1740.01   387.8 1746.27
#Mann= 3 ,-1 , 0
       0      .1       0   244.4    .045       0   270.5      .1       0
#XS Ineff= 2 , 0
                          321.71         1739.13
Permanent Ineff=
       F       F
Bank Sta=244.4,270.5
XS Rating Curve= 0 ,0
Exp/Cntr=0.3,0.1

Type RM Length L Ch R = 1 ,57343   ,163.9,174.3,180
XS GIS Cut Line= 3
     2070791.972      226348.352      2070821.97      226220.819
     2070983.652       225965.44
#Sta/Elev= 30
       0 1793.14    13.6 1791.14    87.8 1778.26    97.9 1775.52     108 1773.48
   124.8 1768.26     131 1766.78   152.4 1763.09   159.4 1761.03   178.3 1756.48
   182.5 1755.04   189.6 1751.84   201.6 1748.23   225.3 1738.04   238.2 1733.57
   246.7  1732.1   259.8 1731.89   270.81730.095   277.6 1728.46     287 1727.98
   293.51729.185   306.4 1730.91   315.6 1733.73   325.8 1735.89   346.6 1738.63
   370.3 1738.72   372.4    1739   380.2 1741.35   398.9 1743.76   433.3 1749.36
#Mann= 3 ,-1 , 0
       0      .1       0   270.8    .045       0   293.5      .1       0
Bank Sta=270.8,293.5
XS Rating Curve= 0 ,0
Exp/Cntr=0.3,0.1