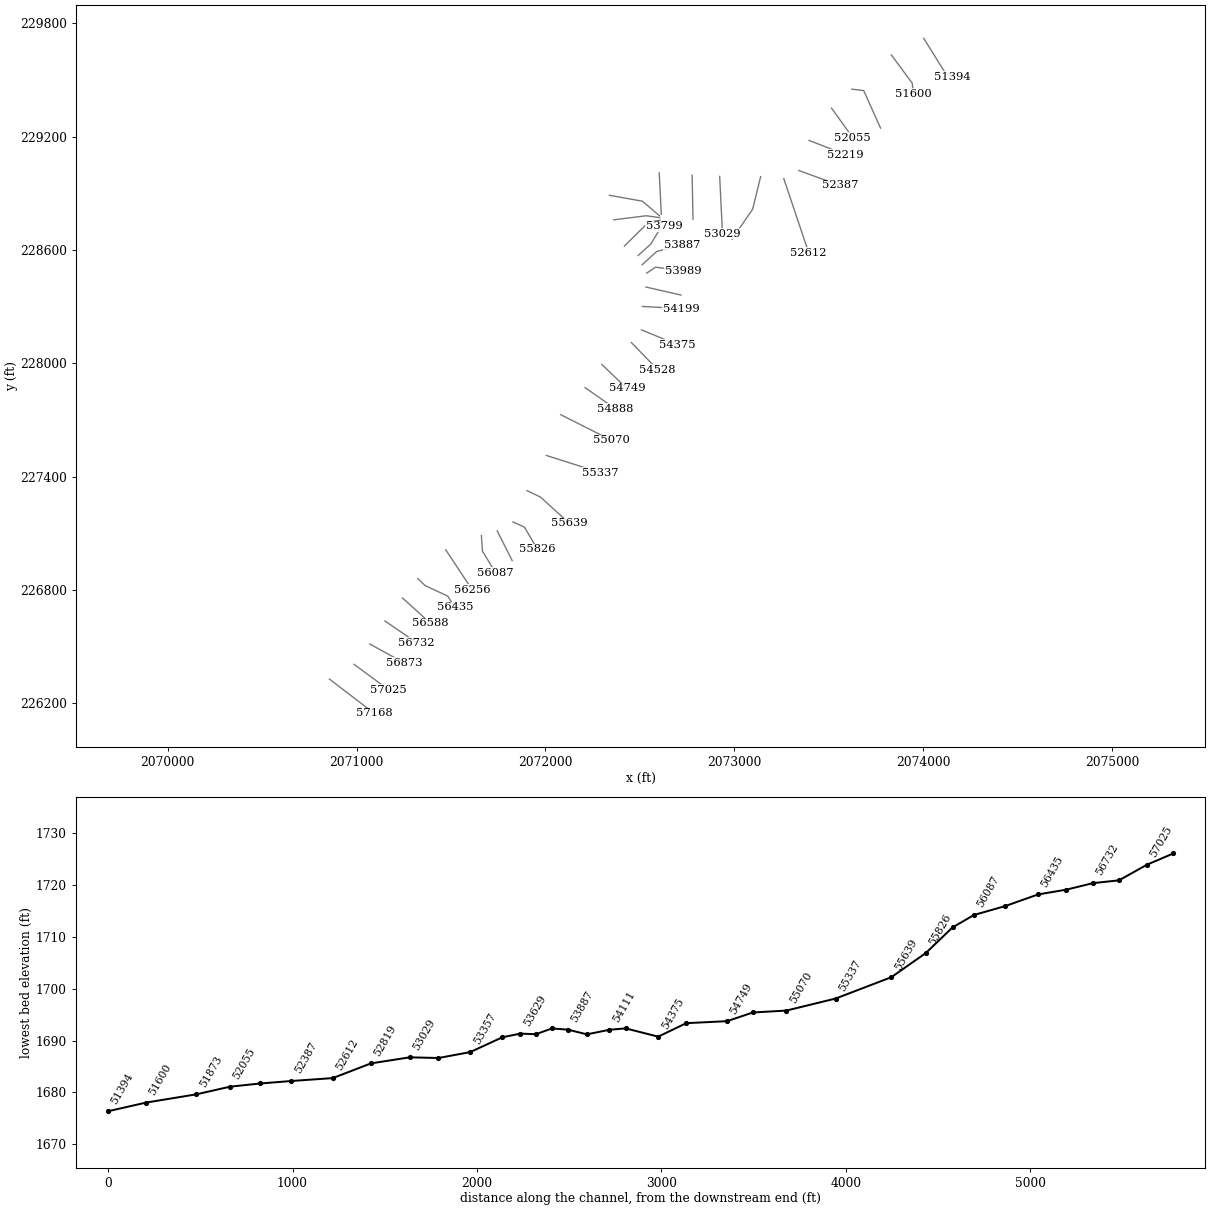
HEC-RAS study WOLFCK.prj: WOLFCK

--- WOLFCK.g01 (geometry) --- (continued)

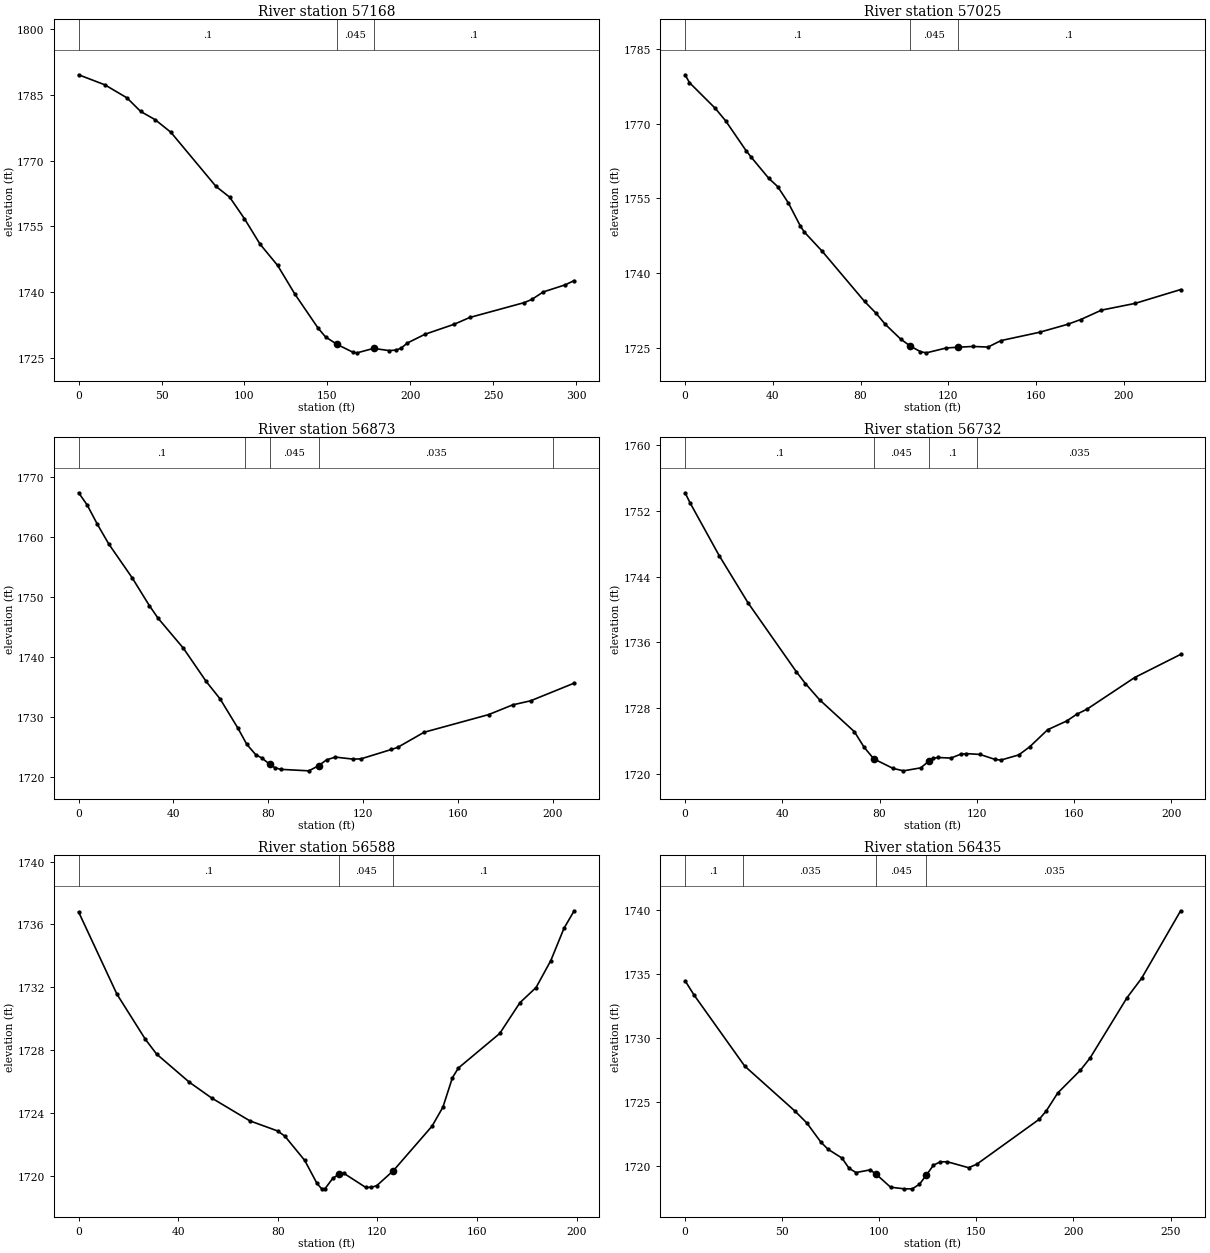
Type RM Length L Ch R = 1 ,57168   ,143.3,143.6,144.1
XS GIS Cut Line= 2
     2070856.209      226327.519     2071093.534      226145.995
#Sta/Elev= 30
       0 1789.64    15.8 1787.35    29.1 1784.38    37.4 1781.27    46.2 1779.37
    55.6 1776.52    82.8 1764.16    91.1 1761.68     100 1756.77   109.4 1750.96
     120  1746.1   130.4 1739.56   144.5 1731.73   148.9 1729.78   155.91728.066
   165.6 1726.25   167.9 1726.15   177.8 1727.16   187.3 1726.66   191.3 1726.78
   194.3 1727.19   198.3 1728.41   208.9  1730.4   226.4 1732.67   235.9 1734.23
   268.7 1737.62   273.2 1738.33   280.2 1740.06   293.5 1741.69   298.8 1742.65
#Mann= 3 ,-1 , 0
       0      .1       0   155.9    .045       0   177.8      .1       0
Bank Sta=155.9,177.8
XS Rating Curve= 0 ,0
Exp/Cntr=0.3,0.1

Type RM Length L Ch R = 1 ,57025   ,148.8,151.7,153.7
XS GIS Cut Line= 2
     2070986.417      226405.644     2071168.403      226271.863
#Sta/Elev= 30
       0 1779.78       2  1778.2    13.7 1773.07    18.5 1770.53    27.8 1764.55
    30.2 1763.21    38.1 1759.02    42.2 1757.34    47.1 1754.04    52.6 1749.37
    54.4 1748.19    62.5 1744.36    81.8 1734.29      87 1731.94    91.2 1729.72
    98.2 1726.76   102.71725.314   107.3  1724.2     110 1723.97   119.1 1724.95
   124.41725.095   131.1 1725.25   138.1 1725.13     144 1726.43   161.6  1728.1
   174.5 1729.71   180.4 1730.66   189.8 1732.54   205.1 1733.89   225.9 1736.67
#Mann= 3 ,-1 , 0
       0      .1       0   102.7    .045       0   124.4      .1       0
Bank Sta=102.7,124.4
XS Rating Curve= 0 ,0
Exp/Cntr=0.3,0.1

Type RM Length L Ch R = 1 ,56873   ,141.6,140.7,137.6
XS GIS Cut Line= 2
      2071069.75      226513.283     2071253.039      226412.922
#Sta/Elev= 30
       0  1767.3     3.6 1765.27     7.9 1762.05    12.7 1758.77    22.6 1753.12
    29.8 1748.51    33.5 1746.39    44.2 1741.38    53.8 1735.85    59.7 1732.92
    67.2 1728.05    70.9 1725.38    74.7 1723.64    77.3 1723.08    80.71722.012
    82.8 1721.47    85.2  1721.2    97.1 1720.95   101.21721.805   104.6 1722.79
   108.3 1723.24   115.8  1722.9   119.1 1722.95   131.9 1724.51   134.5 1724.85
   145.7 1727.38   172.9 1730.32   183.1 1731.95   190.6 1732.62     209 1735.57
#Mann= 5 ,-1 , 0
       0      .1       0      70    .035       0    80.7    .045       0
   101.2    .035       0     200      .1       0
Bank Sta=80.7,101.2
XS Rating Curve= 0 ,0
Exp/Cntr=0.3,0.1

Type RM Length L Ch R = 1 ,56732   ,145.7,144.3,140.1
XS GIS Cut Line= 2
     2071149.957      226635.362     2071318.143      226520.344
#Sta/Elev= 30
       0 1754.17       2 1752.97      14 1746.55    25.9  1740.8    45.8 1732.42
    49.5    1731    55.3 1729.04    69.6 1725.17    73.6 1723.29    77.6 1721.86
    85.5 1720.71    89.8 1720.41    96.9 1720.77   100.31721.597   101.8 1721.91
   103.9 1722.03   109.3 1721.96   113.3 1722.42   115.7  1722.5   121.3  1722.4
   127.5 1721.79   129.9 1721.72   137.2 1722.34   141.7 1723.32   149.1  1725.4
     157 1726.47     161 1727.27   165.3  1727.9   184.9 1731.74   203.8 1734.55
#Mann= 4 ,-1 , 0
       0      .1       0    77.6    .045       0   100.3      .1       0
     120    .035       0
Bank Sta=77.6,100.3
XS Rating Curve= 0 ,0
Exp/Cntr=0.3,0.1

Type RM Length L Ch R = 1 ,56588   ,147.3,153.2,160.1
XS GIS Cut Line= 2
     2071243.273      226756.889     2071390.843      226623.426
#Sta/Elev= 30
       0 1736.79    15.4 1731.55    26.8 1728.68    31.3 1727.74    44.5 1725.94
    53.4 1724.94    68.8 1723.48    79.9 1722.84    82.8 1722.51    90.8 1720.96
    95.7  1719.5    97.6 1719.15      99 1719.17     102 1719.81   104.41720.074
   106.5 1720.14   115.3 1719.24   117.6 1719.25   119.7 1719.35   126.41720.309
   141.9 1723.14   146.3 1724.36   150.1 1726.23   152.5 1726.85   169.1 1729.05
   177.2 1731.01   183.7 1731.98   189.6 1733.69   194.9 1735.75     199 1736.87
#Mann= 3 ,-1 , 0
       0      .1       0   104.4    .045       0   126.4      .1       0
Bank Sta=104.4,126.4
XS Rating Curve= 0 ,0
Exp/Cntr=0.3,0.1

Type RM Length L Ch R = 1 ,56435   ,186.3,178.9,160.6
XS GIS Cut Line= 4
     2071324.653      226859.971     2071362.631      226823.079
     2071483.073      226766.655     2071519.966      226708.061
#Sta/Elev= 30
       0 1734.47     4.6 1733.36    30.7 1727.81    56.5 1724.31    62.7 1723.37
    69.9 1721.88    73.6 1721.32    80.8 1720.63    84.4 1719.84      88  1719.5
    95.3 1719.71    98.4 1719.37   105.8 1718.36   112.8 1718.23     117 1718.23
   120.7 1718.59   124.3 1719.31   127.9 1720.08   131.5 1720.34   135.1 1720.34
     146 1719.88   150.2 1720.15   182.3 1723.65     186 1724.31   191.9 1725.71
   203.6 1727.49   208.6 1728.45   227.6 1733.15   235.1 1734.66   255.2 1739.93
#Mann= 4 ,-1 , 0
       0      .1       0      30    .035       0    98.4    .045       0
   124.3    .035       0
Bank Sta=98.4,124.3
XS Rating Curve= 0 ,0
Exp/Cntr=0.3,0.1

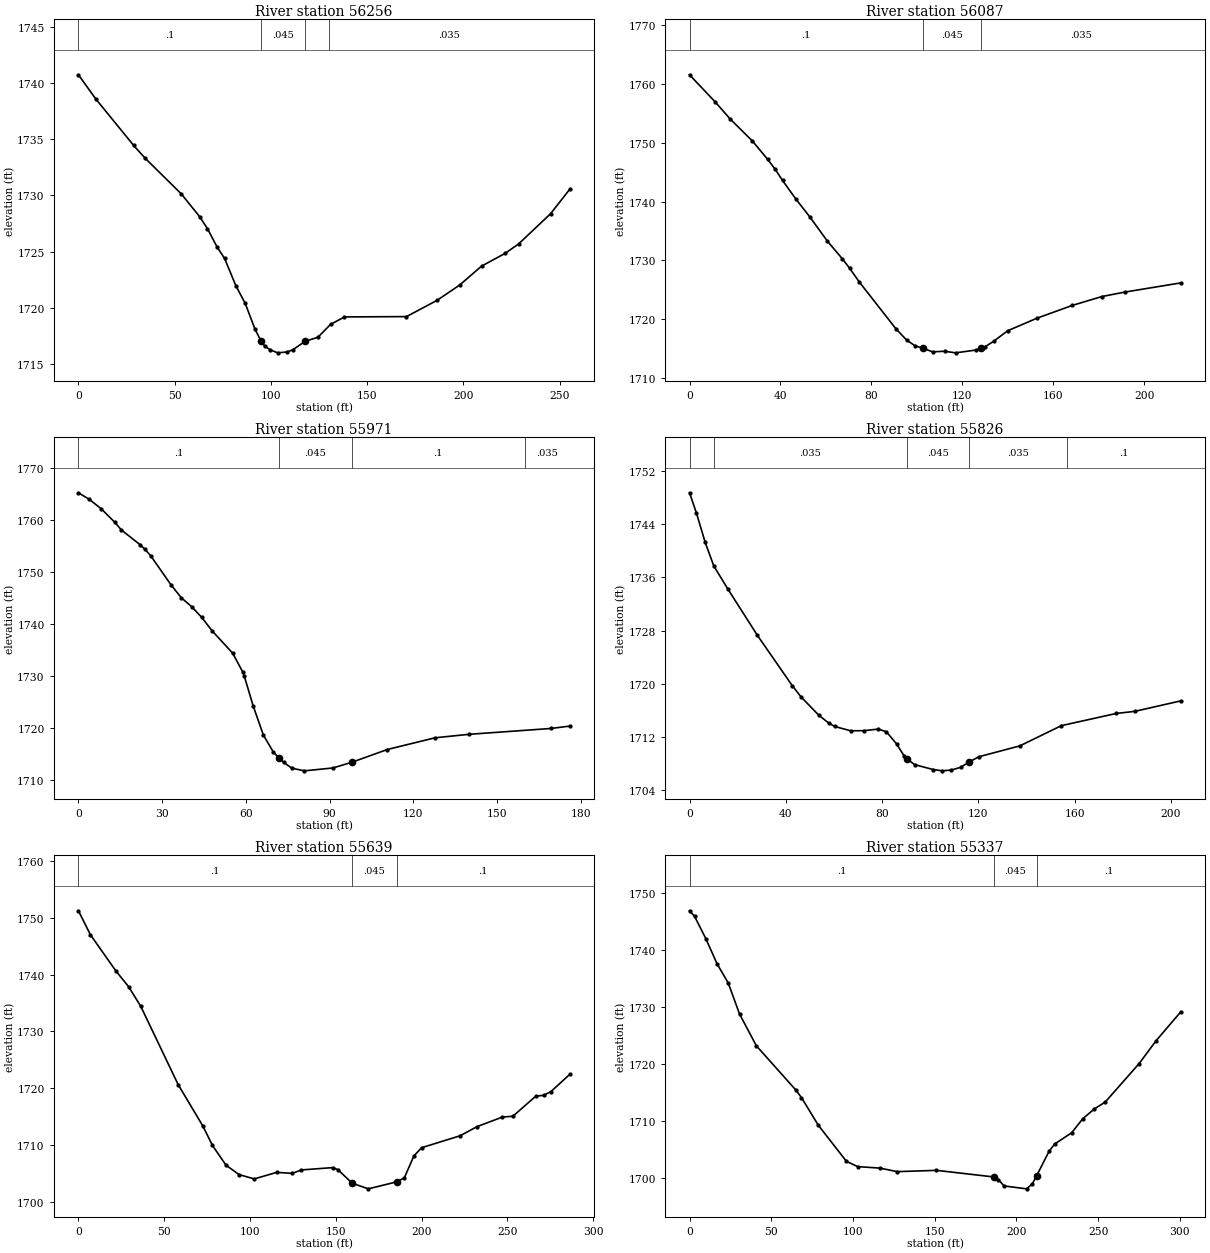
Type RM Length L Ch R = 1 ,56256   ,168.8,168.9,167.7
XS GIS Cut Line= 2
     2071472.223      227011.881     2071613.282      226799.207
#Sta/Elev= 30
       0 1740.75       9  1738.6    28.7 1734.45    34.5 1733.34    53.4 1730.14
    62.9 1728.12      67 1727.04      72 1725.41    75.9 1724.39    81.8 1721.94
    86.6 1720.39    91.7 1718.09    94.91717.007    96.7 1716.59    99.5 1716.25
   103.5 1715.97   108.5 1716.05   111.4 1716.25   117.81716.999   124.4 1717.36
     131 1718.51   138.2 1719.17   170.4  1719.2   186.2 1720.64     198 1722.01
   209.4  1723.7   221.6 1724.83   228.6 1725.67   245.2 1728.36   255.2 1730.55
#Mann= 4 ,-1 , 0
       0      .1       0    94.9    .045       0   117.8      .1       0
     130    .035       0
Bank Sta=94.9,117.8
XS Rating Curve= 0 ,0
Exp/Cntr=0.3,0.1

Type RM Length L Ch R = 1 ,56087   ,117.7,116.3,114
XS GIS Cut Line= 3
     2071661.025      227087.836      2071666.45       227005.37
     2071735.895      226891.438
#Sta/Elev= 30
       0 1761.56    11.3 1756.94    17.9 1754.03    27.7 1750.28    34.3 1747.21
    37.6 1745.53    40.9 1743.59    46.8 1740.41      53 1737.34    60.6 1733.28
    67.2 1730.27    70.5 1728.61    74.6 1726.35    90.7 1718.39    95.5 1716.43
    99.2 1715.46   102.51715.072   106.9 1714.43   112.2 1714.53     117 1714.26
   126.1 1714.74   128.21715.022   129.9 1715.27   133.7 1716.21   139.9 1718.01
   152.8 1720.15   168.3 1722.32   181.4 1723.84   191.4 1724.59   216.1 1726.16
#Mann= 3 ,-1 , 0
       0      .1       0   102.5    .045       0   128.2    .035       0
Bank Sta=102.5,128.2
XS Rating Curve= 0 ,0
Exp/Cntr=0.3,0.1

Type RM Length L Ch R = 1 ,55971   ,143,144.7,145.2
XS GIS Cut Line= 2
     2071744.575      227112.792     2071823.785      226955.457
#Sta/Elev= 30
       0 1765.29     3.8 1764.06     8.1 1762.25      13 1759.64    15.4 1758.14
    22.2 1755.27    23.9 1754.39    25.9 1753.19    33.2 1747.58    36.9  1745.1
    40.6  1743.4    44.2 1741.34    47.9 1738.77    55.3 1734.45    58.9 1730.84
    59.4 1730.14    62.6 1724.38    66.3 1718.71    69.9 1715.43      72 1714.27
    73.6 1713.47    76.5 1712.36      81 1711.85    91.2  1712.4    97.91713.477
   110.7 1715.95   127.8  1718.2     140 1718.87   169.3 1719.99   176.1 1720.45
#Mann= 4 ,-1 , 0
       0      .1       0      72    .045       0    97.9      .1       0
     160    .035       0
Bank Sta=72,97.9
XS Rating Curve= 0 ,0
Exp/Cntr=0.3,0.1

Type RM Length L Ch R = 1 ,55826   ,180.8,187,194.3
XS GIS Cut Line= 3
     2071828.126      227160.535     2071888.889      227132.323
     2071958.334      227014.051
#Sta/Elev= 30
       0 1748.72     2.9 1745.65     6.5 1741.27    10.1 1737.71    15.8 1734.32
    28.2 1727.28    42.7 1719.71    46.3 1718.04    53.6 1715.31    57.8  1714.1
    60.3 1713.58      67 1712.93    72.5 1712.95    78.4 1713.19    81.8 1712.78
      86 1710.96    89.2 1709.13    90.51708.644    93.6 1707.83   101.2 1707.11
     105 1706.91   108.8 1707.04   112.6 1707.43     116 1708.21   120.2 1709.03
   137.2 1710.66   154.5 1713.71   177.3 1715.54   184.9 1715.85   204.1 1717.43
#Mann= 5 ,-1 , 0
       0      .1       0      10    .035       0    90.5    .045       0
     116    .035       0  156.99      .1       0
Bank Sta=90.5,116
XS Rating Curve= 0 ,0
Exp/Cntr=0.3,0.1

Type RM Length L Ch R = 1 ,55639   ,291.4,301.8,308.8
XS GIS Cut Line= 3
     2071902.995      227325.466     2071973.525      227291.829
     2072127.605      227151.855
#Sta/Elev= 30
       0 1751.24       7 1747.01    21.8 1740.65    29.2 1737.88    36.3 1734.42
    58.1 1720.62    72.6 1713.26    78.1 1709.89      86 1706.41    93.6 1704.75
   102.5 1703.99   115.5 1705.14   124.6 1704.97   129.9 1705.57   148.1 1705.98
   151.2 1705.62   159.51703.238   168.9 1702.24   185.51703.476   189.9 1704.18
   195.5 1708.05     200 1709.49   222.4 1711.59   232.4 1713.22     247 1714.88
   253.2 1715.04   266.5 1718.57   271.1 1718.72   275.3 1719.37   286.3 1722.41
#Mann= 3 ,-1 , 0
       0      .1       0   159.5    .045       0   185.5      .1       0
Bank Sta=159.5,185.5
XS Rating Curve= 0 ,0
Exp/Cntr=0.3,0.1

Type RM Length L Ch R = 1 ,55337   ,273.3,267.1,265
XS GIS Cut Line= 2
     2072004.992      227512.098      2072291.45      227420.952
#Sta/Elev= 30
       0 1746.82     3.1 1745.84      10 1741.93    16.9 1737.51    23.7 1734.17
    30.6 1728.74    40.9 1723.17    65.1 1715.41    68.5  1714.1    78.8 1709.26
      96 1702.94   102.9 1702.01   116.6 1701.75     127 1701.13   151.1 1701.36
   186.31700.198     189 1699.75   192.4 1698.63   206.2 1698.12   209.7 1698.97
   212.41700.431     220 1704.71   223.4 1705.97   233.8 1707.94   240.6  1710.4
   247.5 1712.08   254.4 1713.34   275.1 1720.07   285.4 1724.04   300.6 1729.14
#Mann= 3 ,-1 , 0
       0      .1       0   186.3    .045       0   212.4      .1       0
Bank Sta=186.3,212.4
XS Rating Curve= 0 ,0
Exp/Cntr=0.3,0.1

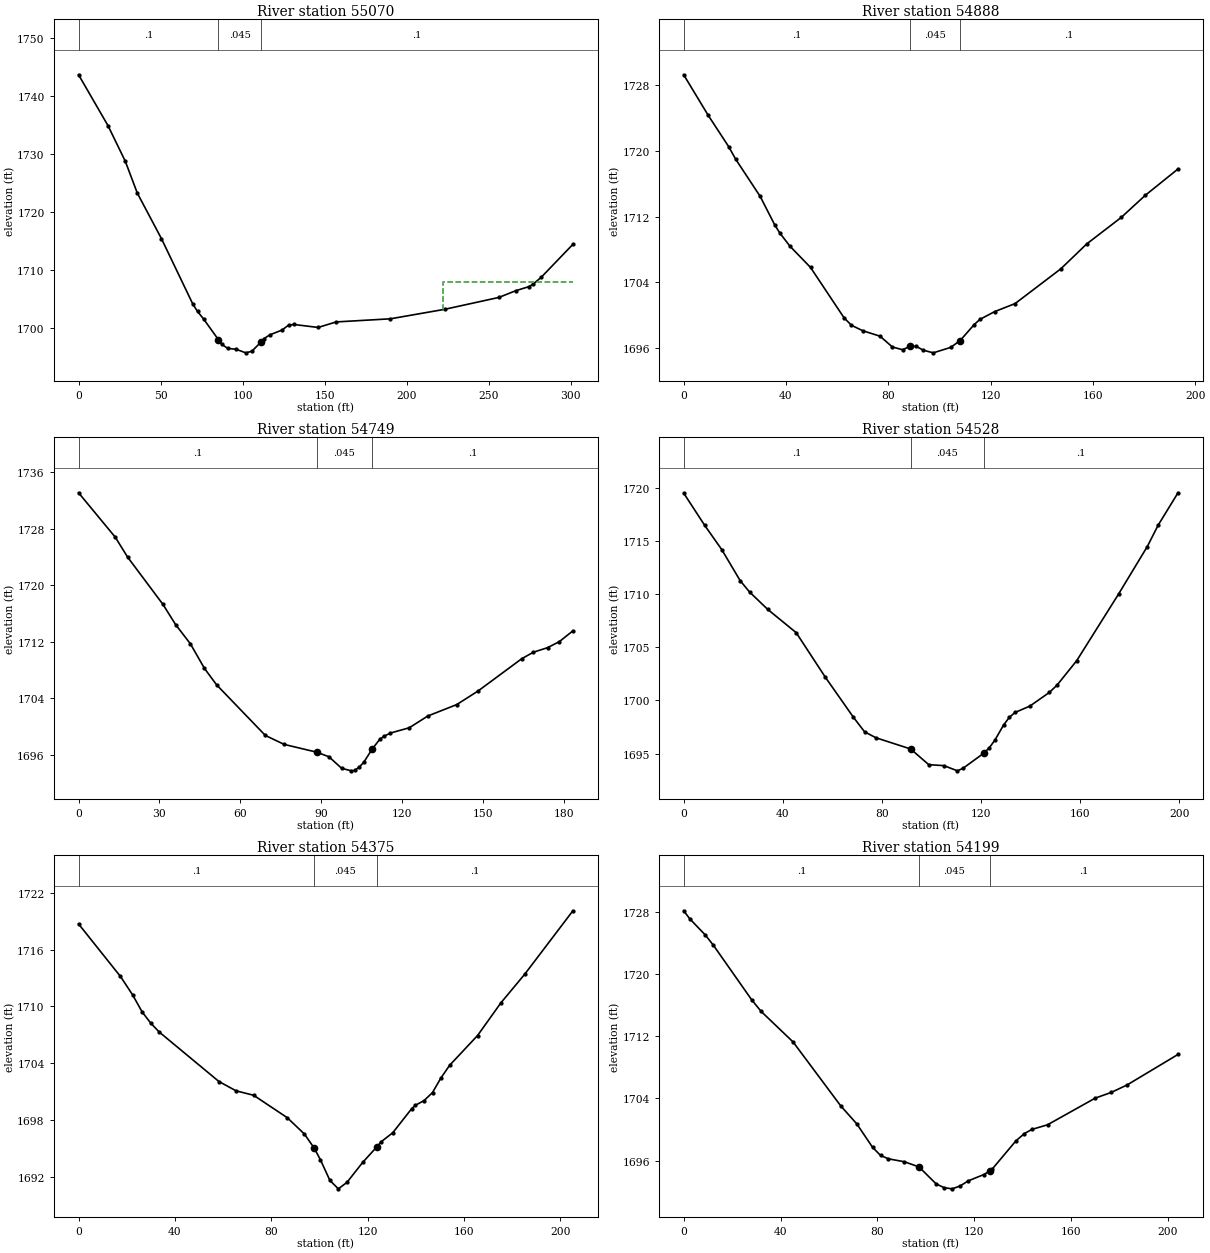
Type RM Length L Ch R = 1 ,55070   ,185.6,181.7,178.3
XS GIS Cut Line= 2
     2072080.947      227728.027     2072350.044      227592.393
#Sta/Elev= 30
       0 1743.67    17.9 1734.93    28.5 1728.77    35.8  1723.3    50.5 1715.47
    69.7 1704.16    72.5 1702.93    76.2 1701.63    85.21698.081    87.2  1697.3
    90.9 1696.56      96 1696.42   101.9  1695.8   105.6 1696.07   111.41697.712
   113.1 1698.26   116.6  1698.9     124 1699.72     128 1700.57   131.3 1700.68
     146 1700.17     157 1701.12   190.1 1701.66   223.1 1703.29   256.2 1705.34
   266.5  1706.5   274.4 1707.19   276.8 1707.57     282 1708.81   301.3 1714.48
#Mann= 3 ,-1 , 0
       0      .1       0    85.2    .045       0   111.4      .1       0
#XS Ineff= 2 , 0
                          222.09         1708.04
Permanent Ineff=
       F       F
Bank Sta=85.2,111.4
XS Rating Curve= 0 ,0
Exp/Cntr=0.3,0.1

Type RM Length L Ch R = 1 ,54888   ,142.8,139.7,136.4
XS GIS Cut Line= 2
      2072210.07      227871.256      2072368.49      227760.579
#Sta/Elev= 30
       0 1729.23     9.6 1724.29    17.6 1720.49    20.3 1718.98    29.9 1714.45
    35.6 1710.98    37.6 1709.99    41.5 1708.41    49.6 1705.81    62.7 1699.69
    65.6 1698.78      70 1698.12    76.8 1697.45    81.6 1696.14    85.6 1695.81
    88.41696.207      91 1696.21    93.6 1695.76    97.6 1695.43   104.4 1696.09
   108.11696.921   113.6 1698.87   115.9 1699.51   121.6 1700.44   129.6 1701.42
   147.5 1705.65   157.6 1708.67   171.1 1711.89   180.5 1714.58   193.3 1717.78
#Mann= 3 ,-1 , 0
       0      .1       0    88.4    .045       0   108.1      .1       0
Bank Sta=88.4,108.1
XS Rating Curve= 0 ,0
Exp/Cntr=0.3,0.1

Type RM Length L Ch R = 1 ,54749   ,214.4,220.8,216.9
XS GIS Cut Line= 2
     2072299.046      227993.869     2072431.424      227866.915
#Sta/Elev= 30
       0 1733.12    13.6 1726.84    18.2 1724.01    31.3 1717.32      36 1714.46
    41.5 1711.73    46.7 1708.26    51.2 1705.93    69.3 1698.76    76.3 1697.49
    88.41696.388    92.9 1695.74    97.6 1694.11   101.2 1693.75   102.4  1693.8
   104.1 1694.27   105.8 1694.95   108.91696.818   111.8 1698.24   113.4 1698.66
   115.7  1699.1   122.7 1699.85   129.6 1701.52   140.3 1703.13   148.2 1705.05
   164.4 1709.62   168.7 1710.54     174 1711.19   178.4 1712.05   183.4 1713.57
#Mann= 3 ,-1 , 0
       0      .1       0    88.4    .045       0   108.9      .1       0
Bank Sta=88.4,108.9
XS Rating Curve= 0 ,0
Exp/Cntr=0.3,0.1

Type RM Length L Ch R = 1 ,54528   ,138,152.4,153.6
XS GIS Cut Line= 2
     2072455.296      228109.971     2072594.185      227966.742
#Sta/Elev= 30
       0  1719.5     8.4 1716.49    15.4 1714.17    22.8 1711.26    26.6 1710.19
    33.9 1708.56    45.4 1706.37    57.1  1702.2    68.5 1698.41      73 1697.04
    77.6 1696.48    91.61695.425    98.9 1693.95     105 1693.86   110.5 1693.37
   112.8 1693.62     1211695.012   123.3 1695.53   125.6 1696.26   129.1 1697.68
   131.4  1698.4   133.7 1698.86   139.7 1699.46   147.6 1700.75   150.7 1701.44
   158.6 1703.73   175.5    1710   187.1 1714.47   191.5 1716.49   199.5 1719.53
#Mann= 3 ,-1 , 0
       0      .1       0    91.6    .045       0     121      .1       0
Bank Sta=91.6,121
XS Rating Curve= 0 ,0
Exp/Cntr=0.3,0.1

Type RM Length L Ch R = 1 ,54375   ,166.4,176,177.3
XS GIS Cut Line= 2
     2072508.464      228177.245     2072698.351       228099.12
#Sta/Elev= 30
       0  1718.7    17.4 1713.16    22.4 1711.24    26.4 1709.42      30 1708.23
    33.5  1707.3    58.3 1702.08    65.4  1701.1    72.7 1700.63    86.7 1698.26
    93.8 1696.54    97.8 1695.08   100.4 1693.85   104.4 1691.64   107.9 1690.76
   111.5 1691.45     118 1693.55   123.81695.168   125.7 1695.73   130.5 1696.68
   138.3  1699.2   139.9 1699.58   143.5 1700.07     147 1700.92   150.4 1702.42
   154.1 1703.79   165.7 1706.93   175.4 1710.38   185.3  1713.4   205.3 1720.09
#Mann= 3 ,-1 , 0
       0      .1       0    97.8    .045       0   123.8      .1       0
Bank Sta=97.8,123.8
XS Rating Curve= 0 ,0
Exp/Cntr=0.3,0.1

Type RM Length L Ch R = 1 ,54199   ,92.2,88.5,85.2
XS GIS Cut Line= 2
     2072513.995      228301.191     2072717.882      228290.093
#Sta/Elev= 30
       0 1728.13     2.5  1727.1       9 1724.99    12.3 1723.68    28.1 1716.67
      32 1715.18    45.2 1711.25    64.9 1703.02    71.5 1700.72      78 1697.71
    81.3 1696.66    84.6 1696.22    91.2 1695.84    97.2 1695.18   104.3 1692.99
   107.6 1692.51   110.9 1692.36   114.2 1692.73   117.5 1693.38     124  1694.2
   126.41694.658   127.3 1694.85   137.2 1698.52   140.7 1699.46   143.8    1700
   150.3  1700.6     170 1704.03   176.6 1704.76   183.2 1705.73   204.2 1709.65
#Mann= 3 ,-1 , 0
       0      .1       0    97.2    .045       0   126.4      .1       0
Bank Sta=97.2,126.4
XS Rating Curve= 0 ,0
Exp/Cntr=0.3,0.1

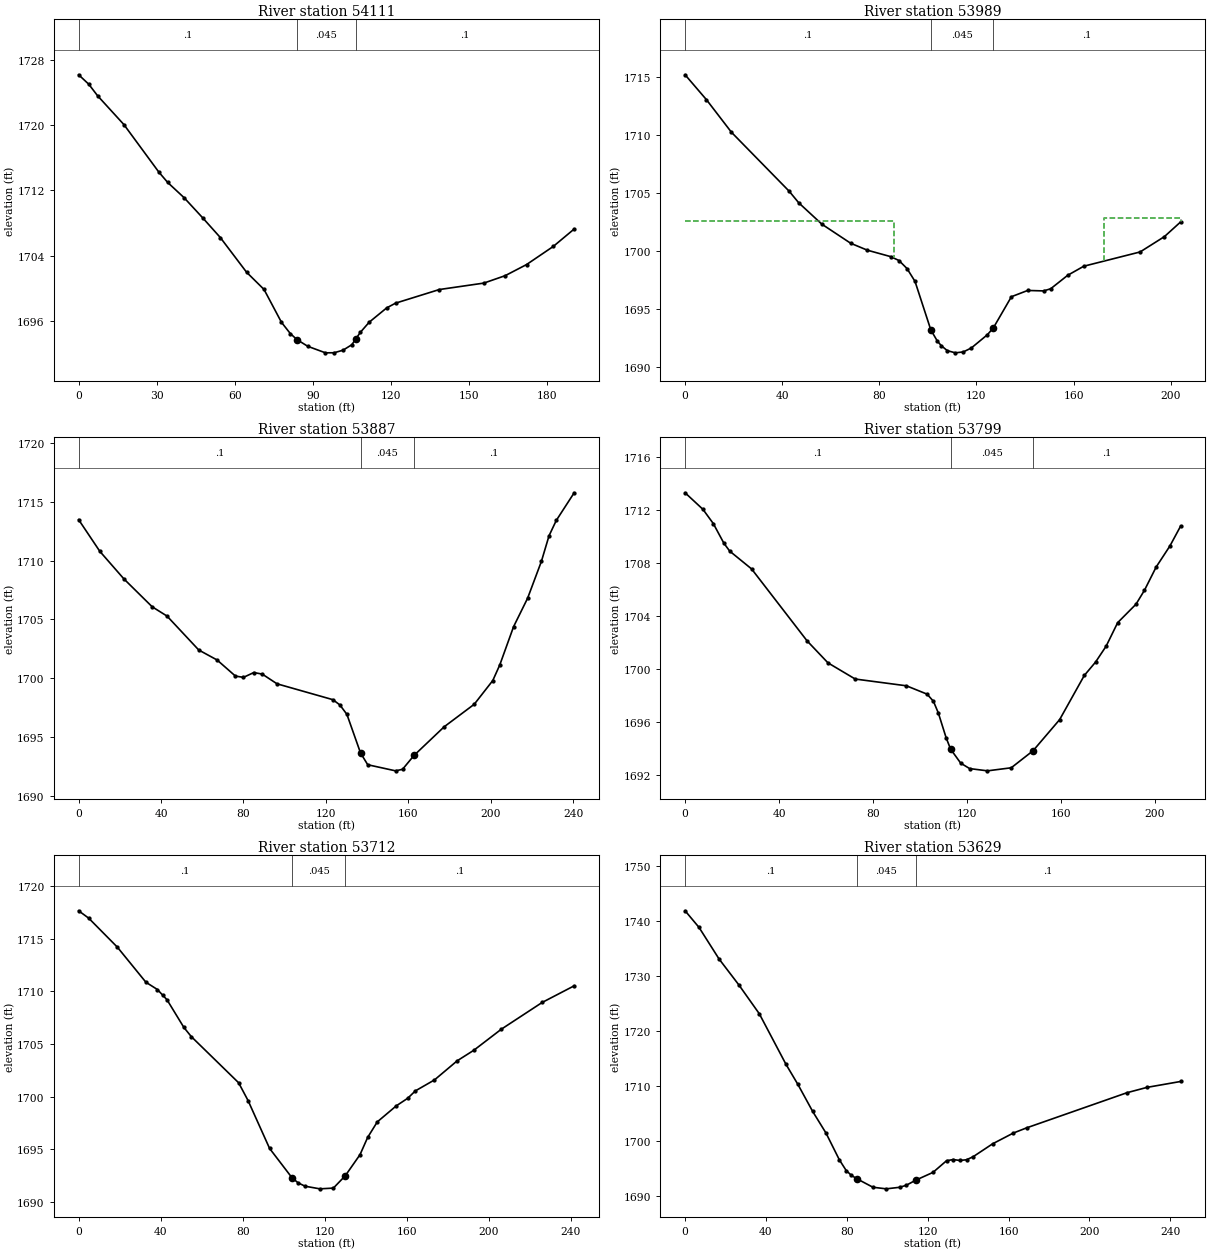
Type RM Length L Ch R = 1 ,54111   ,119.6,121.9,123.2
XS GIS Cut Line= 2
     2072532.336      228404.025     2072717.882      228361.707
#Sta/Elev= 30
       0 1726.18     3.9 1725.02     7.3  1723.6    17.4 1720.07    30.8 1714.25
    34.2 1712.98    40.5 1711.11    47.7 1708.62    54.4 1706.23    64.5 1701.97
    71.2 1699.86    77.9 1695.83    81.3 1694.45    83.91693.702      88 1692.89
    94.8 1692.09    98.1  1692.1   101.5 1692.41   104.9 1693.08   106.41693.775
   108.2 1694.61   111.6 1695.85   118.3  1697.6   121.7 1698.18   138.5 1699.85
   155.6 1700.64   163.8 1701.55     172 1702.91   182.3 1705.14   190.3 1707.27
#Mann= 3 ,-1 , 0
       0      .1       0    83.9    .045       0   106.4      .1       0
Bank Sta=83.9,106.4
XS Rating Curve= 0 ,0
Exp/Cntr=0.3,0.1

Type RM Length L Ch R = 1 ,53989   ,93.7,102,110.6
XS GIS Cut Line= 3
     2072536.676       228477.81     2072583.334      228509.277
     2072729.818      228489.745
#Sta/Elev= 30
       0 1715.19     8.8 1713.04    19.1 1710.23    42.9 1705.14    46.8 1704.15
    56.3 1702.31    68.2 1700.66    75.1 1700.06    84.8  1699.5    88.1 1699.17
    91.4 1698.48    94.7 1697.37   101.21693.192   103.9 1692.22   105.6 1691.81
     108  1691.4   111.3 1691.21   114.6 1691.29   117.9 1691.63   124.5 1692.77
     1271693.376   134.4 1696.05   141.1 1696.59   147.7 1696.55   150.6 1696.74
   157.6  1697.9   164.2 1698.68   187.4 1699.91   197.4 1701.23   204.1  1702.5
#Mann= 3 ,-1 , 0
       0      .1       0   101.2    .045       0     127      .1       0
#XS Ineff= 2 , 0
           85.86 1702.54  172.73         1702.81
Permanent Ineff=
       F       F
Bank Sta=101.2,127
XS Rating Curve= 0 ,0
Exp/Cntr=0.3,0.1

Type RM Length L Ch R = 1 ,53887   ,68.2,87.7,107.3
XS GIS Cut Line= 3
     2072512.804      228522.297     2072589.844      228592.827
     2072722.223      228624.294
#Sta/Elev= 30
       0  1713.5    10.3  1710.8      22 1708.45    35.7 1706.08    42.9 1705.29
    58.3  1702.4    67.2 1701.55    76.1 1700.18      80 1700.07      85 1700.48
    89.1 1700.35    96.3 1699.52   123.4 1698.17   126.8 1697.72   130.2 1696.92
   136.81693.639   140.3 1692.63   153.8 1692.11   157.2 1692.24   162.81693.427
   177.4 1695.86     192 1697.78     201  1699.8   204.4 1701.13   211.1 1704.39
   217.9 1706.81   224.6 1709.95   228.3 1712.13   231.8 1713.43   240.5 1715.79
#Mann= 3 ,-1 , 0
       0      .1       0   136.8    .045       0   162.8      .1       0
Bank Sta=136.8,162.8
XS Rating Curve= 0 ,0
Exp/Cntr=0.3,0.1

Type RM Length L Ch R = 1 ,53799   ,91.5,87.1,81.2
XS GIS Cut Line= 4
     2072491.103      228571.126     2072558.377      228631.889
     2072602.865      228705.674     2072629.992       228726.29
#Sta/Elev= 30
       0 1713.31     7.6 1712.06      12 1710.99    16.5 1709.51      19 1708.91
    28.3 1707.57    51.9 1702.15    60.8 1700.49    72.4 1699.27    94.2 1698.76
     103 1698.13   105.7 1697.59   107.8  1696.7   111.1 1694.84     1131693.986
   117.3 1692.93   121.1 1692.52   128.7 1692.35   138.8 1692.58   148.11693.866
   159.4 1696.21   169.9 1699.54   174.7 1700.55   179.2 1701.75   184.1 1703.52
   191.9 1704.91   195.5 1705.96   200.5 1707.72   206.3 1709.29   210.9  1710.8
#Mann= 3 ,-1 , 0
       0      .1       0     113    .045       0   148.1      .1       0
Bank Sta=113,148.1
XS Rating Curve= 0 ,0
Exp/Cntr=0.3,0.1

Type RM Length L Ch R = 1 ,53712   ,97.6,83.4,66.1
XS GIS Cut Line= 3
     2072418.403      228621.039     2072545.356      228746.907
     2072607.205      228757.757
#Sta/Elev= 30
       0 1717.65     4.9 1716.95    18.9 1714.19    32.8 1710.86    38.4 1710.17
    41.1 1709.61    43.1 1709.19    51.3 1706.57    54.9  1705.7      78 1701.31
    82.6 1699.62    93.1 1695.07     104 1692.29     107  1691.8   110.4 1691.48
   117.6 1691.23   124.2  1691.3     1301692.473   137.2 1694.48   140.9 1696.11
   145.6 1697.59   154.9 1699.12   160.4 1699.83   164.2 1700.54   173.5 1701.58
   184.6  1703.4   192.7  1704.4   206.1  1706.4     226 1708.94   241.6 1710.52
#Mann= 3 ,-1 , 0
       0      .1       0     104    .045       0     130      .1       0
Bank Sta=104,130
XS Rating Curve= 0 ,0
Exp/Cntr=0.3,0.1

Type RM Length L Ch R = 1 ,53629   ,104.6,97.6,90.5
XS GIS Cut Line= 3
      2072361.98      228759.928     2072533.421      228781.629
     2072605.035      228771.863
#Sta/Elev= 30
       0 1741.93     6.9  1738.9    16.8 1733.16    26.7 1728.39    36.7  1723.2
    49.9    1714    55.8 1710.34    63.1 1705.43    69.7 1701.49    76.3 1696.63
    79.7 1694.67    82.2 1693.82    84.81693.215    92.9 1691.64    99.5 1691.35
   106.1 1691.63   109.4    1692   114.11692.929   122.6 1694.34   129.3 1696.46
   132.6 1696.68   135.9 1696.51   139.2 1696.64   142.5  1697.2   152.1 1699.54
   162.3 1701.49   168.9 1702.44   218.6 1708.84   228.5 1709.81   245.1 1710.88
#Mann= 3 ,-1 , 0
       0      .1       0    84.8    .045       0   114.1      .1       0
Bank Sta=84.8,114.1
XS Rating Curve= 0 ,0
Exp/Cntr=0.3,0.1

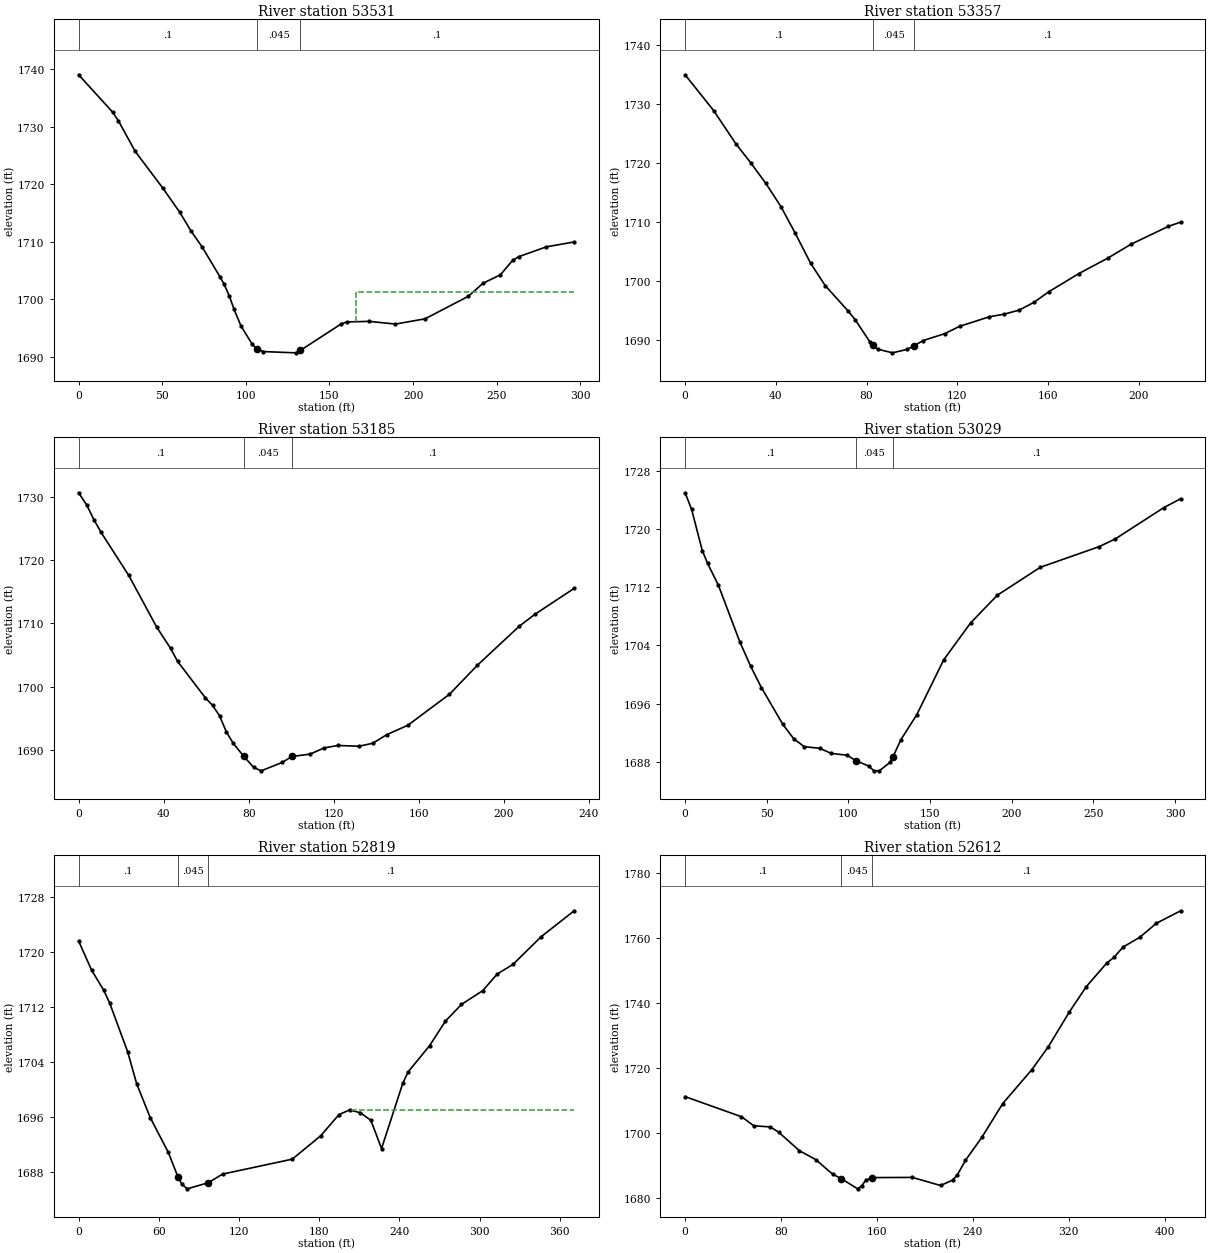
Type RM Length L Ch R = 1 ,53531   ,205.4,174.8,146
XS GIS Cut Line= 3
     2072338.847      228890.019     2072513.889      228858.669
      2072603.95      228781.629
#Sta/Elev= 30
       0 1739.07    20.5 1732.51    23.8 1731.04    33.8 1725.74    50.5 1719.27
    60.5 1715.11    67.1 1711.91    73.8 1709.11    84.5  1703.9    86.9 1702.65
    90.1 1700.56    92.9 1698.26    97.1 1695.32   103.8 1692.14   106.71691.307
   110.4 1690.87   129.7 1690.65   132.61691.075   157.1 1695.71   160.4 1696.03
   173.8 1696.13   189.4 1695.66   207.1 1696.57     233 1700.49   241.7 1702.75
   252.2 1704.24   259.5 1706.76   263.2  1707.4   279.7 1709.11   296.3 1709.96
#Mann= 3 ,-1 , 0
       0      .1       0   106.7    .045       0   132.6      .1       0
#XS Ineff= 2 , 0
                          165.76         1701.17
Permanent Ineff=
       F       F
Bank Sta=106.7,132.6
XS Rating Curve= 0 ,0
Exp/Cntr=0.3,0.1

Type RM Length L Ch R = 1 ,53357   ,172.1,171.9,171.3
XS GIS Cut Line= 2
     2072602.865      229008.409     2072613.716       228790.31
#Sta/Elev= 30
       0 1734.96    12.6 1728.88    22.4 1723.24      29 1719.99    35.6 1716.52
    42.2 1712.61    48.5 1708.11    55.3 1702.99    61.8 1699.17    71.7 1694.94
      75 1693.39    81.6 1689.54      831689.046    84.8 1688.41    91.4 1687.78
      98 1688.38     1011688.986   104.8 1689.85   114.4 1691.03     121 1692.28
   134.1  1693.9   140.7 1694.35   147.3 1695.04   153.8 1696.36   160.4 1698.17
   173.6 1701.24   186.2 1703.83   196.5  1706.2     213 1709.24   218.4 1709.96
#Mann= 3 ,-1 , 0
       0      .1       0      83    .045       0     101      .1       0
Bank Sta=83,101
XS Rating Curve= 0 ,0
Exp/Cntr=0.3,0.1

Type RM Length L Ch R = 1 ,53185   ,154.2,155.8,155.6
XS GIS Cut Line= 2
     2072777.127      228996.473     2072781.556      228763.283
#Sta/Elev= 30
       0 1730.71     3.9 1728.71     7.2 1726.44    10.5 1724.47    23.6  1717.6
    36.7 1709.44    43.3 1706.03    46.6 1703.97    59.7 1698.19      63 1697.01
    66.3 1695.38    69.5 1692.83    72.8 1690.98    77.71688.947    82.4 1687.18
    85.9 1686.64    95.8 1687.97   100.4 1688.92   108.9 1689.29   115.5 1690.27
     122 1690.66   131.9 1690.54   138.4 1691.01     145 1692.37   154.9 1693.86
   174.5 1698.77   187.7 1703.39   207.4 1709.57   214.9 1711.49   233.2 1715.56
#Mann= 3 ,-1 , 0
       0      .1       0    77.7    .045       0   100.4      .1       0
Bank Sta=77.7,100.4
XS Rating Curve= 0 ,0
Exp/Cntr=0.3,0.1

Type RM Length L Ch R = 1 ,53029   ,211.9,210.1,198.8
XS GIS Cut Line= 2
     2072922.961      228989.962     2072937.806      228686.894
#Sta/Elev= 30
       0 1724.95       4 1722.67    10.5 1717.02    13.8 1715.24    20.4 1712.25
    33.5 1704.48    40.1 1701.15    46.7 1698.21    59.8 1693.16    66.4 1691.21
    72.9 1690.09    82.4 1689.87    89.4 1689.17    99.2 1688.91   104.41688.179
   112.4 1687.43   115.6 1686.78   118.9 1686.77   125.5 1687.94   127.21688.655
   132.1 1691.04   141.9  1694.5   158.3    1702   174.8 1707.08   191.2 1710.89
   217.5 1714.72   253.6 1717.56   263.5 1718.63     293  1722.9   303.4 1724.13
#Mann= 3 ,-1 , 0
       0      .1       0   104.4    .045       0   127.2      .1       0
Bank Sta=104.4,127.2
XS Rating Curve= 0 ,0
Exp/Cntr=0.3,0.1

Type RM Length L Ch R = 1 ,52819   ,192.2,207.1,217.6
XS GIS Cut Line= 3
     2073139.974      228988.877     2073097.657      228816.351
     2072988.153       228657.38
#Sta/Elev= 30
       0 1721.59     9.7 1717.36    18.8 1714.43    23.2 1712.59    36.7 1705.49
    43.5 1700.81    53.6 1695.93    67.1 1690.89    74.31687.329    77.3 1686.27
    81.2  1685.6    96.91686.483   107.7 1687.74   159.8 1689.91     181 1693.29
   194.7 1696.37   202.7 1697.06   210.7 1696.65   218.6 1695.56   226.6 1691.45
   242.5 1700.94   246.5 1702.59   262.5 1706.38   274.4 1709.96   286.4 1712.38
   302.3 1714.38   313.1 1716.79   324.9 1718.19   346.1 1722.23   370.7 1725.98
#Mann= 3 ,-1 , 0
       0      .1       0    74.3    .045       0    96.9      .1       0
#XS Ineff= 2 , 0
                          204.79         1697.03
Permanent Ineff=
       F       F
Bank Sta=74.3,96.9
XS Rating Curve= 0 ,0
Exp/Cntr=0.3,0.1

Type RM Length L Ch R = 1 ,52612   ,198.7,224.4,239.4
XS GIS Cut Line= 2
     2073262.587      228978.027     2073394.403      228586.199
#Sta/Elev= 30
       0 1711.15      47 1704.96    57.3 1702.18    71.2 1701.81    78.1 1700.18
    95.4 1694.49   108.9 1691.78   123.1 1687.27   130.21685.927   143.9 1682.76
   147.3  1683.7   150.8 1685.43   156.21686.218   189.5 1686.28   213.1 1683.79
   223.1 1685.43     227 1686.98   233.9 1691.53   247.7 1698.69     265 1709.02
   289.3 1719.46   303.1 1726.55   320.4 1737.12   334.5  1744.9   351.6 1752.21
   357.8 1754.02   365.4  1757.2   379.3 1760.18   393.1 1764.49   413.4 1768.35
#Mann= 3 ,-1 , 0
       0      .1       0   130.2    .045       0   156.2      .1       0
Bank Sta=130.2,156.2
XS Rating Curve= 0 ,0
Exp/Cntr=0.3,0.1

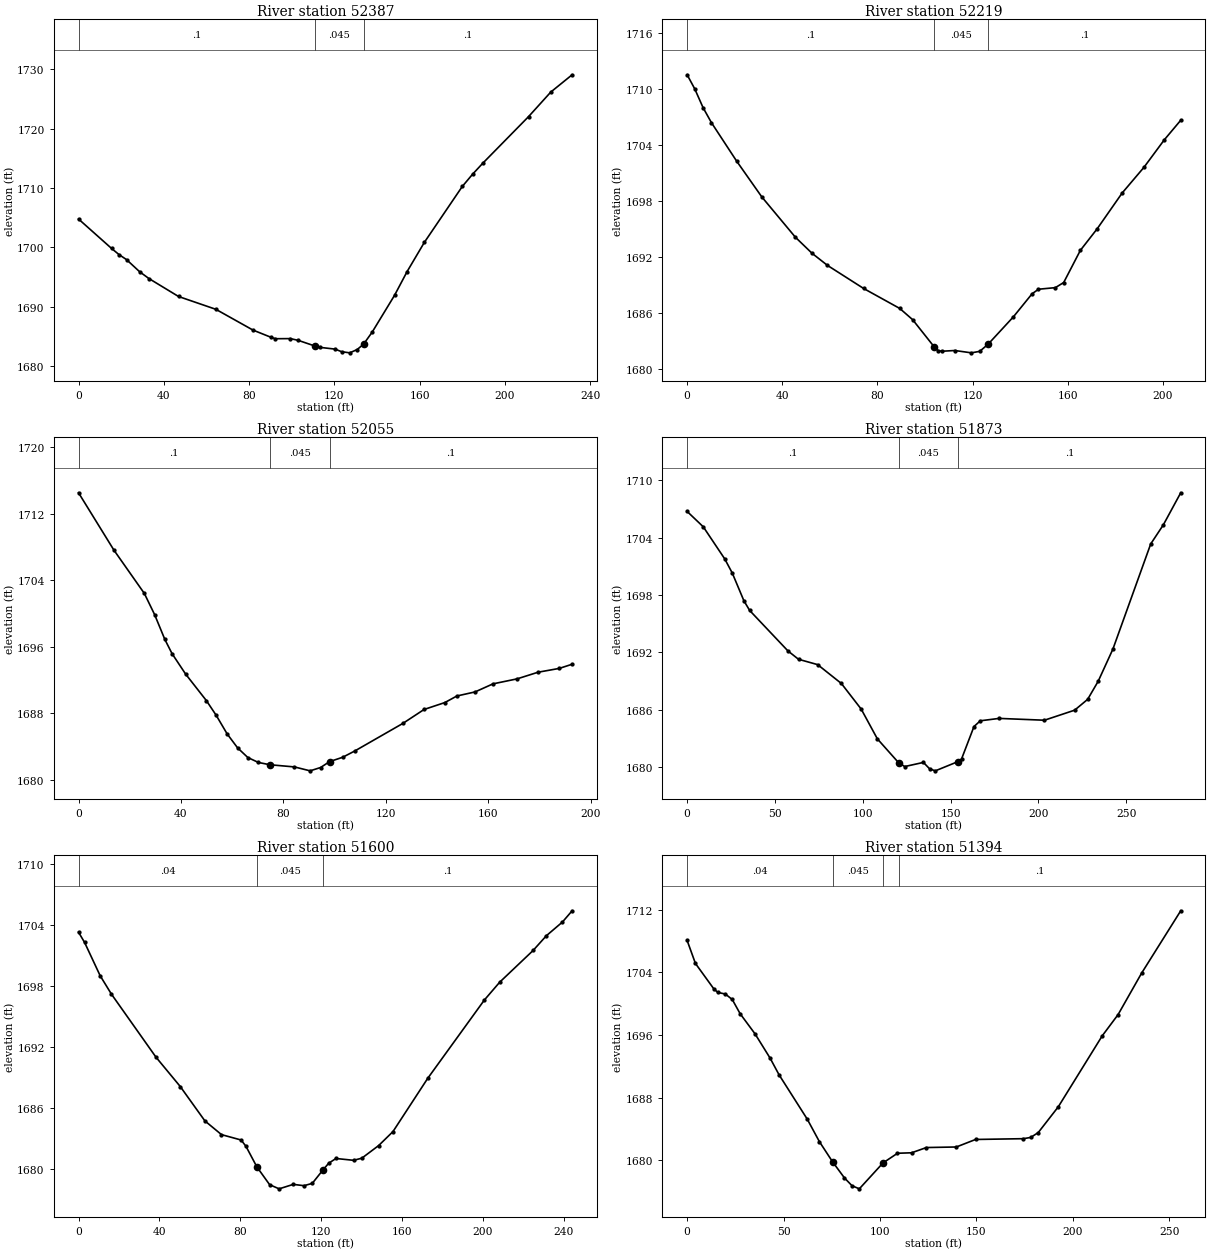
Type RM Length L Ch R = 1 ,52387   ,167.3,168.7,166.2
XS GIS Cut Line= 2
     2073341.797      229021.429     2073559.334      228942.102
#Sta/Elev= 30
       0 1704.76    15.5  1699.8      19 1698.76    22.5 1697.92    28.7 1695.86
      33 1694.73    46.9  1691.7    64.4 1689.54    81.8 1686.04    90.2 1684.83
    92.3 1684.58    99.3  1684.6     103 1684.31   110.91683.346   113.3 1683.12
   120.3 1682.83   123.4 1682.39   127.2  1682.2   130.7 1682.76   133.7 1683.67
   137.7 1685.68   148.2 1691.89   154.1  1695.9   162.2 1700.83     180 1710.26
   184.8 1712.31   189.6 1714.17   211.1 1722.04   221.5 1726.17   231.5 1729.08
#Mann= 3 ,-1 , 0
       0      .1       0   110.9    .045       0   133.7      .1       0
Bank Sta=110.9,133.7
XS Rating Curve= 0 ,0
Exp/Cntr=0.3,0.1

Type RM Length L Ch R = 1 ,52219   ,173.5,163.8,147.9
XS GIS Cut Line= 2
     2073396.051      229180.935     2073589.193       229104.98
#Sta/Elev= 30
       0 1711.49     3.2 1709.98     6.7 1707.97    10.2 1706.37    20.8 1702.25
    31.4 1698.41    45.5  1694.1    52.5 1692.38      59 1691.08    74.2 1688.61
    89.4 1686.47    94.8 1685.27   103.81682.379   105.4 1681.97   107.1 1681.89
   112.5 1681.97   119.5 1681.72     123 1681.88   126.51682.638   137.1 1685.56
     145 1688.04   147.7 1688.53   154.8  1688.7   158.3 1689.25   165.3 1692.69
   172.4 1695.01   182.9 1698.84     192 1701.57   200.6 1704.53   207.5 1706.62
#Mann= 3 ,-1 , 0
       0      .1       0   103.8    .045       0   126.5      .1       0
Bank Sta=103.8,126.5
XS Rating Curve= 0 ,0
Exp/Cntr=0.3,0.1

Type RM Length L Ch R = 1 ,52055   ,185,181.8,173.9
XS GIS Cut Line= 2
     2073515.409       229351.29     2073628.256       229195.04
#Sta/Elev= 30
       0 1714.54    13.8 1707.65    25.7 1702.43    29.7 1699.89    33.7  1696.9
    36.5  1695.2    41.8 1692.74    49.9 1689.55    53.7  1687.8      58 1685.55
    62.1 1683.86    66.1  1682.7    70.2 1682.11    74.71681.833    84.3 1681.57
    90.4  1681.1    94.5  1681.5      981682.207   103.1 1682.73   107.8 1683.48
   126.6  1686.8   134.9 1688.48     143 1689.31   147.7  1690.1   154.8 1690.59
   161.8 1691.56   171.2 1692.16   179.4 1692.96   187.7 1693.42   192.7 1693.92
#Mann= 3 ,-1 , 0
       0      .1       0    74.7    .045       0      98      .1       0
Bank Sta=74.7,98
XS Rating Curve= 0 ,0
Exp/Cntr=0.3,0.1

Type RM Length L Ch R = 1 ,51873   ,266,272.9,265.8
XS GIS Cut Line= 3
      2073622.83      229452.202     2073685.764      229444.606
      2073774.74      229246.039
#Sta/Elev= 30
       0 1706.74     9.2 1705.13    21.4 1701.78    25.7  1700.3    32.3 1697.41
    35.6 1696.39    57.4 1692.16    63.4 1691.29    74.3 1690.73    87.8 1688.76
    99.1 1686.08   108.3 1682.97   120.51680.456   123.9 1680.08   134.5 1680.51
   138.1 1679.83   141.3 1679.63   154.31680.604   156.2 1680.86   163.3 1684.26
   166.9 1684.86   177.6 1685.11   203.4 1684.92   220.6 1685.97     228  1687.1
     234 1688.99   242.4 1692.36   263.9 1703.34   271.1 1705.34     281 1708.69
#Mann= 3 ,-1 , 0
       0      .1       0   120.5    .045       0   154.3      .1       0
Bank Sta=120.5,154.3
XS Rating Curve= 0 ,0
Exp/Cntr=0.3,0.1

Type RM Length L Ch R = 1 ,51600   ,205.4,206.6,197.2
XS GIS Cut Line= 3
     2073832.249      229633.409     2073942.926      229483.669
     2073949.436       229426.16
#Sta/Elev= 30
       0 1703.31       3  1702.3    10.7 1699.02    16.3  1697.2    38.3    1691
    50.3 1688.11    62.5 1684.72    70.7 1683.37    80.4 1682.84    82.8 1682.22
    88.2 1680.19    94.5 1678.44    99.2 1678.03   106.2 1678.47   111.5 1678.34
   115.6 1678.57   120.91679.896   123.7 1680.55   127.3 1681.02     136 1680.84
   140.1 1681.05   148.4 1682.29   155.5 1683.67   172.7 1688.92   200.7 1696.63
   208.3 1698.39   224.8 1701.51   231.4 1702.97   239.3 1704.31   244.1 1705.42
#Mann= 3 ,-1 , 0
       0     .04       0    88.2    .045       0   120.9      .1       0
Bank Sta=88.2,120.9
XS Rating Curve= 0 ,0
Exp/Cntr=0.3,0.1

Type RM Length L Ch R = 1 ,51394   ,224.3,240.6,246.4
XS GIS Cut Line= 3
      2074003.69      229721.299     2074111.112      229548.773
     2074153.429      229517.306
#Sta/Elev= 30
       0 1708.05     4.3 1705.12    13.8 1701.89    15.9 1701.42    19.8 1701.22
    23.4 1700.52    27.5  1698.7    35.2 1696.14      43 1693.05    47.7  1690.9
    62.3 1685.25    68.6 1682.38    75.41679.818    81.6 1677.75    85.5 1676.76
    89.3 1676.36   101.61679.668   109.1  1680.9   116.4 1680.96   124.1 1681.63
   139.6  1681.7   149.6 1682.66   174.4 1682.76   178.2 1682.92   182.1 1683.54
   192.5 1686.83   215.3 1695.89   223.5 1698.59   235.7 1703.88     256 1711.84
#Mann= 4 ,-1 , 0
       0     .04       0    75.4    .045       0   101.6     .04       0
     110      .1       0
Bank Sta=75.4,101.6
XS Rating Curve= 0 ,0
Exp/Cntr=0.3,0.1