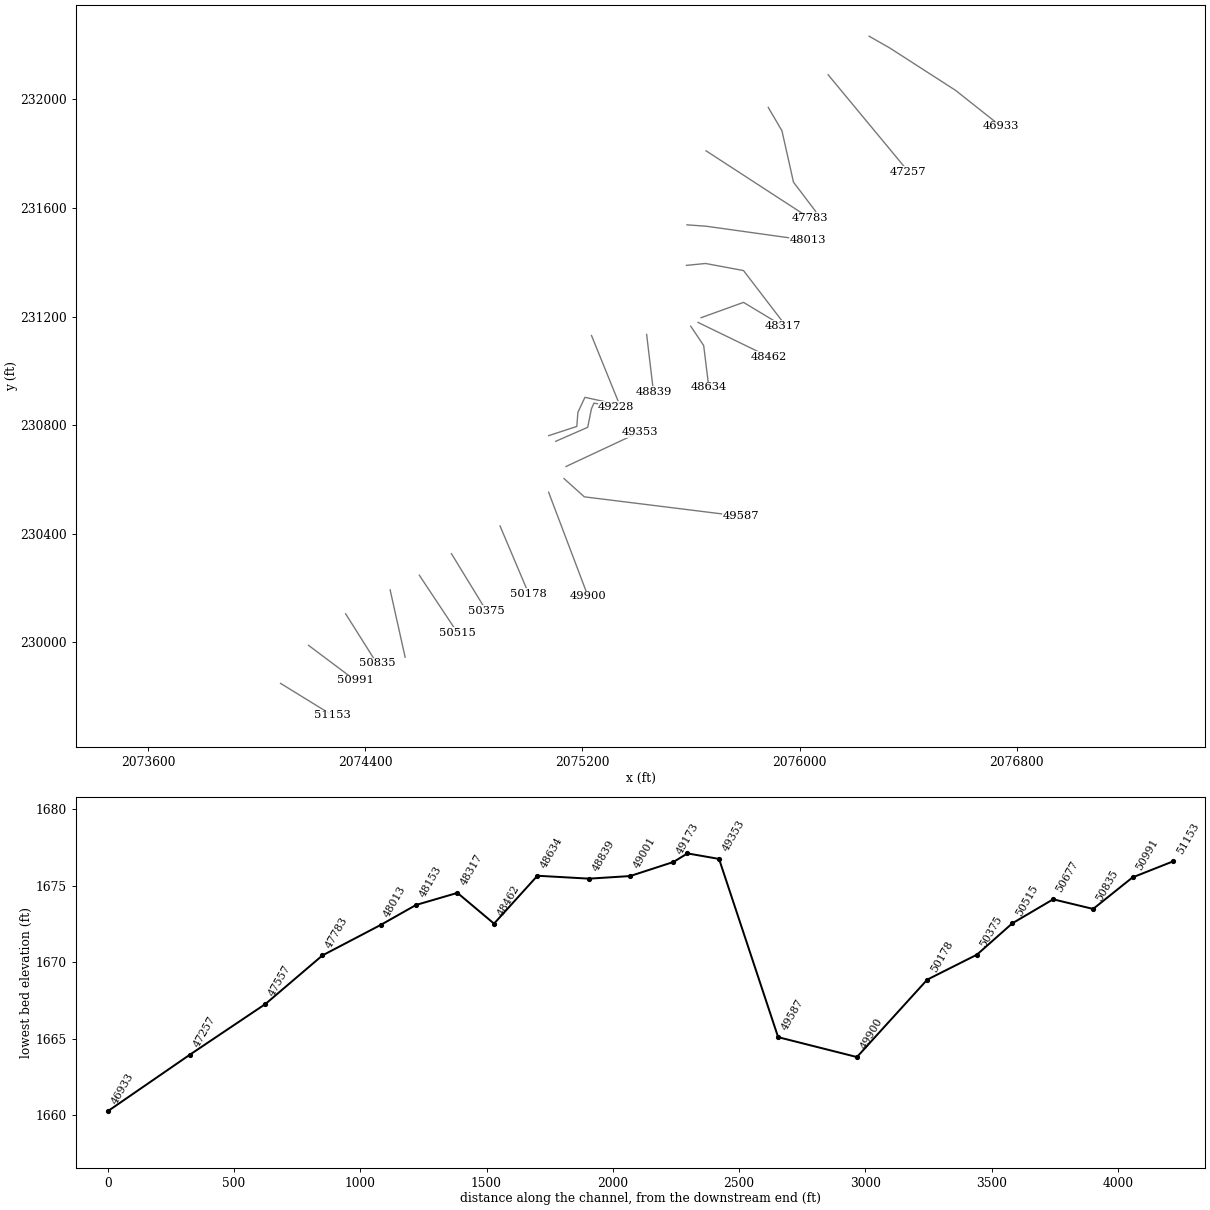
HEC-RAS study WOLFCK.prj: WOLFCK

--- WOLFCK.g01 (geometry) --- (continued)

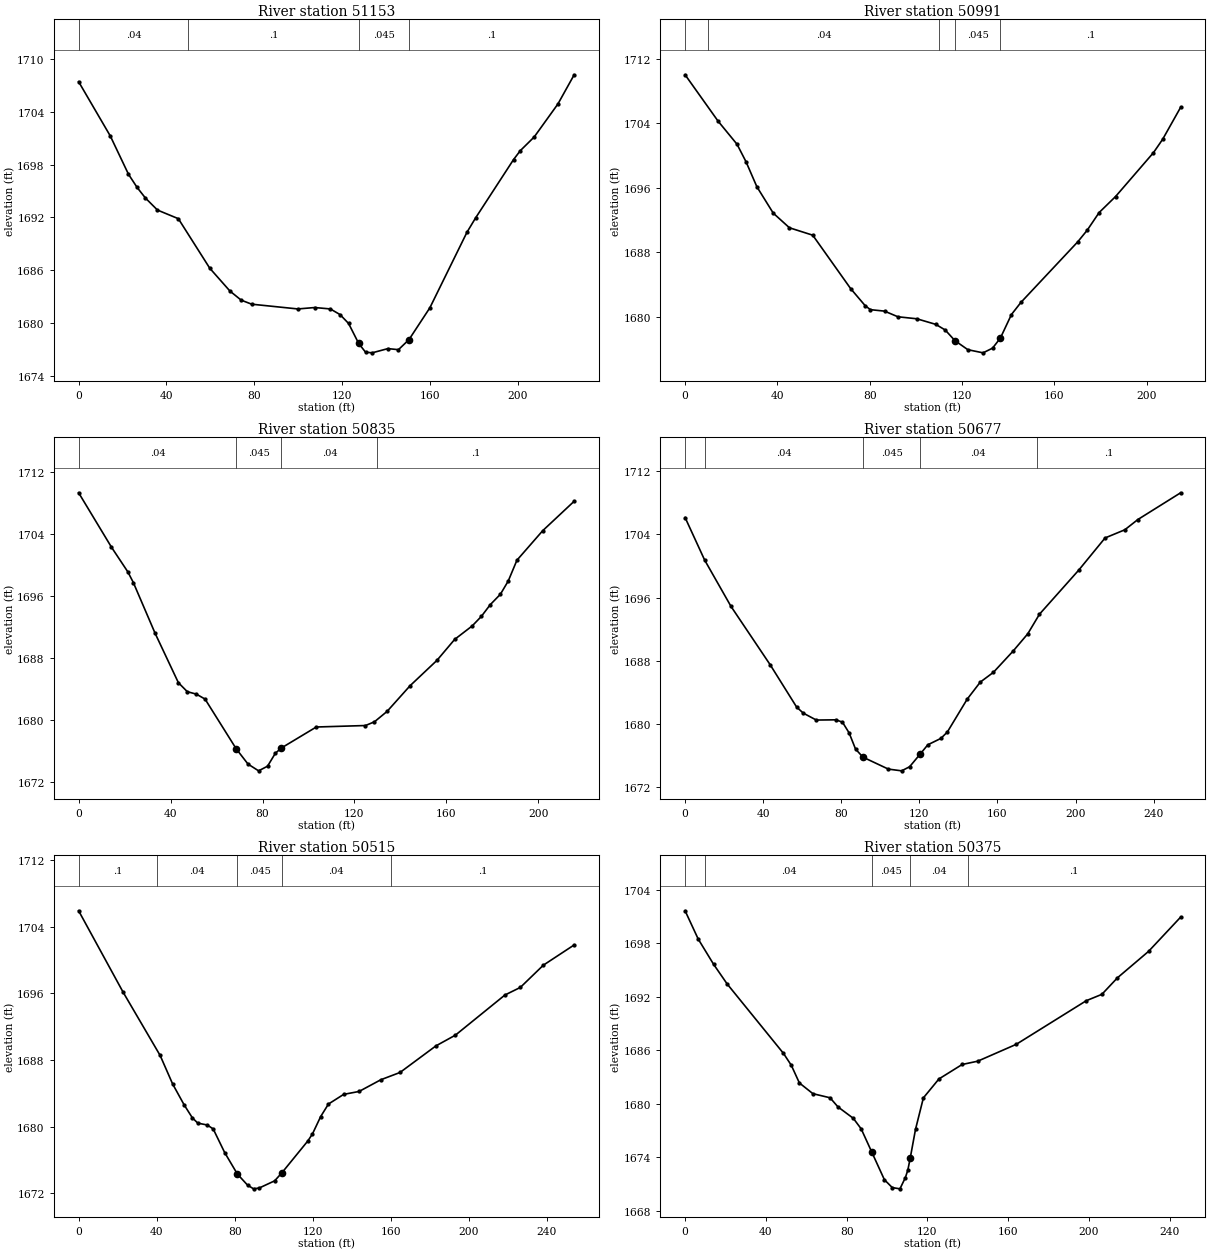
Type RM Length L Ch R = 1 ,51153   ,163.7,162.1,159.9
XS GIS Cut Line= 2
     2074088.325      229849.337     2074280.382      229731.065
#Sta/Elev= 30
       0 1707.41    14.4 1701.25    22.7 1696.89    26.6  1695.4    30.4 1694.19
    35.9 1692.82    45.4 1691.84    59.7 1686.21    68.9 1683.61      74 1682.58
    78.8 1682.12    99.8 1681.58   107.5 1681.74   114.6 1681.58     119 1680.94
   122.9 1679.93   127.51677.657   130.6 1676.67   133.6 1676.59   140.8 1677.07
   145.6 1676.95   150.41678.094   159.9 1681.71   176.8  1690.3   180.7 1691.92
     198 1698.56   201.1 1699.58   207.4 1701.13   218.2 1704.88   225.6  1708.2
#Mann= 4 ,-1 , 0
       0     .04       0      50      .1       0   127.5    .045       0
   150.4      .1       0
Bank Sta=127.5,150.4
XS Rating Curve= 0 ,0
Exp/Cntr=0.3,0.1

Type RM Length L Ch R = 1 ,50991   ,161.7,155.9,147.2
XS GIS Cut Line= 2
     2074191.407      229989.311     2074363.153      229860.505
#Sta/Elev= 30
       0 1709.99    14.3 1704.24    22.5 1701.38    26.4 1699.21    31.1 1696.11
    38.2 1692.84    45.2 1691.03    55.3 1690.11    71.7  1683.5      78 1681.38
    80.3 1680.88    86.4  1680.7    92.2    1680   100.4 1679.75   108.6 1679.06
   112.7 1678.36   116.91677.045   122.5 1675.92   129.1 1675.53   133.2 1676.11
   136.6 1677.36   141.4 1680.28   145.5 1681.78   170.1 1689.28   174.2 1690.72
   179.4 1692.92   186.5  1694.9   202.9 1700.33   206.9 1701.99   214.7 1705.96
#Mann= 5 ,-1 , 0
       0      .1       0      10     .04       0     110      .1       0
   116.9    .045       0   136.6      .1       0
Bank Sta=116.9,136.6
XS Rating Curve= 0 ,0
Exp/Cntr=0.3,0.1

Type RM Length L Ch R = 1 ,50835   ,164.3,158.4,151.4
XS GIS Cut Line= 2
     2074328.126      230105.414     2074443.014      229923.005
#Sta/Elev= 30
       0 1709.31    14.3 1702.29    21.4 1699.12    23.8 1697.74    33.3 1691.18
    43.4 1684.83    47.3 1683.67    51.2 1683.36      55 1682.72    68.61676.291
    73.7 1674.34    78.3 1673.47    82.2 1674.07    85.6 1675.74    88.21676.413
   103.4 1679.12   124.8 1679.31   128.7 1679.79   134.2 1681.13   144.2 1684.44
   155.9 1687.71   163.6 1690.41   171.2 1692.14   175.2 1693.37   179.1 1694.89
   183.5 1696.23   186.9 1697.93   190.7 1700.62   201.9 1704.42   215.6 1708.22
#Mann= 4 ,-1 , 0
       0     .04       0    68.6    .045       0    88.2     .04       0
     130      .1       0
Bank Sta=68.6,88.2
XS Rating Curve= 0 ,0
Exp/Cntr=0.3,0.1

Type RM Length L Ch R = 1 ,50677   ,149.8,161.7,167.6
XS GIS Cut Line= 2
     2074491.971      230193.304     2074547.181      229945.574
#Sta/Elev= 30
       0 1706.12      10 1700.75    23.5 1694.89    43.6  1687.5    57.1 1682.17
    60.5  1681.4    67.2 1680.52    77.3 1680.55    80.6 1680.25      84  1678.9
    87.3 1676.85    91.11675.829   104.1 1674.32   110.9  1674.1     115 1674.62
   120.41676.218   124.3 1677.39     131  1678.2   134.3    1679   144.5 1683.17
   151.2 1685.32   157.9 1686.55     168 1689.24   175.5 1691.42   181.5  1693.9
   201.6 1699.47   215.1 1703.54   225.2 1704.57   231.9 1705.87   253.8 1709.25
#Mann= 5 ,-1 , 0
       0      .1       0      10     .04       0    91.1    .045       0
   120.4     .04       0     180      .1       0
Bank Sta=91.1,120.4
XS Rating Curve= 0 ,0
Exp/Cntr=0.3,0.1

Type RM Length L Ch R = 1 ,50515   ,140.4,140.3,139
XS GIS Cut Line= 2
     2074599.393      230247.558     2074739.889      230035.852
#Sta/Elev= 30
       0 1705.91    22.8 1696.14    41.8 1688.54    48.2 1685.12    54.1 1682.61
    58.3 1681.06    61.1 1680.42      66 1680.19      69 1679.72    74.9 1676.88
    81.41674.305    86.6 1672.98    89.7 1672.53    92.6 1672.63   100.5 1673.49
   104.21674.448   117.5 1678.27   119.9 1679.12   124.1  1681.2   128.1 1682.71
   135.9 1683.87   143.8 1684.22     155 1685.63   164.8  1686.5   183.2 1689.69
   193.2 1690.98   218.6  1695.8   226.5 1696.71   238.3 1699.38   254.1 1701.81
#Mann= 5 ,-1 , 0
       0      .1       0      40     .04       0    81.4    .045       0
   104.2     .04       0     160      .1       0
Bank Sta=81.4,104.2
XS Rating Curve= 0 ,0
Exp/Cntr=0.3,0.1

Type RM Length L Ch R = 1 ,50375   ,197.5,196.5,191
XS GIS Cut Line= 2
     2074717.665      230326.768     2074845.792      230117.449
#Sta/Elev= 30
       0 1701.63     6.5 1698.46    14.1 1695.64    20.8 1693.44    48.7 1685.66
    52.6 1684.32    56.6 1682.34    63.3 1681.14    71.8 1680.68    75.7 1679.66
    83.3 1678.38    87.2  1677.2    92.4 1674.62    98.7  1671.5   102.6 1670.62
   106.4 1670.48   109.1 1671.75   110.3 1672.58   111.5 1673.94   114.1 1677.14
     118 1680.67   125.7 1682.79   137.2 1684.41   144.9 1684.78     164 1686.67
   198.7 1691.56   206.4 1692.27   214.1 1694.12   229.5 1697.08   245.4 1700.92
#Mann= 5 ,-1 , 0
       0      .1       0      10     .04       0    92.4    .045       0
   111.5     .04       0     140      .1       0
Bank Sta=92.4,111.5
XS Rating Curve= 0 ,0
Exp/Cntr=0.3,0.1

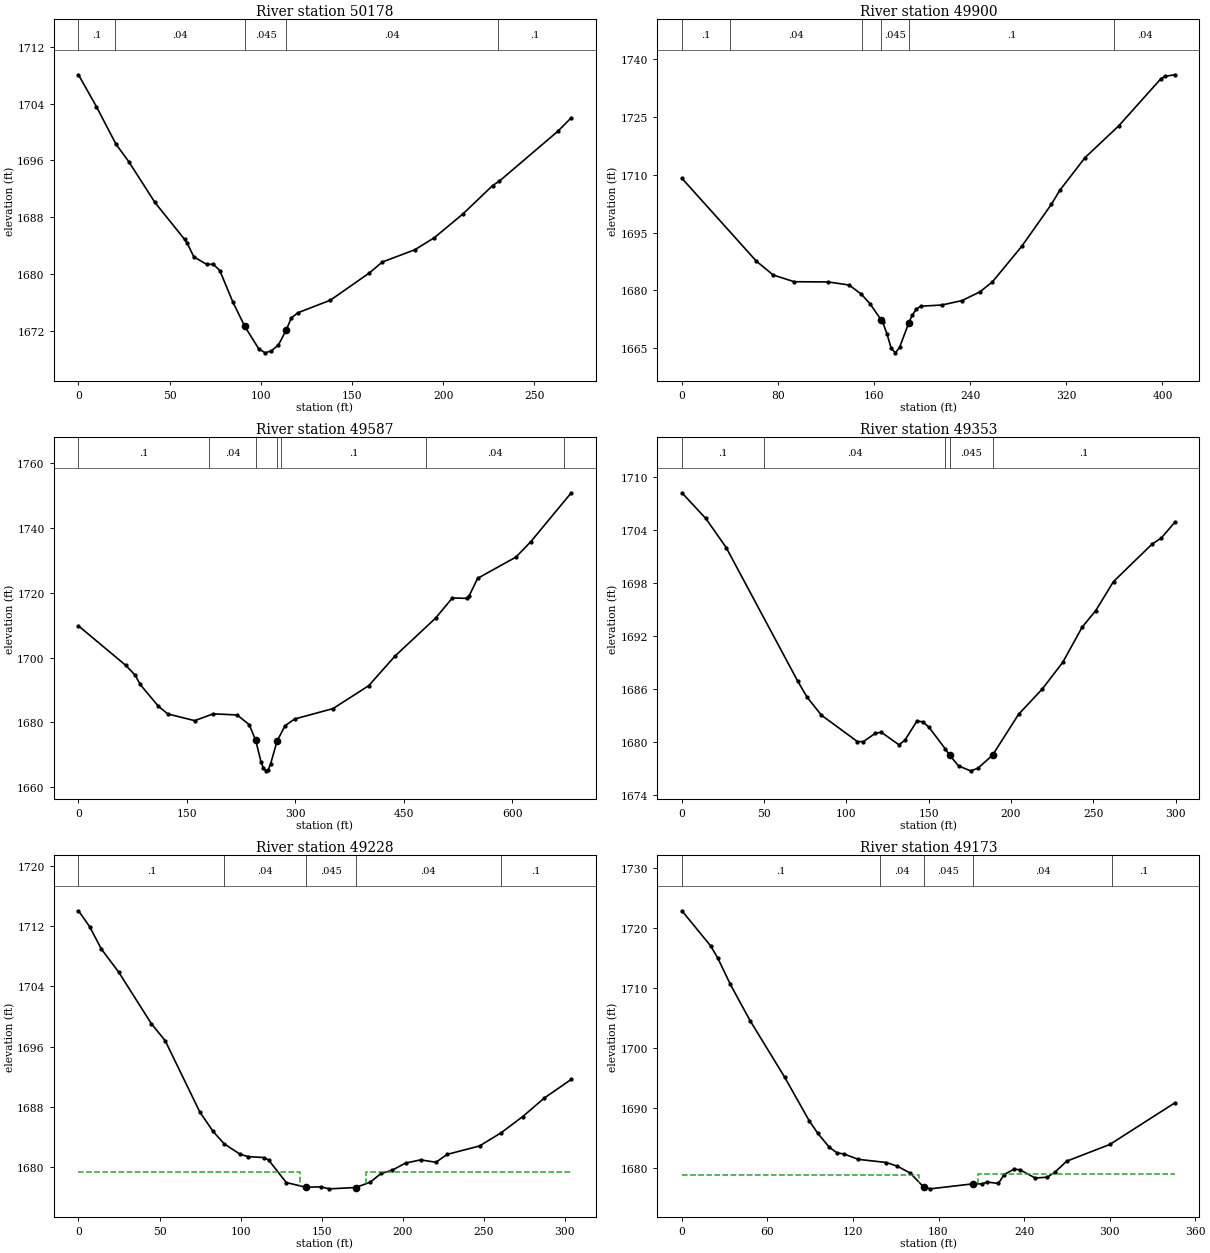
Type RM Length L Ch R = 1 ,50178   ,268.6,278.5,268.5
XS GIS Cut Line= 2
     2074896.702      230428.764     2075002.042      230179.949
#Sta/Elev= 30
       0  1708.1     9.8 1703.62    20.5 1698.33    27.6 1695.83    41.9 1690.08
    58.2 1684.86    59.7 1684.29    63.2 1682.41    70.4 1681.32    73.9 1681.37
    77.5 1680.46    84.6 1676.04    91.21672.574    98.9 1669.39   102.4 1668.85
   105.8 1669.14   109.6 1669.95   113.91672.064   116.7 1673.79   120.3 1674.51
   138.1 1676.28   159.4 1680.11   166.6 1681.67   184.4  1683.4   195.1  1685.1
   210.9 1688.48   227.1 1692.47   230.7 1693.07   262.8 1700.12   270.2 1702.03
#Mann= 5 ,-1 , 0
       0      .1       0      20     .04       0    91.2    .045       0
   113.9     .04       0     230      .1       0
Bank Sta=91.2,113.9
XS Rating Curve= 0 ,0
Exp/Cntr=0.3,0.1

Type RM Length L Ch R = 1 ,49900   ,281.5,312.1,334.9
XS GIS Cut Line= 2
     2075075.521      230553.113     2075220.792      230169.533
#Sta/Elev= 30
       0  1709.1    61.9 1687.61      76 1683.99    93.5 1682.25   121.6  1682.2
   139.1  1681.4   149.2 1679.07   156.7 1676.48     1661672.274   167.2 1671.69
   170.7  1668.7   174.2 1664.97   177.7 1663.79   181.2 1665.21   188.81671.567
   191.7 1673.55     195 1675.11   198.8  1675.9   216.3  1676.2   233.2 1677.36
   247.9  1679.6   258.4 1682.19     283  1691.5   307.5 1702.33   314.5 1705.97
   335.6 1714.49   363.6 1722.72   398.7 1734.95   402.2 1735.58   410.2 1735.98
#Mann= 6 ,-1 , 0
       0      .1       0      40     .04       0     150      .1       0
     166    .045       0   188.8      .1       0     360     .04       0
Bank Sta=166,188.8
XS Rating Curve= 0 ,0
Exp/Cntr=0.3,0.1

Type RM Length L Ch R = 1 ,49587   ,216.6,234,244.3
XS GIS Cut Line= 3
     2075132.162      230603.461     2075207.032      230536.186
     2075783.292      230464.672
#Sta/Elev= 30
       0 1709.74      65 1697.65    78.4 1694.56    85.3 1691.69   110.3 1685.03
   123.5 1682.61   160.7 1680.55   186.3 1682.65   219.4  1682.3   235.9 1679.34
     2451674.517   252.4 1667.78   255.7 1665.89   259.1 1665.09   262.4 1665.43
   265.7 1667.31   274.51674.239   285.5 1678.97   298.9 1681.06   351.8 1684.26
   401.2 1691.31   437.6 1700.44   493.8 1712.15   516.9 1718.35   536.8 1718.22
   540.1    1719   551.8 1724.38   604.8 1730.93   625.4 1735.69   681.3 1750.74
#Mann= 7 ,-1 , 0
       0      .1       0  180.66     .04       0     245    .045       0
   274.5     .04       0  280.66      .1       0  480.66     .04       0
  670.66      .1       0
Bank Sta=245,274.5
XS Rating Curve= 0 ,0
Exp/Cntr=0.3,0.1

Type RM Length L Ch R = 1 ,49353   ,98.9,125,147.8
XS GIS Cut Line= 2
     2075139.757      230647.948     2075411.025      230774.902
#Sta/Elev= 30
       0 1708.22    14.5 1705.31    26.9 1702.02    70.3 1686.92    76.1 1685.07
    84.8 1683.04   106.6 1680.06   110.2 1680.04   117.4 1680.97   121.1 1681.12
   131.9 1679.69   135.5  1680.2   142.8 1682.37   146.4 1682.29   150.2 1681.66
     160 1679.24   162.81678.487   168.1  1677.3   175.4 1676.74   179.8 1677.02
   188.81678.518   204.6 1683.14   218.9 1685.98   231.4 1689.01   243.3 1693.02
   251.5 1694.88   262.3 1698.17   285.8 1702.42   291.3 1703.09   299.5 1704.87
#Mann= 5 ,-1 , 0
       0      .1       0      50     .04       0     160      .1       0
   162.8    .045       0   188.8      .1       0
Bank Sta=162.8,188.8
XS Rating Curve= 0 ,0
Exp/Cntr=0.5,0.3

Type RM Length L Ch R = 1 ,49228   ,64.8,55.6,56.3
XS GIS Cut Line= 5
     2075102.012      230740.7222075219.46724779230792.212512368
2075233.11828931230859.995826414     2075242.579      230881.195
      2075324.87      230867.132
#Sta/Elev= 30
       0 1714.06     6.9 1711.94    14.1 1708.98    24.8 1705.91      45 1699.04
    53.5 1696.79    74.9  1687.3      83 1684.75    89.9 1683.08    99.8 1681.69
   104.8 1681.38   114.4 1681.26   117.3 1680.94   128.2 1677.94   140.41677.305
   149.4 1677.37   154.8  1677.1     1711677.274     180 1677.98   186.7 1679.14
   193.4 1679.56   201.8 1680.52   211.1 1680.95   220.6 1680.63   227.5 1681.68
   247.5  1682.8   260.8 1684.55   274.1  1686.7   287.4 1689.16   304.1 1691.65
#Mann= 5 ,-1 , 0
       0      .1       0      90     .04       0   140.4    .045       0
     171     .04       0   260.6      .1       0
#XS Ineff= 2 , 0
          136.46 1679.34  177.12         1679.34
Permanent Ineff=
       F       F
Bank Sta=140.4,171
XS Rating Curve= 0 ,0
Exp/Cntr=0.5,0.3

Type RM Length L Ch R = 1 ,49173   ,216.5,171.4,107.8
XS GIS Cut Line= 5
      2075075.97      230761.5552075179.35804947230795.337512368
2075183.35362809230847.3513966442075209.32031405230902.619115724
     2075330.079      230875.987
#Sta/Elev= 30
       0 1722.89    20.2 1717.02    25.2 1714.98      34 1710.61    47.8 1704.58
      72 1695.18    89.3 1687.88    95.4 1685.77   103.2 1683.52   108.8 1682.53
   113.8 1682.35   123.6 1681.46   143.4 1680.93   151.1 1680.32   160.3 1679.14
   169.6 1676.83   174.2 1676.54   204.4 1677.38   210.5 1677.36   214.1 1677.67
     222 1677.44   226.1 1678.93   232.8  1679.8   236.9 1679.74   247.9 1678.34
   256.3 1678.48   261.6  1679.3   269.9 1681.15   300.2 1683.94   345.7 1690.86
#Mann= 5 ,-1 , 0
       0      .1       0  138.77     .04       0   169.6    .045       0
   204.4     .04       0     302      .1       0
#XS Ineff= 2 , 0
          166.52 1678.89  207.88         1679.03
Permanent Ineff=
       F       F
Bank Sta=169.6,204.4
XS Rating Curve= 0 ,0
Exp/Cntr=0.5,0.3

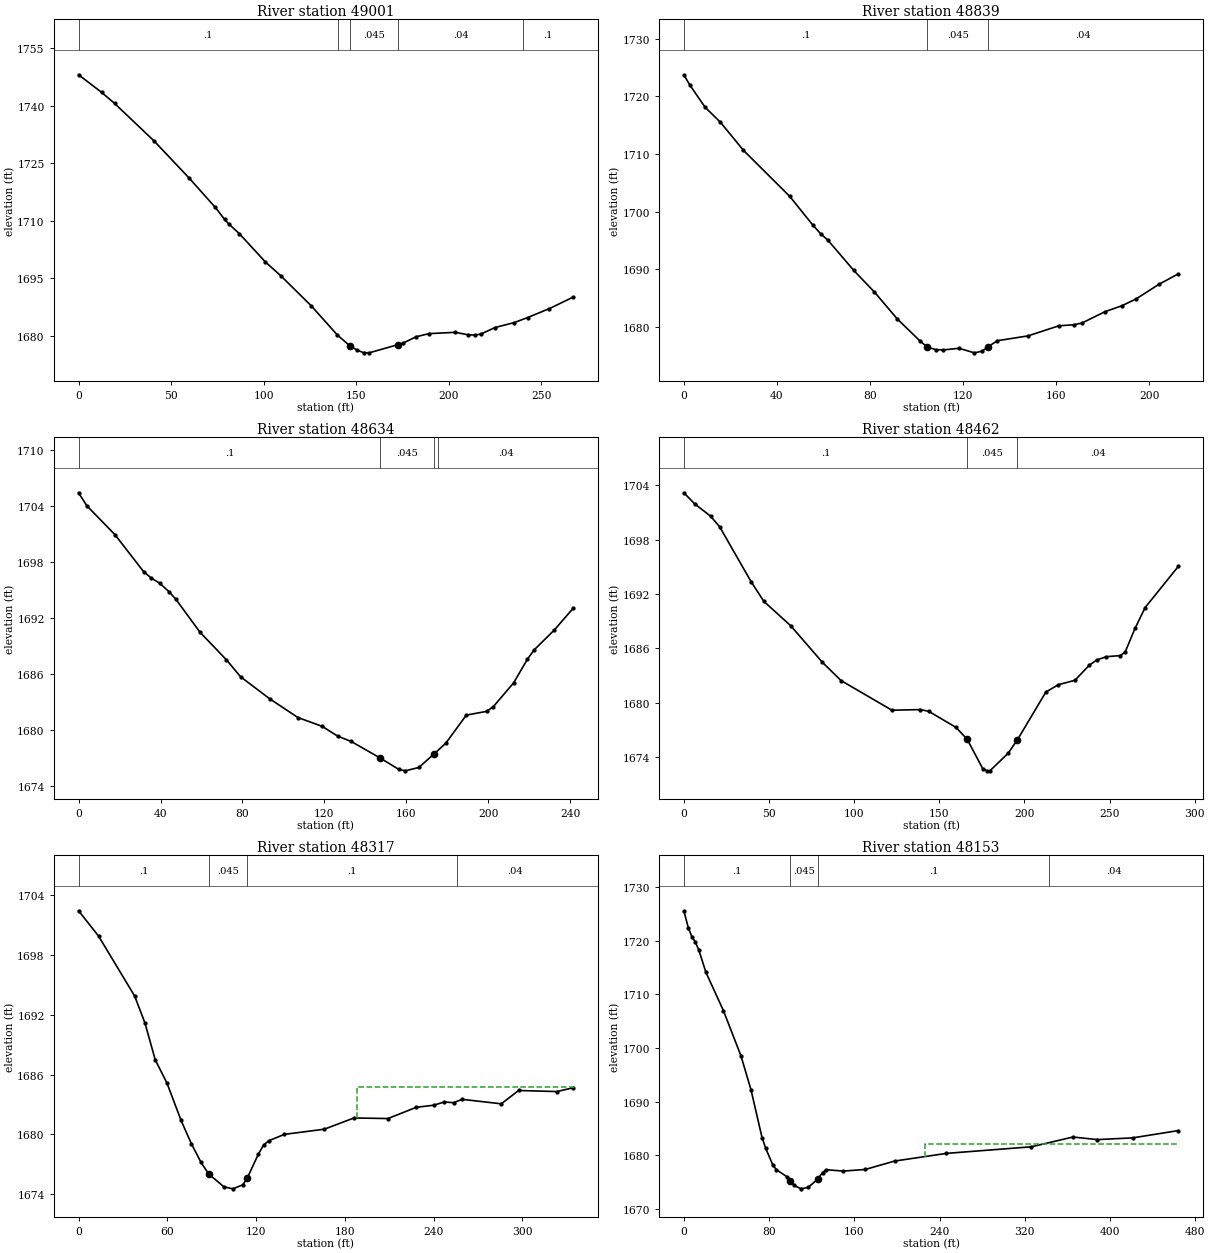
Type RM Length L Ch R = 1 ,49001   ,167.9,162.3,155.6
XS GIS Cut Line= 2
     2075233.522      231130.045     2075334.028      230882.432
#Sta/Elev= 30
       0 1748.05    12.4 1743.49    19.5 1740.57    40.7 1730.86    59.7 1721.17
    73.9  1713.5    78.9 1710.39    81.4 1709.09    86.8  1706.7   100.9 1699.32
   109.2 1695.73   125.7 1687.88   139.9 1680.24   146.61677.445   150.5 1676.32
     154 1675.68     157 1675.62   172.71677.772   175.3 1678.14   182.4 1679.81
   189.4 1680.63   203.6 1680.96   210.7  1680.3   214.2 1680.24   217.5 1680.53
     225 1682.21   235.5 1683.51   242.6  1684.8   254.3 1687.12   267.2 1690.12
#Mann= 5 ,-1 , 0
       0      .1       0     140     .04       0   146.6    .045       0
   172.7     .04       0     240      .1       0
Bank Sta=146.6,172.7
XS Rating Curve= 0 ,0
Exp/Cntr=0.3,0.1

Type RM Length L Ch R = 1 ,48839   ,205.2,204.9,205.4
XS GIS Cut Line= 2
     2075436.459      231134.168     2075461.632      230923.231
#Sta/Elev= 30
       0 1723.76     2.5 1722.02     9.1 1718.13    15.7 1715.52    25.6 1710.63
    45.5 1702.63    55.4 1697.64    58.7 1696.17      62 1694.97      73 1689.76
    81.8 1686.04    91.7 1681.33   101.6 1677.45   104.61676.441   108.2 1676.01
   111.4 1675.96   118.2 1676.24   124.8 1675.45   128.1 1675.73   130.71676.518
   134.7 1677.56   147.9  1678.4   161.1 1680.15   167.5 1680.32     171 1680.63
   180.9  1682.6   188.2 1683.64   194.1 1684.78   204.1 1687.36   212.4 1689.18
#Mann= 3 ,-1 , 0
       0      .1       0   104.6    .045       0   130.7     .04       0
Bank Sta=104.6,130.7
XS Rating Curve= 0 ,0
Exp/Cntr=0.3,0.1

Type RM Length L Ch R = 1 ,48634   ,151.9,171.8,198.1
XS GIS Cut Line= 3
     2075598.785       231164.55     2075646.528      231093.369
     2075665.626      230938.856
#Sta/Elev= 30
       0 1705.38       4    1704    17.8 1700.89    31.7 1696.96    35.6 1696.24
    39.6 1695.71    44.2 1694.79    47.5 1693.99    59.3 1690.46    72.2 1687.51
    79.1  1685.7    93.4 1683.33   107.1 1681.34   118.9  1680.4   126.5 1679.35
   133.1 1678.78   147.31677.005   156.2 1675.81   159.5 1675.64   166.1    1676
   173.31677.395   179.3  1678.6   189.3  1681.6   199.2    1682   202.5 1682.51
   212.4 1685.05   219.1 1687.57   222.3 1688.55   232.2 1690.69   241.4 1693.01
#Mann= 4 ,-1 , 0
       0      .1       0   147.3    .045       0   173.3      .1       0
  175.71     .04       0
Bank Sta=147.3,173.3
XS Rating Curve= 0 ,0
Exp/Cntr=0.3,0.1

Type RM Length L Ch R = 1 ,48462   ,130.7,145,169.9
XS GIS Cut Line= 2
     2075625.695      231178.439      2075886.98      231051.703
#Sta/Elev= 30
       0 1703.15     6.3 1701.94    15.7 1700.57      21 1699.41    39.5 1693.35
      47 1691.18    62.8 1688.49    81.3 1684.48    92.3 1682.46   122.2 1679.19
   138.9 1679.26   143.8 1679.07   159.8  1677.3   166.41675.987   175.7 1672.69
   178.2 1672.51   179.8 1672.52   190.4 1674.44   195.81675.898   212.6 1681.19
   219.9    1682   229.7 1682.49   238.1 1684.15   242.5 1684.73   248.2 1685.09
   256.4 1685.21   259.2 1685.61     265 1688.22   270.9  1690.5   290.4 1695.04
#Mann= 3 ,-1 , 0
       0      .1       0   166.4    .045       0   195.8     .04       0
Bank Sta=166.4,195.8
XS Rating Curve= 0 ,0
Exp/Cntr=0.3,0.1

Type RM Length L Ch R = 1 ,48317   ,176.7,163.9,152.8
XS GIS Cut Line= 3
      2075636.98        231195.8      2075793.23      231252.224
     2075937.327      231165.418
#Sta/Elev= 30
       0 1702.45    13.5 1699.91    37.9 1693.89    44.9 1691.17    51.8 1687.49
    59.8 1685.13    69.3 1681.39    76.3 1679.04    82.8 1677.17      881676.011
    98.2 1674.73   104.2 1674.52     111 1674.92     1141675.592   121.6 1678.02
   125.1 1678.92   128.6 1679.35   139.1 1679.99   166.1 1680.51   186.2 1681.64
   209.2 1681.58   228.3 1682.71   240.2 1682.92   247.2 1683.25   253.5 1683.17
   259.3 1683.51   285.8 1683.06   297.5  1684.4   323.4 1684.29   334.3 1684.67
#Mann= 4 ,-1 , 0
       0      .1       0      88    .045       0     114      .1       0
  256.13     .04       0
#XS Ineff= 2 , 0
                          188.08         1684.71
Permanent Ineff=
       F       F
Bank Sta=88,114
XS Rating Curve= 0 ,0
Exp/Cntr=0.3,0.1

Type RM Length L Ch R = 1 ,48153   ,139.7,140.5,141.5
XS GIS Cut Line= 4
      2075583.16      231388.508     2075653.473      231395.453
      2075793.23      231369.411     2075946.007      231169.758
#Sta/Elev= 30
       0 1725.57     4.2 1722.38     7.5 1720.75    10.8 1719.72    14.1 1718.22
    20.7  1714.1    37.1 1706.97    53.6 1698.53      63 1692.21    73.4 1683.29
    76.8  1681.3    83.5 1678.19    86.8 1677.31    96.8 1675.98    99.7 1675.25
   103.5 1674.36   110.2 1673.73   116.8 1674.01   125.6 1675.53   130.2 1676.77
   133.5  1677.3   149.5 1677.04   170.2 1677.34   197.9 1678.91   246.5 1680.34
   326.3 1681.57   365.3 1683.39   388.2 1682.91   421.3 1683.23   464.2 1684.59
#Mann= 4 ,-1 , 0
       0      .1       0    99.7    .045       0   125.6      .1       0
  342.82     .04       0
#XS Ineff= 2 , 0
                          226.19            1682
Permanent Ineff=
       F       F
Bank Sta=99.7,125.6
XS Rating Curve= 0 ,0
Exp/Cntr=0.3,0.1

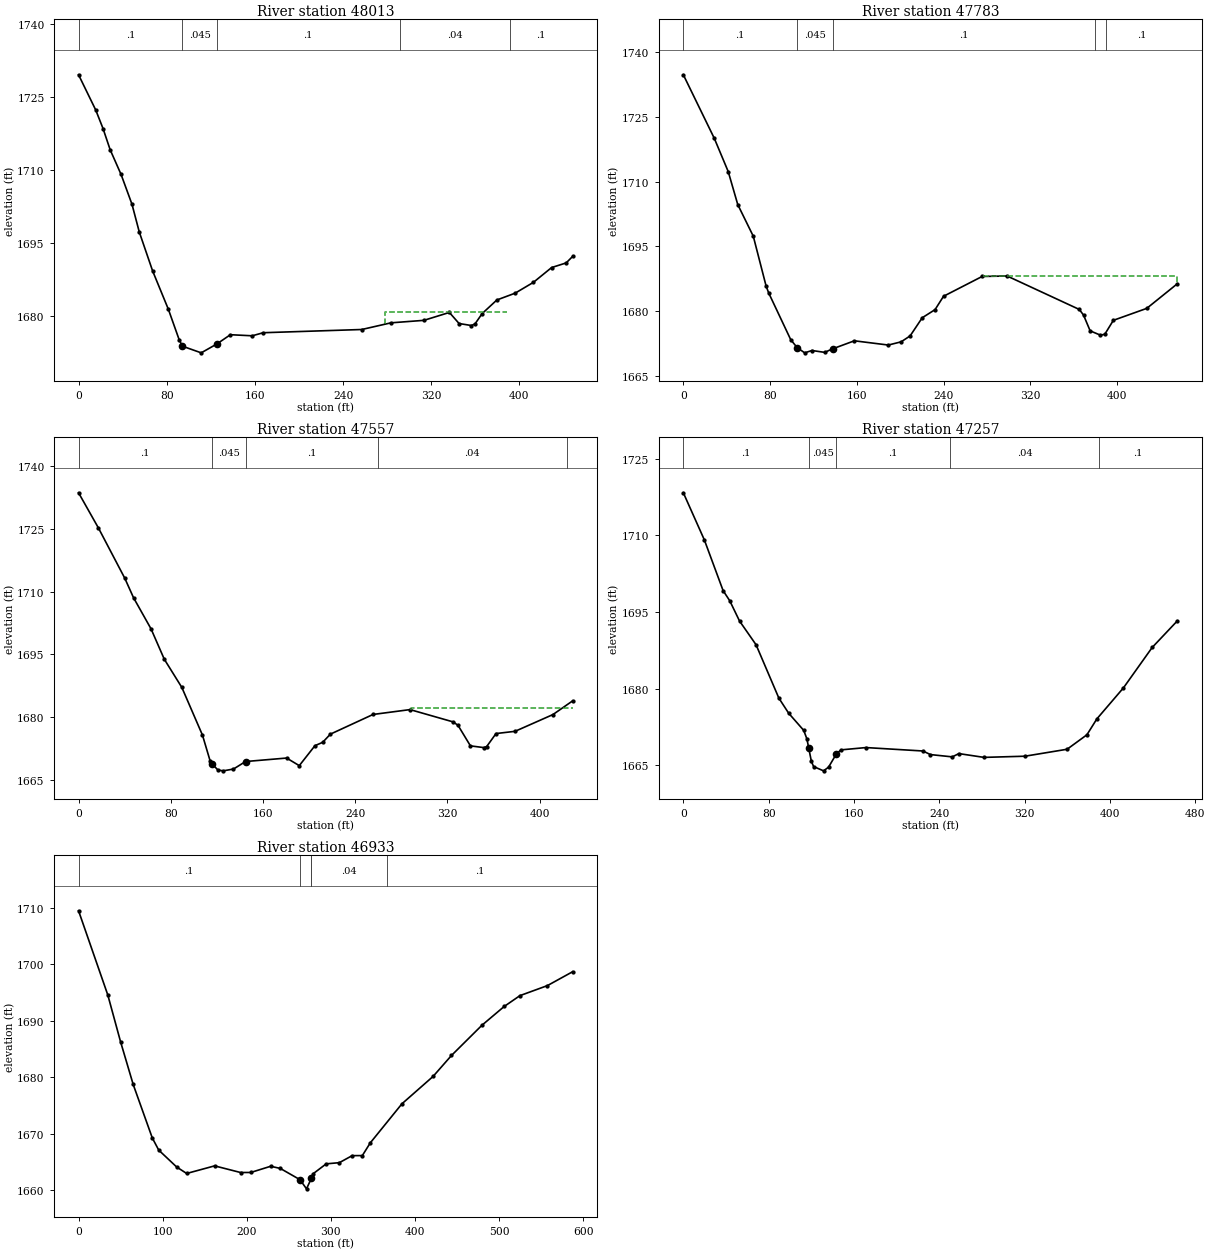
Type RM Length L Ch R = 1 ,48013   ,240.6,230.4,218
XS GIS Cut Line= 3
     2075584.896      231537.814     2075656.077      231532.606
     2076029.341      231480.522
#Sta/Elev= 30
       0  1729.5    15.6 1722.26    22.2 1718.47    28.7  1714.1    38.6 1709.03
    48.5 1702.91    55.1 1697.23    67.2 1689.24    81.5 1681.36    91.4 1675.05
    94.31673.783   111.3 1672.42   125.41674.226   137.8 1676.14   157.6 1675.92
   167.6 1676.55     257 1677.21   283.5 1678.58   313.4 1679.09   336.5 1680.71
   345.3 1678.44   356.4 1678.03   359.7 1678.34   366.3 1680.49   379.6 1683.27
   396.2 1684.67   412.7 1686.88   429.3 1689.93   442.5 1690.88   448.3  1692.2
#Mann= 5 ,-1 , 0
       0      .1       0    94.3    .045       0   125.4      .1       0
  291.37     .04       0  391.37      .1       0
#XS Ineff= 1 ,-1
  278.33  389.221680.851
Permanent Ineff=
       F
Bank Sta=94.3,125.4
XS Rating Curve= 0 ,0
Exp/Cntr=0.3,0.1

Type RM Length L Ch R = 1 ,47783   ,240.6,225.3,200.6
XS GIS Cut Line= 2
     2075655.209      231810.383     2076037.153      231562.119
#Sta/Elev= 30
       0 1734.65    28.6 1719.94    41.4 1712.28    50.2 1704.66    64.5 1697.36
    76.3 1685.87    78.7 1684.26      99 1673.48   104.91671.647   111.9 1670.43
   118.6 1670.97   130.3 1670.54   137.61671.349   157.7 1673.21     189 1672.23
   200.8 1672.97   209.1 1674.34   220.3 1678.54   232.1 1680.41   239.9 1683.49
   275.5 1688.07   298.6 1688.17   365.1 1680.45     369 1679.15   375.1 1675.51
   384.6 1674.51   388.6 1674.72   396.5 1677.94   427.3  1680.7   455.5 1686.39
#Mann= 5 ,-1 , 0
       0      .1       0   104.9    .045       0   137.6      .1       0
     380     .04       0     390      .1       0
#XS Ineff= 2 , 0
                          276.17         1688.21
Permanent Ineff=
       F       F
Bank Sta=104.9,137.6
XS Rating Curve= 0 ,0
Exp/Cntr=0.3,0.1

Type RM Length L Ch R = 1 ,47557   ,288.7,299.8,310.5
XS GIS Cut Line= 4
     2075884.376      231970.106     2075934.723      231884.168
     2075977.257      231694.932     2076058.855      231587.293
#Sta/Elev= 30
       0 1733.55    17.3 1725.13    40.1 1713.18    47.7 1708.53    62.9  1701.1
    74.4 1693.86    89.6 1687.15   107.5 1675.78   114.3 1669.49   115.81668.936
     121 1667.43   125.6 1667.26   134.4 1667.69   144.9 1669.48   180.5 1670.31
   191.5  1668.5   205.1 1673.26   211.8 1674.06   218.5 1676.01   255.5  1680.7
   287.6 1681.86   325.2 1678.91   329.3 1678.07     340 1673.21   351.7  1672.8
   354.1 1673.06   362.2 1676.15   378.7 1676.68   411.6 1680.68   428.6 1683.93
#Mann= 5 ,-1 , 0
       0      .1       0   115.8    .045       0   144.9      .1       0
   259.6     .04       0  423.56      .1       0
#XS Ineff= 2 , 0
                          288.78         1682.14
Permanent Ineff=
       F       F
Bank Sta=115.8,144.9
XS Rating Curve= 0 ,0
Exp/Cntr=0.3,0.1

Type RM Length L Ch R = 1 ,47257   ,317.8,324.8,334.3
XS GIS Cut Line= 2
     2076104.862      232090.331     2076400.435       231733.56
#Sta/Elev= 30
       0  1718.3    19.7 1709.09    37.3 1699.17    43.5  1697.2    52.7 1693.23
    68.2 1688.59    89.6 1678.15    98.8  1675.2   112.9 1671.85   115.9 1670.17
   117.51668.485   120.1 1665.77   122.2 1664.77   131.5 1663.94   136.2 1664.66
   143.61667.281   147.9 1668.04   171.3 1668.49   224.7 1667.82   231.7 1667.12
   252.2 1666.67   258.4 1667.31     282 1666.57   320.4  1666.8   359.9 1668.16
   378.5 1670.99   387.8 1674.09   412.7 1680.15   439.7 1688.06   463.3 1693.26
#Mann= 5 ,-1 , 0
       0      .1       0   117.5    .045       0   143.6      .1       0
     250     .04       0     390      .1       0
Bank Sta=117.5,143.6
XS Rating Curve= 0 ,0
Exp/Cntr=0.3,0.1

Type RM Length L Ch R = 1 ,46933   ,440.3,462.7,461.2
XS GIS Cut Line= 4
     2076255.903      232232.258     2076331.424       232189.29
2076573.94934728232033.0547922892076740.21608974231901.396419254
#Sta/Elev= 30
       01709.465  34.7871694.558  49.8861686.318  64.9841678.717  87.6581669.268
  95.3381667.104   116.7 1664.11 128.5681662.968 161.8081664.314 192.6551663.138
 204.7381663.143 228.4231664.241 239.8621663.864 263.2781661.873 271.0831660.248
 276.8881662.113 278.8881662.912 294.4991664.672  310.111664.879 325.3531666.124
 337.4691666.135 346.9391668.389 384.5881675.306 421.5821680.144 443.4911683.858
 479.7161689.207 506.1411692.525 524.8931694.447  557.591696.223 587.463 1698.67
#Mann= 5 ,-1 , 0
       0      .1       0 263.278    .045       0 276.888      .1       0
  276.89     .04       0  366.89      .1       0
#XS Ineff= 1 ,-1
  421.21   570.2 1669.65
Permanent Ineff=
       F
Bank Sta=263.278,276.888
XS Rating Curve= 0 ,0
Exp/Cntr=0.3,0.1