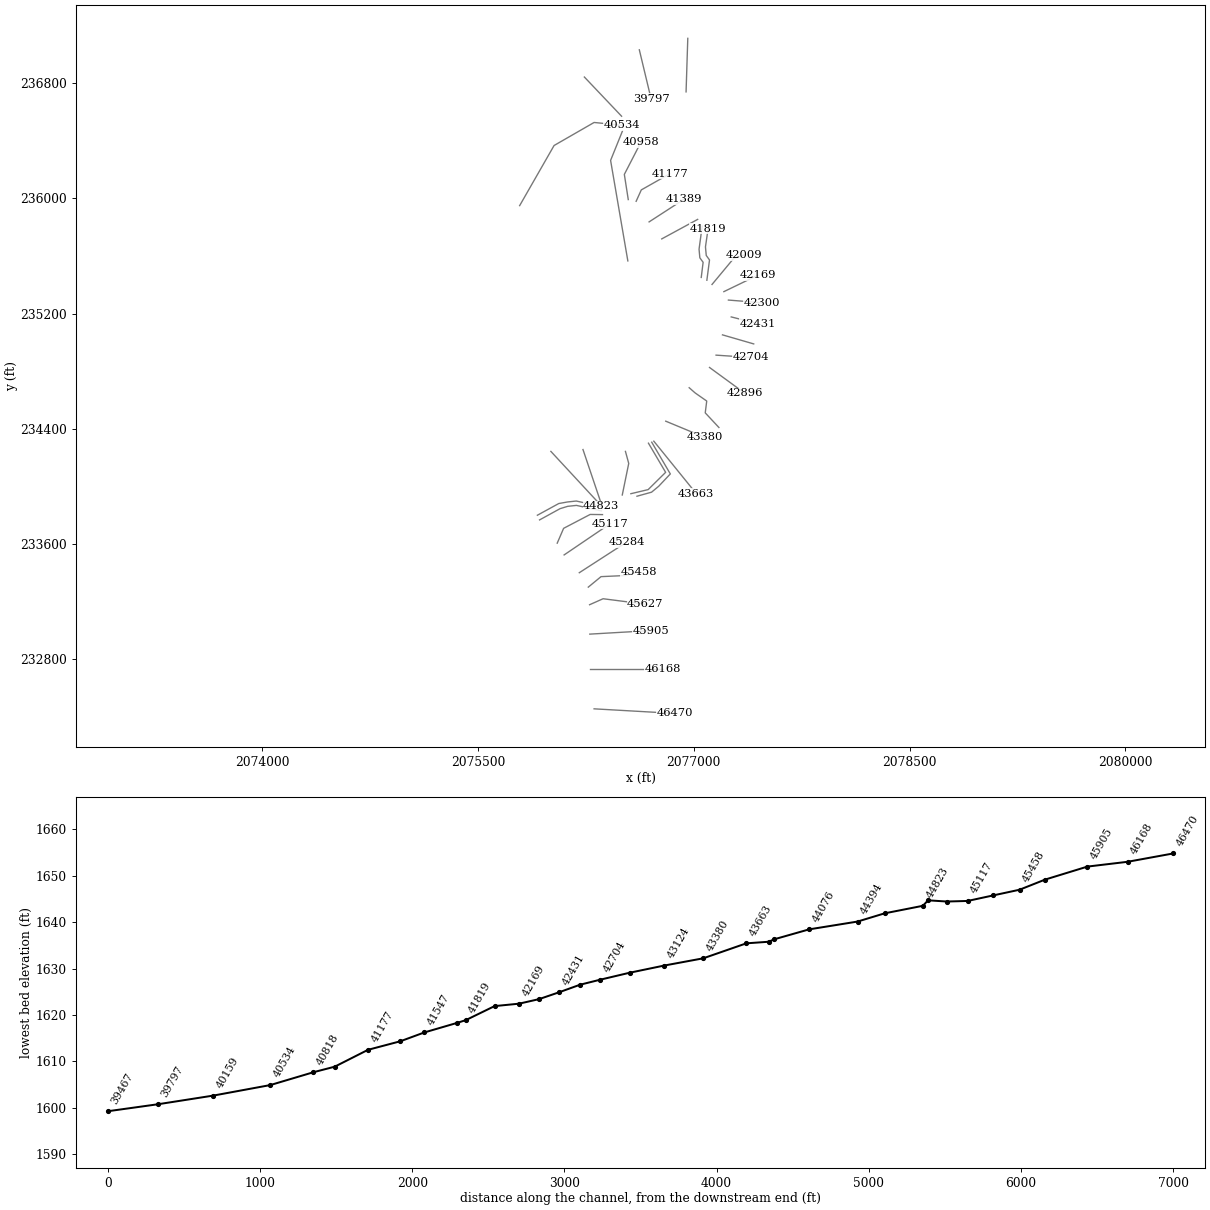
HEC-RAS study WOLFCK.prj: WOLFCK

--- WOLFCK.g01 (geometry) --- (continued)

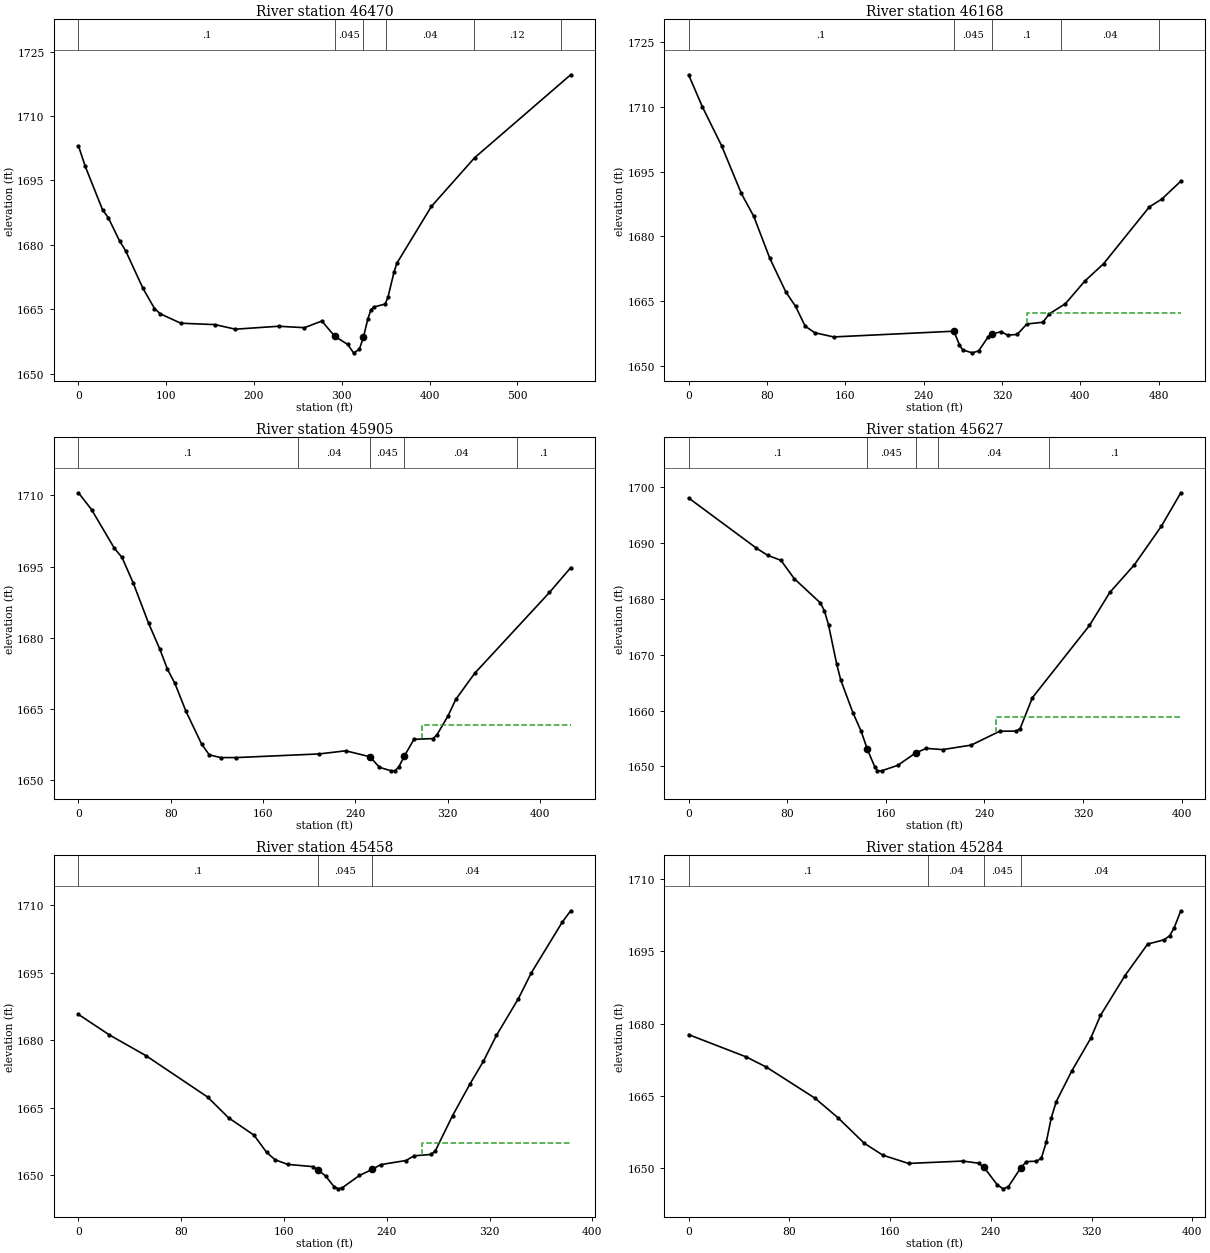
Type RM Length L Ch R = 1 ,46470   ,298.2,301.8,300.3
XS GIS Cut Line= 3
     2076307.987      232451.008      2076766.32      232424.967
2076867.68000569232419.430014519
#Sta/Elev= 30
       0 1703.04     7.7 1698.26    27.4 1688.15      34 1686.28    47.1 1680.78
    53.7 1678.62    73.4 1669.88    86.6 1665.15    93.1 1663.93   116.5 1661.73
   155.6  1661.4   178.7 1660.34   227.9 1661.02   257.4 1660.69   277.2 1662.24
   291.81658.706   306.7 1656.78   313.3 1654.83   319.9 1655.63   324.61658.523
   329.7 1662.81     333 1664.78   336.3  1665.5   349.4 1666.19   352.7 1667.93
   359.3 1673.54   362.6 1675.68     402 1688.93   451.3 1700.28   560.6 1719.58
#Mann= 6 ,-1 , 0
       0      .1       0   291.8    .045       0   324.6      .1       0
     350     .04       0     450     .12       0  549.07      .1       0
Bank Sta=291.8,324.6
XS Rating Curve= 0 ,0
Exp/Cntr=0.3,0.1

Type RM Length L Ch R = 1 ,46168   ,262.2,263.5,265.4
XS GIS Cut Line= 2
     2076281.945      232725.748     2076784.549      232725.748
#Sta/Elev= 30
       0 1717.49      14 1710.09    33.7 1701.03    53.8 1689.99    66.5 1684.69
    82.9 1674.95    99.3 1667.12   109.2 1663.81     119 1659.21   128.9 1657.68
   148.1 1656.71   270.91658.037   276.5 1654.91   279.8  1653.7   289.6 1653.02
   296.2 1653.47     306 1656.76     3101657.372   319.2 1657.94   325.7 1657.11
   335.6 1657.29   345.4 1659.71   361.8 1660.11   368.4 1662.07   384.8 1664.42
   404.5 1669.64   423.7 1673.67   470.5 1686.86   483.2 1688.67   502.6 1692.82
#Mann= 5 ,-1 , 0
       0      .1       0   270.9    .045       0     310      .1       0
     380     .04       0     480      .1       0
#XS Ineff= 2 , 0
                          345.36         1662.17
Permanent Ineff=
       F       F
Bank Sta=270.9,310
XS Rating Curve= 0 ,0
Exp/Cntr=0.3,0.1

Type RM Length L Ch R = 1 ,45905   ,276.3,278.1,263
XS GIS Cut Line= 2
     2076278.039       232970.54      2076703.82      232995.279
#Sta/Elev= 30
       0 1710.55    11.4 1706.99    31.1 1698.87    37.7 1696.95    47.5 1691.54
    60.7 1683.11    70.6 1677.57    77.1 1673.39    83.6 1670.39    93.1 1664.56
   106.7 1657.63   113.3 1655.37   123.1 1654.78   136.3 1654.78   208.6 1655.55
   231.6 1656.21   252.61654.954   260.8 1652.73     271 1651.99   274.3 1652.02
   277.6 1652.82   282.21655.016   290.7 1658.63   307.2 1658.78   310.5 1659.53
   320.3 1663.59   326.9 1667.02   343.3 1672.52   408.1 1689.55   426.5 1694.77
#Mann= 5 ,-1 , 0
       0      .1       0     190     .04       0   252.6    .045       0
   282.2     .04       0     380      .1       0
#XS Ineff= 2 , 0
                          297.43         1661.65
Permanent Ineff=
       F       F
Bank Sta=252.6,282.2
XS Rating Curve= 0 ,0
Exp/Cntr=0.3,0.1

Type RM Length L Ch R = 1 ,45627   ,164.3,168.3,173.2
XS GIS Cut Line= 3
     2076276.737      233174.967     2076370.487      233216.633
     2076664.757      233178.873
#Sta/Elev= 30
       0 1698.12    54.9 1689.14    64.1 1687.84    74.9 1686.94    85.7 1683.65
   106.9  1679.3   110.2 1677.86   113.5 1675.36   120.1 1668.37   123.4 1665.49
   133.3 1659.61   139.9 1656.34     1451653.053   151.1 1649.87   153.2 1649.21
   156.5 1649.19   169.7 1650.18   184.1 1652.39   192.8 1653.22   206.1    1653
   229.2  1653.8   252.4 1656.29   265.6 1656.32   268.9 1656.74   278.9 1662.31
   325.2 1675.26   341.7 1681.18   361.6 1686.13   383.4 1693.01   399.3 1699.05
#Mann= 5 ,-1 , 0
       0      .1       0     145    .045       0   184.1      .1       0
  202.59     .04       0  292.59      .1       0
#XS Ineff= 2 , 0
                          249.09         1658.78
Permanent Ineff=
       F       F
Bank Sta=145,184.1
XS Rating Curve= 0 ,0
Exp/Cntr=0.3,0.1

Type RM Length L Ch R = 1 ,45458   ,159.6,173.9,187.1
XS GIS Cut Line= 4
     2076267.622      233297.363     2076356.164      233370.279
     2076525.435      233378.092     2076620.487      233405.435
#Sta/Elev= 30
       0 1685.71      24 1681.17    52.5 1676.56   100.5 1667.38   116.9 1662.75
   136.6 1658.92   146.4 1655.11     153 1653.46   162.8 1652.43   182.5 1651.93
   186.41651.216   192.4 1649.83     199 1647.46   202.2    1647   205.5 1647.27
   218.7 1649.97   228.81651.339   235.2 1652.37   254.8 1653.28   261.4 1654.34
   274.5 1654.63   277.8 1655.45   291.2 1663.26   304.8  1670.3   315.1 1675.27
   325.3 1681.04   342.4 1689.21   352.6    1695   376.5 1706.16   383.1 1708.71
#Mann= 3 ,-1 , 0
       0      .1       0   186.4    .045       0   228.8     .04       0
#XS Ineff= 2 , 0
                          267.02         1657.25
Permanent Ineff=
       F       F
Bank Sta=186.4,228.8
XS Rating Curve= 0 ,0
Exp/Cntr=0.3,0.1

Type RM Length L Ch R = 1 ,45284   ,167,167.6,167.9
XS GIS Cut Line= 2
     2076205.122      233397.623     2076533.247      233609.863
#Sta/Elev= 30
       0  1677.7    45.7 1673.09    61.8 1670.97   100.4 1664.53   118.7 1660.47
   139.5  1655.2   154.3 1652.73   174.6 1651.03   217.6 1651.52   230.2 1651.08
   234.5 1650.23     245 1646.63   249.7 1645.77   253.9 1646.23   263.81650.152
   268.2 1651.41   276.2 1651.49   280.1 1652.12     284 1655.46   287.9 1660.42
   291.9 1663.83   304.1 1670.11   319.2  1676.9     327 1681.67   346.5 1689.93
   364.5 1696.45   377.8 1697.35   382.1 1698.22   385.6 1699.86   390.8 1703.34
#Mann= 4 ,-1 , 0
       0      .1       0     190     .04       0   234.5    .045       0
   263.8     .04       0
Bank Sta=234.5,263.8
XS Rating Curve= 0 ,0
Exp/Cntr=0.3,0.1

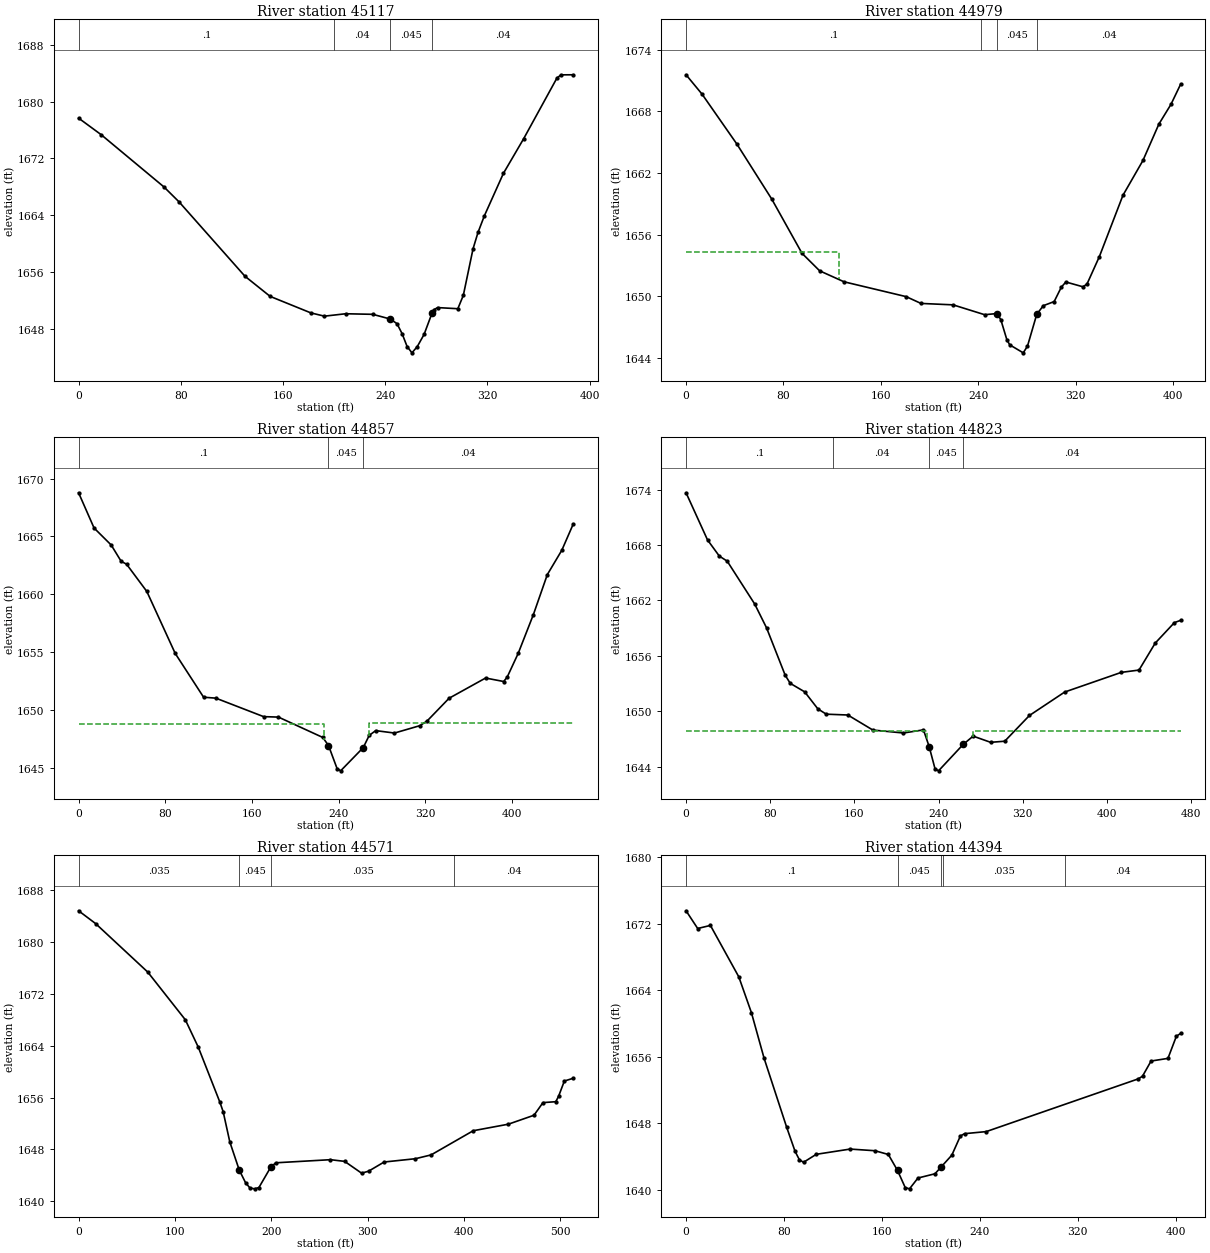
Type RM Length L Ch R = 1 ,45117   ,140.8,137.4,134.2
XS GIS Cut Line= 2
     2076099.653      233521.321     2076419.966      233738.769
#Sta/Elev= 30
       0 1677.67    17.7 1675.33    66.8 1667.97    78.7 1665.85   130.2 1655.38
   149.9 1652.54   181.8 1650.21   192.4 1649.75     209 1650.09   230.2 1650.01
     2441649.343   249.2 1648.69   253.2 1647.28   257.1 1645.47   260.9 1644.58
   265.1 1645.47   270.4 1647.18   276.51650.128   278.2 1650.66   280.9 1650.96
   296.8  1650.8   301.1 1652.68   308.7 1659.24   312.6 1661.56   317.6 1663.91
   332.5 1669.89   348.3 1674.76   374.3  1683.3   377.5 1683.77   387.1 1683.78
#Mann= 4 ,-1 , 0
       0      .1       0     200     .04       0     244    .045       0
   276.5     .04       0
Bank Sta=244,276.5
XS Rating Curve= 0 ,0
Exp/Cntr=0.3,0.1

Type RM Length L Ch R = 1 ,44979   ,127.2,122.1,108.2
XS GIS Cut Line= 4
     2076051.693      233603.135     2076096.181      233706.217
     2076280.643      233802.788     2076366.363      233801.703
#Sta/Elev= 30
       0 1671.58    13.2 1669.68    41.8 1664.81    70.4 1659.45    95.2 1654.17
   109.7 1652.46   129.7 1651.39   180.8 1649.94   192.9 1649.28   219.3 1649.14
   245.2 1648.18   255.41648.292   258.5 1647.69   263.4 1645.76   265.8 1645.24
   276.9 1644.46   280.4 1645.12     2881648.218   293.4 1649.06   302.3 1649.46
   308.2 1650.87   311.9 1651.37     326  1650.9   329.3 1651.18   339.4 1653.84
   358.8 1659.83   375.2 1663.22   388.3 1666.77   398.2 1668.69   406.2 1670.67
#Mann= 4 ,-1 , 0
       0      .1       0  242.27     .04       0   255.4    .045       0
     288     .04       0
#XS Ineff= 2 , 0
          125.25 1654.25
Permanent Ineff=
       F       F
Bank Sta=255.4,288
XS Rating Curve= 0 ,0
Exp/Cntr=0.5,0.3

Type RM Length L Ch R = 1 ,44857   ,31.3,33.8,33.2
XS GIS Cut Line= 5
      2075929.08       233764.81     2076071.224      233842.935
     2076124.393      233859.211     2076185.157      233865.722
     2076358.768      233827.744
#Sta/Elev= 30
       0 1668.78    14.3 1665.73    30.1 1664.26    39.3 1662.85    44.3  1662.6
      63 1660.24    89.2 1654.88   115.4 1651.09   126.7 1651.01   170.8 1649.41
   184.5 1649.37   225.4 1647.61   230.71646.912   238.6 1644.92   241.9 1644.72
   262.81646.732   268.3 1647.79   274.3  1648.2   291.6 1647.99   315.1 1648.63
   321.8 1649.04     342    1651   375.7 1652.75   392.4 1652.45   395.7 1652.84
   405.8 1654.88   419.8 1658.23   432.7  1661.7   446.1 1663.81   456.6 1666.07
#Mann= 3 ,-1 , 0
       0      .1       0   230.7    .045       0   262.8     .04       0
#XS Ineff= 2 , 0
          226.77 1648.76  268.18         1648.83
Permanent Ineff=
       F       F
Bank Sta=230.7,262.8
XS Rating Curve= 0 ,0
Exp/Cntr=0.5,0.3

Type RM Length L Ch R = 1 ,44823   ,270.1,252,220.7
XS GIS Cut Line= 5
     2075913.889      233797.363     2076062.544      233878.743
     2076123.308      233889.593     2076184.072      233896.104
     2076357.683      233858.126
#Sta/Elev= 30
       0 1673.67    20.4 1668.56    31.6 1666.81    39.1 1666.26    65.2 1661.62
    76.5 1659.03    94.2  1653.9      99 1653.02   112.7  1652.1   125.2 1650.26
   133.2 1649.68   153.7 1649.59   177.5 1647.96   206.6 1647.64   225.6 1647.98
   231.2  1646.1   231.2 1646.08   236.6 1643.75   239.9 1643.54   263.4 1646.41
   272.8  1647.3   289.4 1646.63   302.8 1646.75   326.3 1649.54   359.8 1652.08
   413.6 1654.21   430.4 1654.46   445.8 1657.38     464  1659.6     470 1659.85
#Mann= 4 ,-1 , 0
       0      .1       0     140     .04       0   231.2    .045       0
   263.4     .04       0
#XS Ineff= 2 , 0
          229.29 1647.82  272.22         1647.82
Permanent Ineff=
       F       F
Bank Sta=231.2,263.4
XS Rating Curve= 0 ,0
Exp/Cntr=0.5,0.3

Type RM Length L Ch R = 1 ,44571   ,184.4,177.6,164.7
XS GIS Cut Line= 2
     2076007.719      234241.156     2076356.677       233864.42
#Sta/Elev= 30
       0 1684.83    17.7 1682.85    71.8 1675.37   110.8 1668.01   124.2  1663.8
   146.6 1655.32   150.1 1653.82     157 1649.15   166.81644.807   173.4 1642.84
     178 1642.03   182.8 1641.91   187.2 1642.11   199.5 1645.26   204.7 1645.93
   261.5 1646.41   276.2 1646.15   293.8 1644.33     301 1644.63   317.2 1646.05
   349.7 1646.56     366 1647.15   409.7 1650.88   446.2 1651.89   472.8 1653.27
   482.1 1655.22   495.4 1655.36   498.3 1656.19   504.3 1658.55   513.5 1658.98
#Mann= 4 ,-1 , 0
       0    .035       0   166.8    .045       0   199.5    .035       0
     390     .04       0
Bank Sta=166.8,199.5
XS Rating Curve= 0 ,0
Exp/Cntr=0.3,0.1

Type RM Length L Ch R = 1 ,44394   ,326.4,318.1,291
XS GIS Cut Line= 2
      2076230.73      234254.177     2076359.853      233871.147
#Sta/Elev= 30
       0 1673.56     9.5 1671.43    19.9  1671.8    43.1 1665.62    53.4 1661.32
    63.8 1655.82    82.2 1647.55    89.1 1644.64    92.6 1643.64      96 1643.33
   106.4 1644.29   134.1 1644.92   154.4 1644.72   165.3 1644.27   172.81642.352
   179.1 1640.29   182.6 1640.14   189.5 1641.44   203.4 1641.95   208.61642.797
   217.2 1644.19   224.2  1646.5   227.6 1646.77   245.3 1647.02   369.6 1653.36
     373 1653.68     380  1655.5   393.8 1655.82   400.7 1658.49   404.2 1658.82
#Mann= 5 ,-1 , 0
       0      .1       0   172.8    .045       0   208.6      .1       0
     210    .035       0     310     .04       0
Bank Sta=172.8,208.6
XS Rating Curve= 0 ,0
Exp/Cntr=0.3,0.1

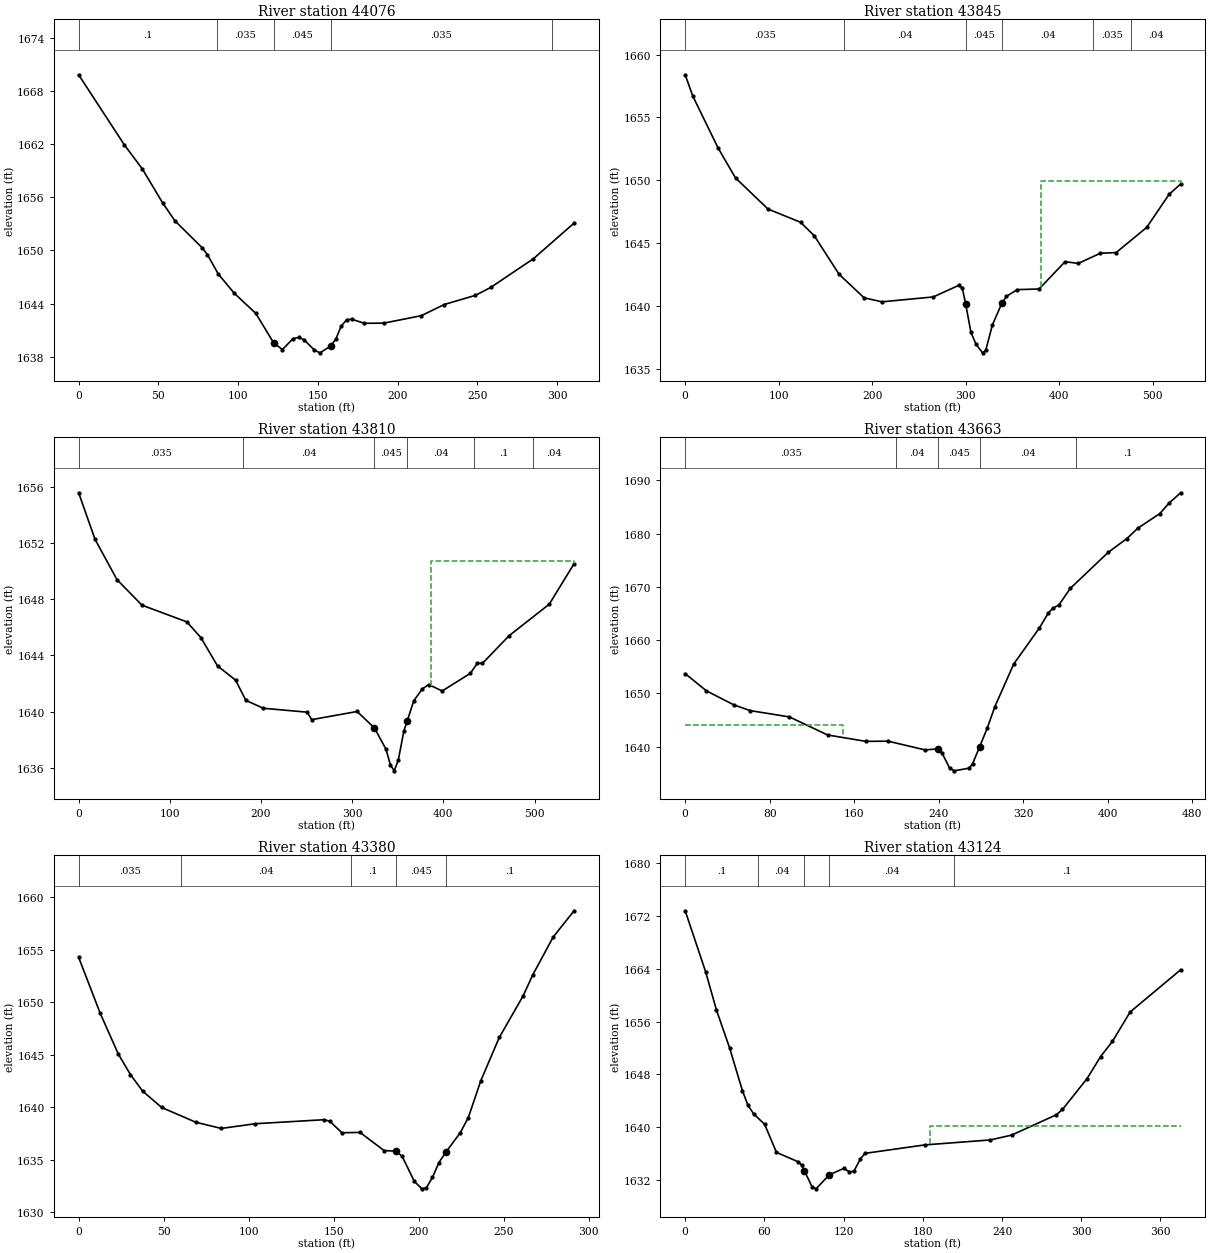
Type RM Length L Ch R = 1 ,44076   ,243.4,230.6,208.2
XS GIS Cut Line= 3
     2076525.869      234241.156     2076548.655      234157.606
     2076503.777      233938.031
#Sta/Elev= 30
       0 1669.81    28.6 1661.93      40 1659.18    52.6 1655.39    60.4 1653.34
    77.4 1650.32    80.8 1649.52    87.6 1647.34    97.7 1645.16   111.1 1642.91
   122.31639.587   127.8 1638.83   134.5 1640.07   137.9 1640.19   141.2 1639.95
   147.9 1638.77   151.3 1638.46   158.1 1639.22   161.3 1640.02   164.6 1641.44
     168 1642.19   171.3 1642.25   179.2 1641.79   191.4 1641.81   214.9 1642.65
   229.3 1643.91   248.8 1644.94   258.4 1645.83   285.2 1649.07   310.7 1653.09
#Mann= 5 ,-1 , 0
       0      .1       0    86.6    .035       0   122.3    .045       0
   158.1    .035       0   296.6     .04       0
Bank Sta=122.3,158.1
XS Rating Curve= 0 ,0
Exp/Cntr=0.5,0.3

Type RM Length L Ch R = 1 ,43845   ,90.9,35.1,37.4
XS GIS Cut Line= 4
     2076685.721      234298.448     2076805.165       234095.67
     2076683.638      233975.531     2076563.499      233947.059
#Sta/Elev= 30
       0 1658.39     8.2 1656.69    35.2 1652.57    53.8  1650.2    88.5 1647.73
   123.3 1646.68     138 1645.61   164.6 1642.54   191.3 1640.68   210.3 1640.36
   265.3 1640.75   292.5 1641.67   296.2 1641.48   299.8 1640.22   305.5 1637.93
     311 1636.98     318 1636.31   321.3 1636.51   328.5 1638.54   338.51640.231
   343.5  1640.8   355.1 1641.33   378.3 1641.38   406.2 1643.55   420.2 1643.41
   443.9 1644.22   460.7 1644.27   493.4 1646.27   517.3 1648.89   529.7 1649.72
#Mann= 6 ,-1 , 0
       0    .035       0     170     .04       0   299.8    .045       0
   338.5     .04       0  436.23    .035       0  476.23     .04       0
#XS Ineff= 2 , 0
                          380.58         1649.92
Permanent Ineff=
       F       F
Bank Sta=299.8,338.5
XS Rating Curve= 0 ,0
Exp/Cntr=0.5,0.3

Type RM Length L Ch R = 1 ,43810   ,53.8,146.8,179
XS GIS Cut Line= 5
     2076708.464      234305.045     2076837.804      234084.559
     2076756.902      233998.795     2076707.422      233957.649
      2076605.86      233929.524
#Sta/Elev= 30
       0 1655.56      18 1652.25      42 1649.39    69.4 1647.57   118.7 1646.38
   134.1 1645.26   152.3 1643.25   172.1 1642.24   183.4  1640.8   202.5 1640.24
   250.6 1639.96   255.6 1639.43   305.4 1640.01   324.41638.837     337 1637.33
   341.9 1636.21     346 1635.79   350.5 1636.54   356.7 1638.64   360.4 1639.35
   367.5 1640.77   376.8 1641.61   383.8 1641.92   398.7 1641.47   429.5 1642.72
   437.3 1643.45   442.8 1643.43   471.9 1645.39   516.1 1647.64   543.3 1650.52
#Mann= 6 ,-1 , 0
       0    .035       0     180     .04       0   324.4    .045       0
   360.4     .04       0  433.52      .1       0  497.88     .04       0
#XS Ineff= 2 , 0
                          385.88         1650.69
Permanent Ineff=
       F       F
Bank Sta=324.4,360.4
XS Rating Curve= 0 ,0
Exp/Cntr=0.5,0.3

Type RM Length L Ch R = 1 ,43663   ,271.7,283.4,301.1
XS GIS Cut Line= 2
     2076722.997      234312.336     2077018.136      233947.753
#Sta/Elev= 30
       0 1653.71    20.1 1650.48    46.1 1647.84    61.4 1646.77    98.7 1645.58
   134.8 1642.19     171 1640.99   192.1 1641.02     227 1639.39   239.51639.565
   243.3 1638.75   250.3    1636   254.7 1635.45     269 1635.96   272.1 1636.78
   278.8 1639.98     286 1643.48   293.2 1647.51     311  1655.5   335.4  1662.3
   343.9 1665.13   348.1 1665.99   353.8 1666.61   364.6 1669.72   400.7 1676.53
   418.3  1679.1   428.3    1681   449.4 1683.78   457.9  1685.7   469.1 1687.69
#Mann= 5 ,-1 , 0
       0    .035       0     200     .04       0   239.5    .045       0
   278.8     .04       0     370      .1       0
#XS Ineff= 2 , 0
          148.99 1644.06
Permanent Ineff=
       F       F
Bank Sta=239.5,278.8
XS Rating Curve= 0 ,0
Exp/Cntr=0.3,0.1

Type RM Length L Ch R = 1 ,43380   ,259.7,256.1,244.1
XS GIS Cut Line= 2
     2076805.903      234451.399     2077075.001      234339.637
#Sta/Elev= 30
       0 1654.26    12.7 1648.93    23.4 1645.03    30.5 1643.09    37.6 1641.53
    48.8 1639.97    68.9 1638.56    83.9 1637.97     104 1638.42   144.2  1638.8
   147.7 1638.66   154.8 1637.56   165.5 1637.59   179.7 1635.86   186.61635.812
   190.3 1635.31   197.4 1632.94   201.9 1632.22   204.5 1632.31   208.1 1633.31
   211.9 1634.72   216.11635.736   224.5 1637.57   229.2 1639.01   236.5  1642.5
   247.4 1646.63   261.4 1650.58   267.1 1652.59   279.1 1656.19   291.4 1658.69
#Mann= 5 ,-1 , 0
       0    .035       0      60     .04       0     160      .1       0
   186.6    .045       0   216.1      .1       0
Bank Sta=186.6,216.1
XS Rating Curve= 0 ,0
Exp/Cntr=0.3,0.1

Type RM Length L Ch R = 1 ,43124   ,223.4,228,220.4
XS GIS Cut Line= 5
2076968.88624019234684.0305306162077010.55541759234647.527047099
2077090.76287216234591.4617718482077080.39771047234509.188300899
2077175.39232495234407.549290424
#Sta/Elev= 30
       01672.786  15.482 1663.55  23.705 1657.74  33.6631652.002  43.3821645.516
  47.5341643.323  51.8961642.007   60.19 1640.44  69.1371636.184   85.631634.759
   88.211634.266  90.3421633.382  96.216 1630.92  99.1181630.663  109.191632.794
 120.2331633.764 124.2361633.252 127.7511633.302  132.751635.223 136.2451636.037
 181.5171637.319 231.1181638.069 247.2681638.804 281.1621641.885 285.8051642.694
 304.3741647.348 314.6291650.687  323.611652.997 337.0821657.462 375.3011663.847
#Mann= 5 ,-1 , 0
       0      .1       0    55.4     .04       0  90.342    .045       0
  109.19     .04       0  203.26      .1       0
#XS Ineff= 2 , 0
                          185.66         1640.12
Permanent Ineff=
       F       F
Bank Sta=90.342,109.19
XS Rating Curve= 0 ,0
Exp/Cntr=0.3,0.1

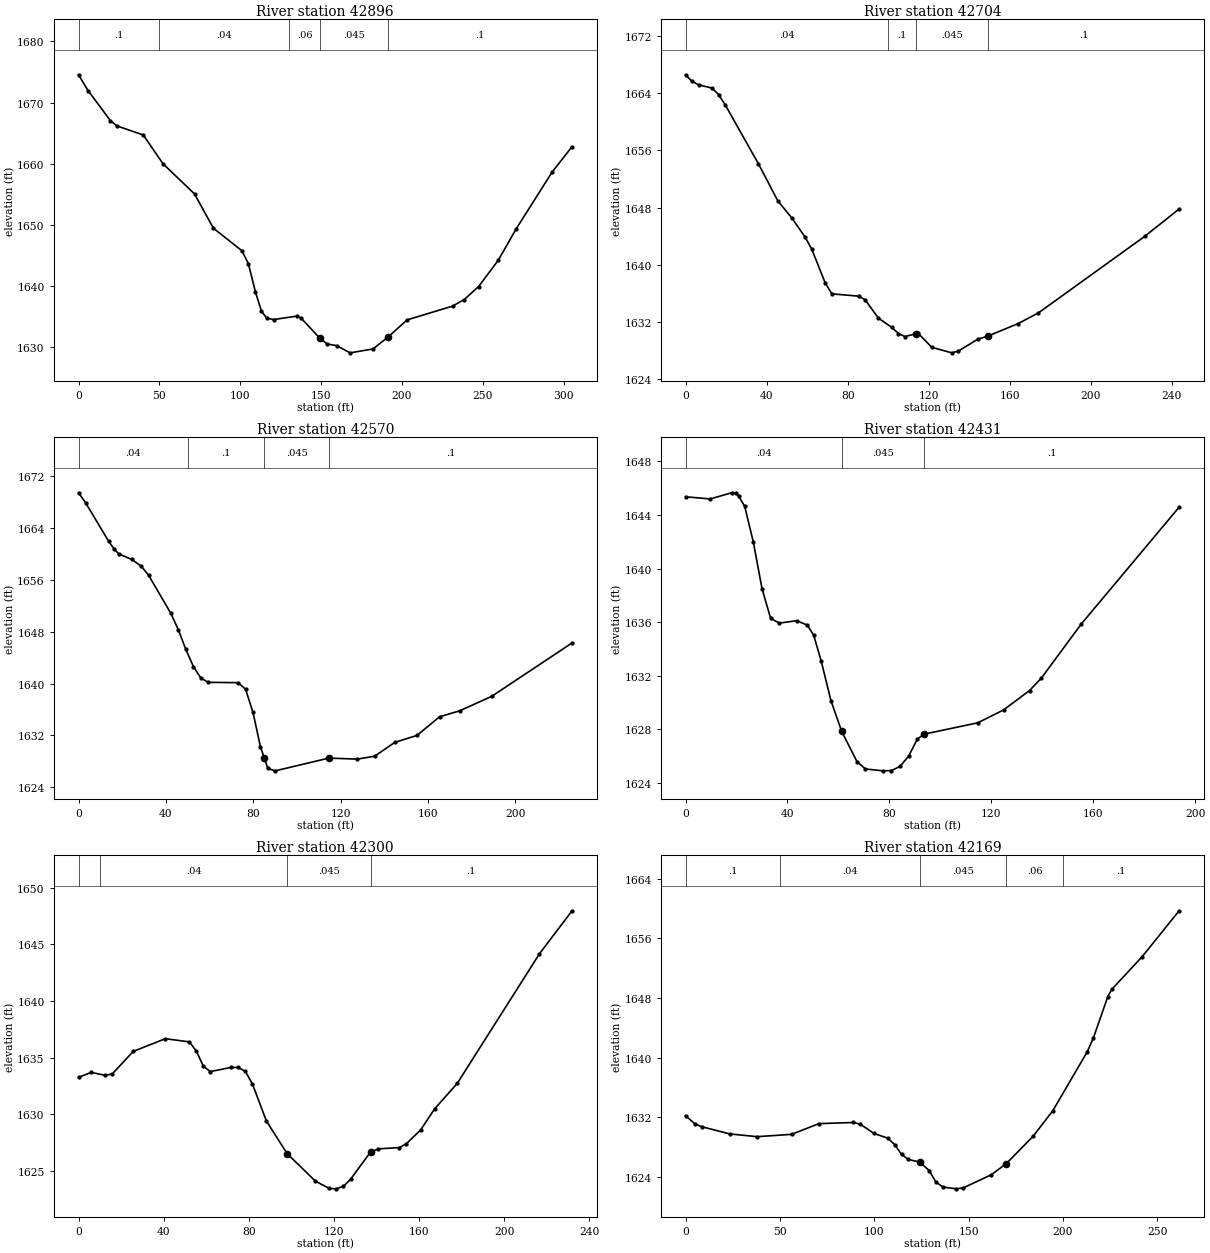
Type RM Length L Ch R = 1 ,42896   ,175,192,208.4
XS GIS Cut Line= 2
     2077110.157       234824.88     2077356.468      234644.758
#Sta/Elev= 30
       0 1674.53     5.9 1671.95    19.7 1667.04    23.7 1666.18      40  1664.7
    52.2    1660    71.7 1655.07    83.4 1649.46     101 1645.79     105 1643.67
   109.4 1639.02   113.1 1635.91   116.3 1634.79   120.6 1634.55   135.1 1635.11
   137.5 1634.81   149.3 1631.46   153.8 1630.55   159.5 1630.29   167.9 1629.11
     182 1629.74   191.51631.723   203.1 1634.49   231.3 1636.75   238.4 1637.81
   247.3 1639.93   259.5 1644.24   270.6 1649.39   292.9 1658.68   305.1 1662.79
#Mann= 5 ,-1 , 0
       0      .1       0      50     .04       0     130     .06       0
   149.3    .045       0   191.5      .1       0
Bank Sta=149.3,191.5
XS Rating Curve= 0 ,0
Exp/Cntr=0.3,0.1

Type RM Length L Ch R = 1 ,42704   ,135.6,133.3,123.5
XS GIS Cut Line= 2
      2077155.73        234910.6     2077398.785      234894.324
#Sta/Elev= 30
       0 1666.62     3.1 1665.72     6.4 1665.21      13 1664.76    16.3 1663.84
    19.6 1662.39      36 1654.12    45.5 1648.96    52.4 1646.55      59 1643.87
    62.3 1642.16    68.9 1637.44    72.2  1635.9    85.6 1635.56    88.6 1635.07
    95.2 1632.49   101.8 1631.18   105.1 1630.33   108.3  1629.9   113.71630.296
   114.9 1630.34   121.5  1628.4   131.4 1627.62   134.6 1627.86   144.1 1629.51
   149.41629.987   164.2 1631.73   174.1 1633.21   226.7 1643.97   243.6 1647.79
#Mann= 4 ,-1 , 0
       0     .04       0     100      .1       0   113.7    .045       0
   149.4      .1       0
Bank Sta=113.7,149.4
XS Rating Curve= 0 ,0
Exp/Cntr=0.3,0.1

Type RM Length L Ch R = 1 ,42570   ,138.7,139.7,140.3
XS GIS Cut Line= 2
     2077200.218      235051.659     2077417.231      234988.725
#Sta/Elev= 30
       0 1669.45     3.2 1667.93    13.8 1661.96    16.4 1660.74    18.4 1660.02
    24.4 1659.16    28.7 1658.12    32.1 1656.72    42.3 1650.82    45.7  1648.3
    49.1 1645.31    52.6 1642.63      56 1640.86    59.4 1640.19    73.1 1640.14
    76.5 1639.12    79.9 1635.54    83.3 1630.24    85.11628.477    86.7  1626.9
    90.1 1626.53   114.61628.495   127.7 1628.34   135.6 1628.79   144.8 1630.92
     155    1632   165.3 1634.87   174.5 1635.79   189.2 1638.03     226 1646.27
#Mann= 4 ,-1 , 0
       0     .04       0      50      .1       0    85.1    .045       0
   114.6      .1       0
Bank Sta=85.1,114.6
XS Rating Curve= 0 ,0
Exp/Cntr=0.3,0.1

Type RM Length L Ch R = 1 ,42431   ,125.3,130.3,134.9
XS GIS Cut Line= 2
     2077260.981      235176.442     2077448.698      235128.699
#Sta/Elev= 30
       0 1645.36     9.7  1645.2    18.1 1645.66    19.9 1645.66    20.8 1645.42
    23.2 1644.65    26.6 1641.98      30  1638.5    33.4 1636.27    36.8 1635.92
    43.6  1636.1    47.8 1635.77    50.3 1635.01    53.2 1633.11    57.1  1630.1
    61.3 1627.82    67.3 1625.56    70.6 1625.02    77.5 1624.88    80.8  1624.9
    84.2 1625.21    87.6    1626      91 1627.26    93.61627.621   114.7 1628.47
   124.8 1629.43     135 1630.88   139.6  1631.8   155.3 1635.85   193.7 1644.58
#Mann= 3 ,-1 , 0
       0     .04       0    61.3    .045       0    93.6      .1       0
Bank Sta=61.3,93.6
XS Rating Curve= 0 ,0
Exp/Cntr=0.3,0.1

Type RM Length L Ch R = 1 ,42300   ,117.3,131.5,150.7
XS GIS Cut Line= 2
      2077241.45       235293.63      2077472.57      235275.184
#Sta/Elev= 30
       0 1633.26       6  1633.7    12.6 1633.43    15.9 1633.57    25.7 1635.55
    40.8 1636.67    52.1 1636.39    55.4 1635.56    58.7 1634.23    61.9 1633.77
    71.8 1634.14    75.1 1634.13    78.4 1633.78    81.7 1632.68    88.3  1629.4
      981626.532   111.3  1624.1   117.9 1623.45   121.2 1623.42   124.5 1623.65
   127.8 1624.26   137.21626.665   140.9 1626.95   150.8 1627.06   154.1 1627.41
   160.7 1628.61   167.3 1630.47     178 1632.74   216.6 1644.17   231.9 1647.96
#Mann= 4 ,-1 , 0
       0      .1       0      10     .04       0      98    .045       0
   137.2      .1       0
Bank Sta=98,137.2
XS Rating Curve= 0 ,0
Exp/Cntr=0.3,0.1

Type RM Length L Ch R = 1 ,42169   ,147.2,160.4,176.5
XS GIS Cut Line= 2
     2077209.983      235352.224     2077445.443      235466.156
#Sta/Elev= 30
       0 1632.24     5.1 1631.12     8.8 1630.75    23.4  1629.8    37.9 1629.43
    56.2 1629.74    70.7 1631.18      89 1631.33    92.6  1631.1    99.9 1629.86
   107.2 1629.23   110.8 1628.38   114.5 1627.05   118.1 1626.38   124.21626.022
   129.1 1624.89   132.7 1623.36   136.4 1622.68   143.6 1622.44   147.3 1622.58
   162.1 1624.33     170 1625.82   184.2 1629.48   194.7 1632.92   212.9  1640.8
   216.1 1642.61   223.8 1648.18   225.9 1649.17   242.1 1653.57   261.6  1659.7
#Mann= 5 ,-1 , 0
       0      .1       0      50     .04       0   124.2    .045       0
     170     .06       0     200      .1       0
Bank Sta=124.2,170
XS Rating Curve= 0 ,0
Exp/Cntr=0.3,0.1

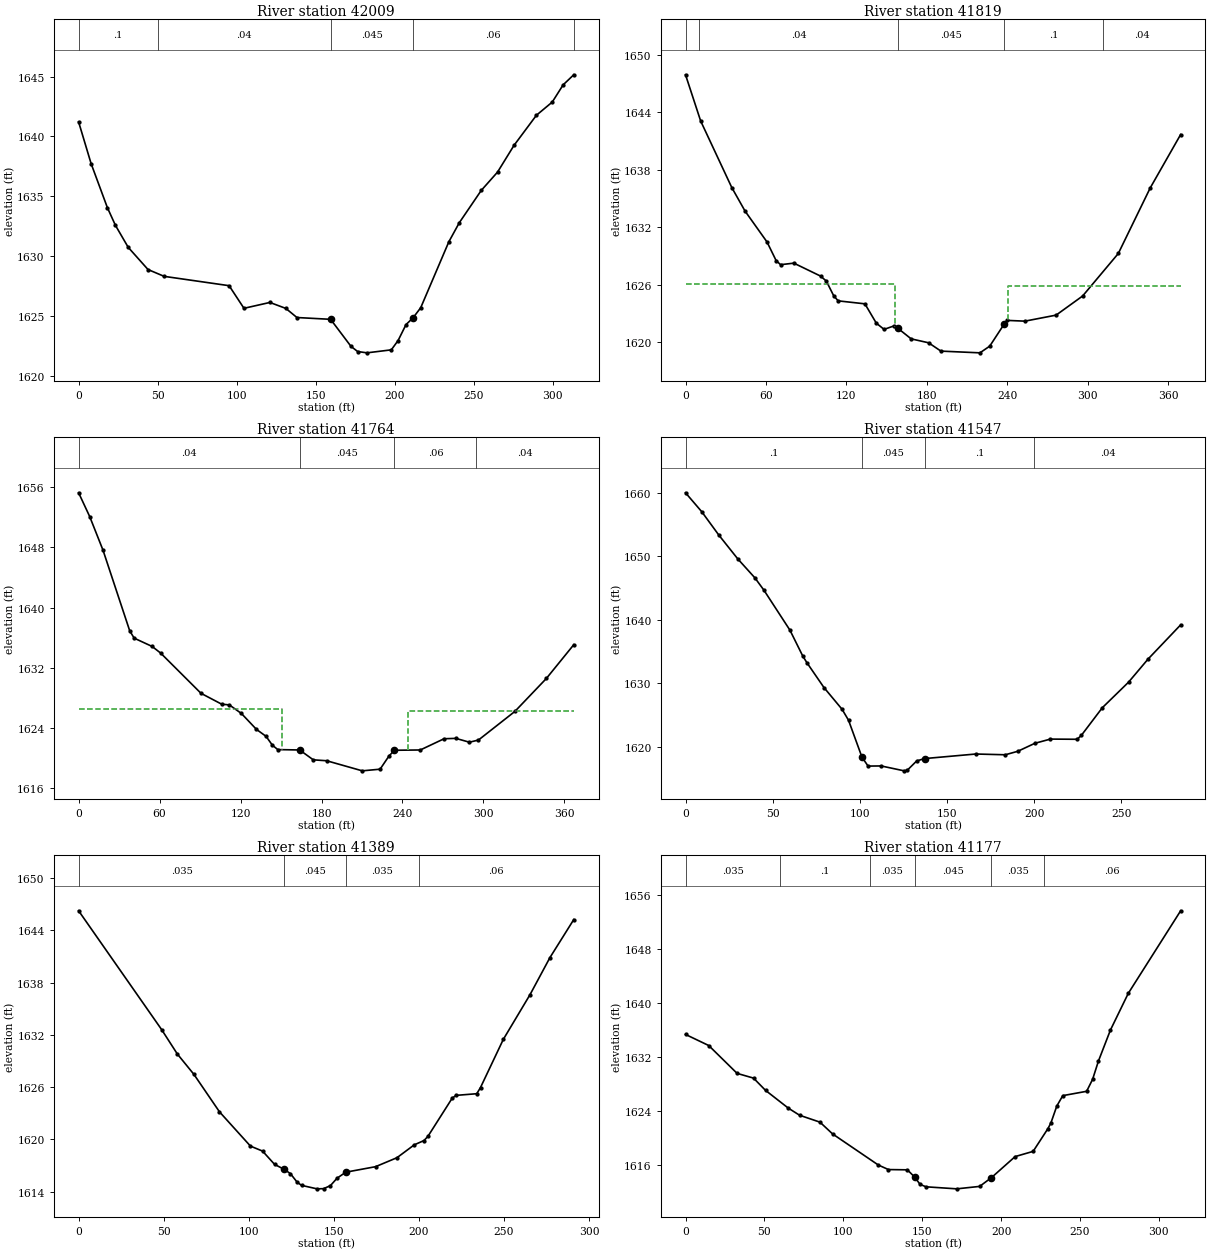
Type RM Length L Ch R = 1 ,42009   ,125.6,189.7,221.5
XS GIS Cut Line= 3
     2077127.518      235402.137     2077277.257      235582.258
     2077352.127      235607.215
#Sta/Elev= 30
       0 1641.21     7.9 1637.73    18.2 1634.05    23.3 1632.57    31.4 1630.73
    43.9 1628.88    54.1 1628.31    95.2 1627.53   104.6 1625.64     121 1626.13
   131.1 1625.63   138.1 1624.87   159.4 1624.72   172.3 1622.46   176.5 1622.03
   182.4 1621.92   197.8 1622.17   202.1 1622.95   207.1 1624.28   211.51624.838
   216.4 1625.69   234.2  1631.2   240.8 1632.79   254.7 1635.49     265 1637.02
   275.4 1639.25   289.6 1641.77   299.6 1642.87   306.5 1644.31   313.2 1645.15
#Mann= 5 ,-1 , 0
       0      .1       0      50     .04       0   159.4    .045       0
   211.5     .06       0  313.15      .1       0
Bank Sta=159.4,211.5
XS Rating Curve= 0 ,0
Exp/Cntr=0.5,0.3

Type RM Length L Ch R = 1 ,41819   ,77.2,54.9,43.1
XS GIS Cut Line= 5
     2077091.711      235431.434     2077110.157      235572.493
      2077087.37       235603.96     2077081.945      235663.639
     2077100.391      235790.592
#Sta/Elev= 30
       0 1647.94    11.3 1643.11    34.5 1636.16    44.4  1633.7    60.8 1630.47
    67.6 1628.52    70.9  1628.1    80.8 1628.26   100.7 1626.91     105 1626.39
   110.6 1624.83   113.9 1624.32   133.8 1624.01   142.3 1621.99   148.1 1621.34
   155.4  1621.7   158.41621.454   168.3 1620.35   181.3 1619.94   190.5 1619.07
   219.6 1618.89   226.9 1619.59   237.91621.944   239.9 1622.28   253.1  1622.2
   276.4 1622.83   296.2 1624.83   322.8 1629.27   346.6 1636.12   369.3  1641.7
#Mann= 5 ,-1 , 0
       0      .1       0      10     .04       0   158.4    .045       0
   237.9      .1       0  311.04     .04       0
#XS Ineff= 2 , 0
          156.36 1626.07   240.4         1625.84
Permanent Ineff=
       F       F
Bank Sta=158.4,237.9
XS Rating Curve= 0 ,0
Exp/Cntr=0.5,0.3

Type RM Length L Ch R = 1 ,41764   ,263.5,217.2,182.8
XS GIS Cut Line= 5
     2077052.648      235450.965     2077065.669      235556.217
     2077042.882      235587.684     2077037.457      235647.363
     2077059.159      235807.953
#Sta/Elev= 30
       0 1655.23     8.2 1652.08    18.1  1647.6    37.9 1636.89    41.2 1635.93
    54.5 1634.83    60.8 1633.95    90.7 1628.61     106 1627.17   111.7 1627.07
   120.6 1625.94   131.8 1623.82   138.9  1622.9   143.6 1621.72   147.6 1621.14
   163.8 1621.09   173.9 1619.78   183.8 1619.66   210.2 1618.32   223.4 1618.54
     230 1620.29     234 1621.05   253.2 1621.09   270.8 1622.58   279.5 1622.63
   289.6 1622.12   296.3 1622.41   323.3 1626.21   346.6 1630.58   366.9 1635.06
#Mann= 4 ,-1 , 0
       0     .04       0   163.8    .045       0     234     .06       0
  294.83     .04       0
#XS Ineff= 2 , 0
          150.71 1626.55  244.44         1626.25
Permanent Ineff=
       F       F
Bank Sta=163.8,234
XS Rating Curve= 0 ,0
Exp/Cntr=0.5,0.3

Type RM Length L Ch R = 1 ,41547   ,155.1,157.7,159.5
XS GIS Cut Line= 2
     2076778.126      235718.977     2077027.692      235854.611
#Sta/Elev= 30
       0 1660.03     9.3 1657.05    19.1 1653.37      30 1649.61    39.8 1646.63
      45 1644.68    59.9 1638.39    67.3 1634.29    69.7 1633.24    79.4 1629.36
    89.8 1625.93    93.5 1624.21   101.2  1618.4   104.7 1616.99   112.2 1617.01
   125.4 1616.24   127.1 1616.31   132.6  1617.8   137.11618.171   166.5 1618.89
   183.4 1618.77   190.6 1619.32   200.4 1620.58   209.3 1621.24   224.6 1621.21
     227 1621.81   239.1 1626.19   254.1  1630.2   265.3 1633.84     284 1639.23
#Mann= 4 ,-1 , 0
       0      .1       0   101.2    .045       0   137.1      .1       0
     200     .04       0
Bank Sta=101.2,137.1
XS Rating Curve= 0 ,0
Exp/Cntr=0.3,0.1

Type RM Length L Ch R = 1 ,41389   ,213.9,212.2,211
XS GIS Cut Line= 2
     2076690.235       235837.25     2076934.376       235995.67
#Sta/Elev= 30
       0 1646.23    48.8  1632.6      58 1629.81    67.8 1627.46    82.8 1623.17
     101 1619.24   108.1 1618.67   115.2 1617.14     1211616.559   124.5 1616.08
   128.4 1615.11     131 1614.74   140.1 1614.34     144 1614.36     148 1614.71
   151.9 1615.56     1571616.248   174.5 1616.88   187.1 1617.91   197.3 1619.39
     203 1619.88   205.3 1620.36   219.6 1624.75   221.9 1625.06     234 1625.25
   236.2 1625.96   249.6 1631.48   265.3 1636.61     277 1640.86     291 1645.22
#Mann= 4 ,-1 , 0
       0    .035       0     121    .045       0     157    .035       0
     200     .06       0
Bank Sta=121,157
XS Rating Curve= 0 ,0
Exp/Cntr=0.3,0.1

Type RM Length L Ch R = 1 ,41177   ,196.3,219.2,238.2
XS GIS Cut Line= 3
     2076600.174      235980.479     2076635.981      236059.689
     2076833.464      236171.451
#Sta/Elev= 30
       0 1635.33    14.7 1633.69    32.7 1629.57    43.1 1628.87    50.7 1627.06
    65.1 1624.44    72.3 1623.38    85.2 1622.36    93.2 1620.62   122.2 1616.02
   128.6 1615.35   140.6 1615.31   145.3 1614.22   148.6 1613.17   152.4  1612.8
   171.9  1612.5   186.4 1612.86   193.9 1614.16   208.9 1617.27   220.3 1618.04
   229.7 1621.41   231.6 1622.26   235.3 1624.74   239.1 1626.28   254.2 1626.92
     258 1628.69   261.7  1631.4   269.3 1635.98   280.6  1641.4   313.8 1653.61
#Mann= 6 ,-1 , 0
       0    .035       0      60      .1       0  116.93    .035       0
   145.3    .045       0   193.9    .035       0  226.93     .06       0
Bank Sta=145.3,193.9
XS Rating Curve= 0 ,0
Exp/Cntr=0.3,0.1

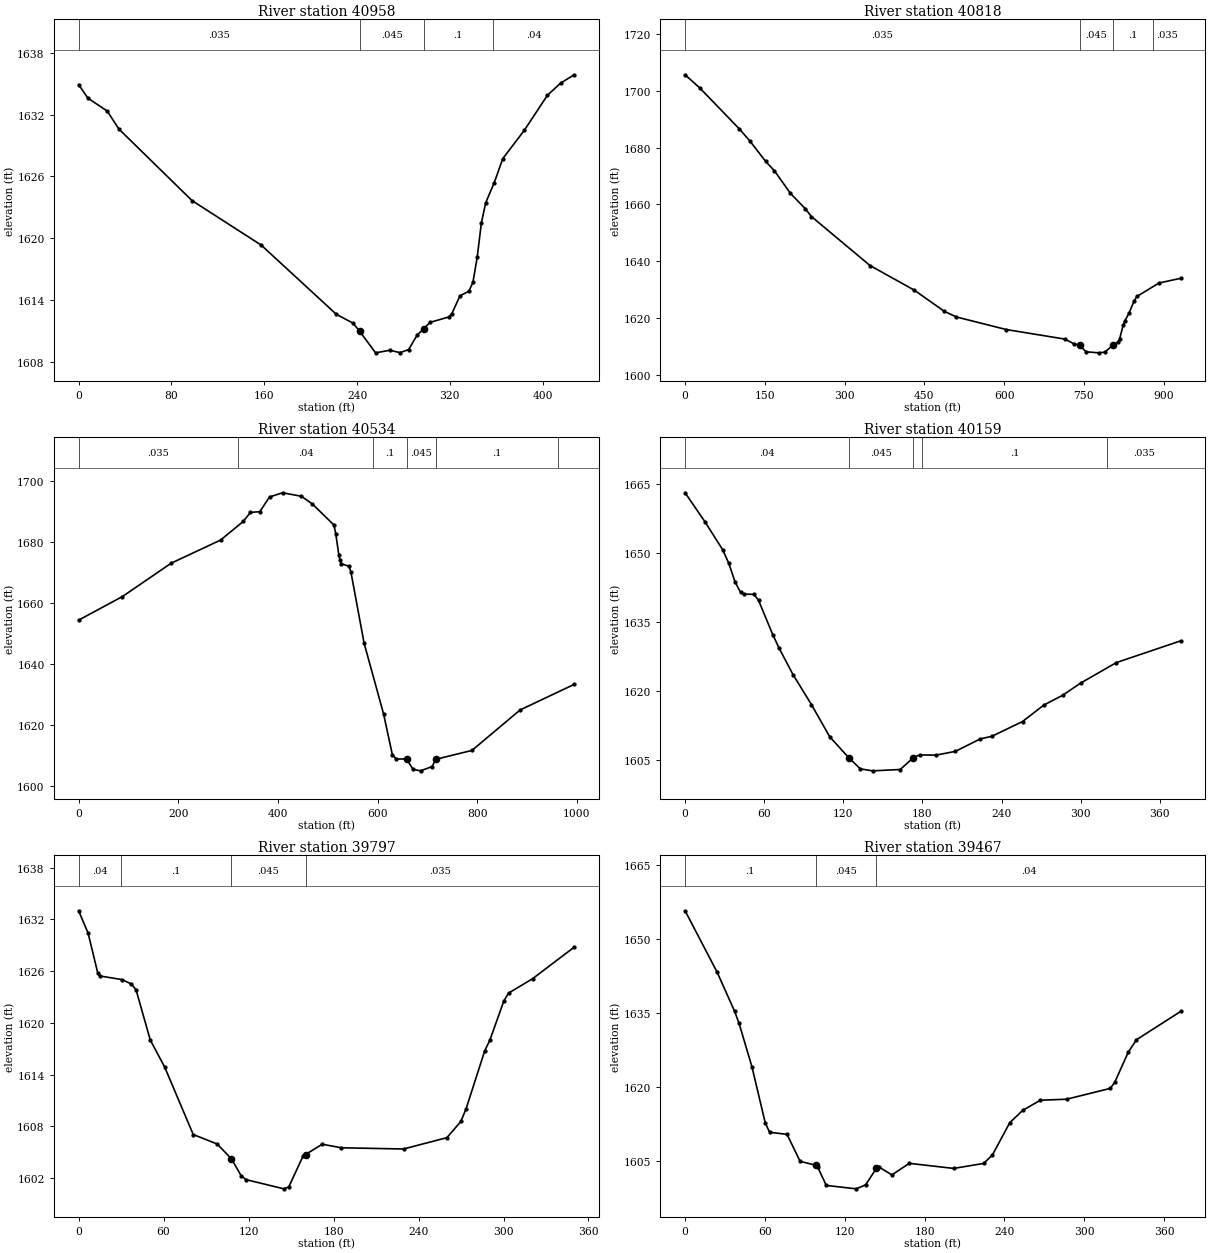
Type RM Length L Ch R = 1 ,40958   ,132.6,139.3,141.3
XS GIS Cut Line= 3
     2076545.445      235992.449     2076518.143      236167.545
     2076632.726      236389.767
#Sta/Elev= 30
       0 1634.92     8.1  1633.6    24.7 1632.35    34.6 1630.62    97.7 1623.66
   157.5 1619.32   222.2  1612.6   236.5 1611.75   242.2 1610.97     256 1608.86
   268.2 1609.11   277.1 1608.88   284.5 1609.18   291.9  1610.6   297.4 1611.18
   302.9 1611.82   319.3 1612.35   321.8 1612.68   328.8 1614.41   336.4 1614.84
   339.9  1615.7   343.6 1618.14   347.2 1621.48   350.9 1623.43   358.3  1625.4
   365.7 1627.74   384.2 1630.48   404.1 1633.88   415.5 1635.07   427.2 1635.88
#Mann= 4 ,-1 , 0
       0    .035       0   242.2    .045       0   297.4      .1       0
  357.21     .04       0
Bank Sta=242.2,297.4
XS Rating Curve= 0 ,0
Exp/Cntr=0.3,0.1

Type RM Length L Ch R = 1 ,40818   ,306.8,283.9,254.1
XS GIS Cut Line= 3
2076542.50437738 235565.85507594     2076422.657      236264.767
      2076505.99      236471.364
#Sta/Elev= 30
       0 1705.65    28.2  1700.9   101.4 1686.69   121.4 1682.42   151.3 1675.18
     168 1671.82   197.9 1663.92   226.3  1658.4   237.5  1655.7   347.7 1638.44
   430.9 1629.77   487.5  1622.3   510.3  1620.3     604 1615.88   714.2 1612.51
   731.9 1610.79   741.91610.349     754 1608.04   777.8 1607.67   789.3 1607.92
   804.11610.311   814.5 1611.56   817.1 1612.61   823.8 1617.33   826.5 1618.76
   834.5 1621.55   844.8 1626.11   849.8 1627.56   891.1 1632.27   931.9 1633.93
#Mann= 4 ,-1 , 0
       0    .035       0   741.9    .045       0   804.1      .1       0
  879.11    .035       0
Bank Sta=741.9,804.1
XS Rating Curve= 0 ,0
Exp/Cntr=0.3,0.1

Type RM Length L Ch R = 1 ,40534   ,412.2,375,309.8
XS GIS Cut Line= 4
2075790.68722872 235950.424764632076029.91430092236368.469402635
     2076308.073      236528.656     2076499.046      236509.559
#Sta/Elev= 30
       0  1654.4    87.9 1662.15   186.1 1673.13   284.8 1680.69   330.4 1686.82
   344.9 1689.78   363.7 1690.03   383.2 1694.86   409.3 1696.23     447 1695.09
   469.1 1692.55   512.3 1685.66   516.1 1682.75   522.3 1675.82   524.7 1673.99
   527.5 1672.92   542.6 1672.09   546.4 1670.31   572.9 1646.88     612 1623.61
   629.7  1610.2   637.6 1608.79   658.11608.787   671.3 1605.38   686.5  1604.9
   709.2  1606.3   717.21608.703   789.5 1611.61   886.1  1624.9   994.6  1633.3
#Mann= 6 ,-1 , 0
       0    .035       0     320     .04       0  591.65      .1       0
   658.1    .045       0   717.2      .1       0  962.64    .035       0
Bank Sta=658.1,717.2
XS Rating Curve= 0 ,0
Exp/Cntr=0.3,0.1

Type RM Length L Ch R = 1 ,40159   ,377.3,362.3,339.3
XS GIS Cut Line= 2
     2076240.365      236844.628     2076499.046      236572.059
#Sta/Elev= 30
       0 1663.13      15 1656.85    28.6 1650.69    33.1 1647.79    37.9 1643.73
    42.1 1641.44    44.7 1641.07    52.2 1641.04    55.7 1639.73    66.5 1632.25
    71.3 1629.32    81.8 1623.59    95.8 1617.05   109.7 1610.03   124.21605.461
   132.9 1603.06   142.2 1602.63   163.1 1602.92   173.2 1605.51   177.8 1606.09
   190.4 1606.05     205 1606.87   223.8 1609.57   232.7 1610.15   255.9 1613.36
   272.1 1616.95   286.4 1619.08     300 1621.73   327.1 1626.19   375.8 1630.91
#Mann= 5 ,-1 , 0
       0     .04       0   124.2    .045       0   173.2     .04       0
     180      .1       0     320    .035       0
Bank Sta=124.2,173.2
XS Rating Curve= 0 ,0
Exp/Cntr=0.3,0.1

Type RM Length L Ch R = 1 ,39797   ,336.5,330,320
XS GIS Cut Line= 2
      2076622.31      237033.864     2076703.907      236693.586
#Sta/Elev= 30
       0 1633.01     6.7 1630.41    13.5  1625.8      15 1625.45    30.3 1625.04
    37.1 1624.54    40.5 1623.87    50.6 1618.02    60.7 1614.91    80.9 1607.07
    97.8 1605.97   107.9 1604.25   114.7 1602.31   118.1 1601.84     145 1600.77
   148.4    1601   158.5 1604.58   160.2 1604.75     172 1605.94   185.5 1605.53
   229.4 1605.39     260  1606.7   269.9 1608.58   273.6 1610.06   286.7 1616.75
   290.5 1618.06   300.2 1622.54   303.6 1623.47   320.5 1625.13   349.9 1628.79
#Mann= 4 ,-1 , 0
       0     .04       0      30      .1       0   107.9    .045       0
   160.2    .035       0
Bank Sta=107.9,160.2
XS Rating Curve= 0 ,0
Exp/Cntr=0.3,0.1

Type RM Length L Ch R = 1 ,39467   ,226.6,259.2,283.1
XS GIS Cut Line= 2
     2076959.115      237113.725     2076947.194      236741.481
#Sta/Elev= 30
       0 1655.76    24.1 1643.27    37.2 1635.34    40.5 1632.94    50.3 1623.99
    60.2 1612.69    63.5 1610.75    76.6 1610.33    86.4 1604.86      98 1604.06
    99.6  1603.7   106.1 1599.95   128.7 1599.26   135.7 1600.09   143.81603.445
   145.5 1603.74   155.4 1602.09   168.5 1604.44   201.8 1603.41   224.3 1604.42
   230.9 1606.12     244  1612.7   253.8 1615.22     267 1617.27   286.7 1617.47
   319.5 1619.67   322.9 1620.91     333 1627.01   339.2 1629.56   372.4  1635.3
#Mann= 3 ,-1 , 0
       0      .1       0      98    .045       0   143.8     .04       0
Bank Sta=98,143.8
XS Rating Curve= 0 ,0
Exp/Cntr=0.3,0.1