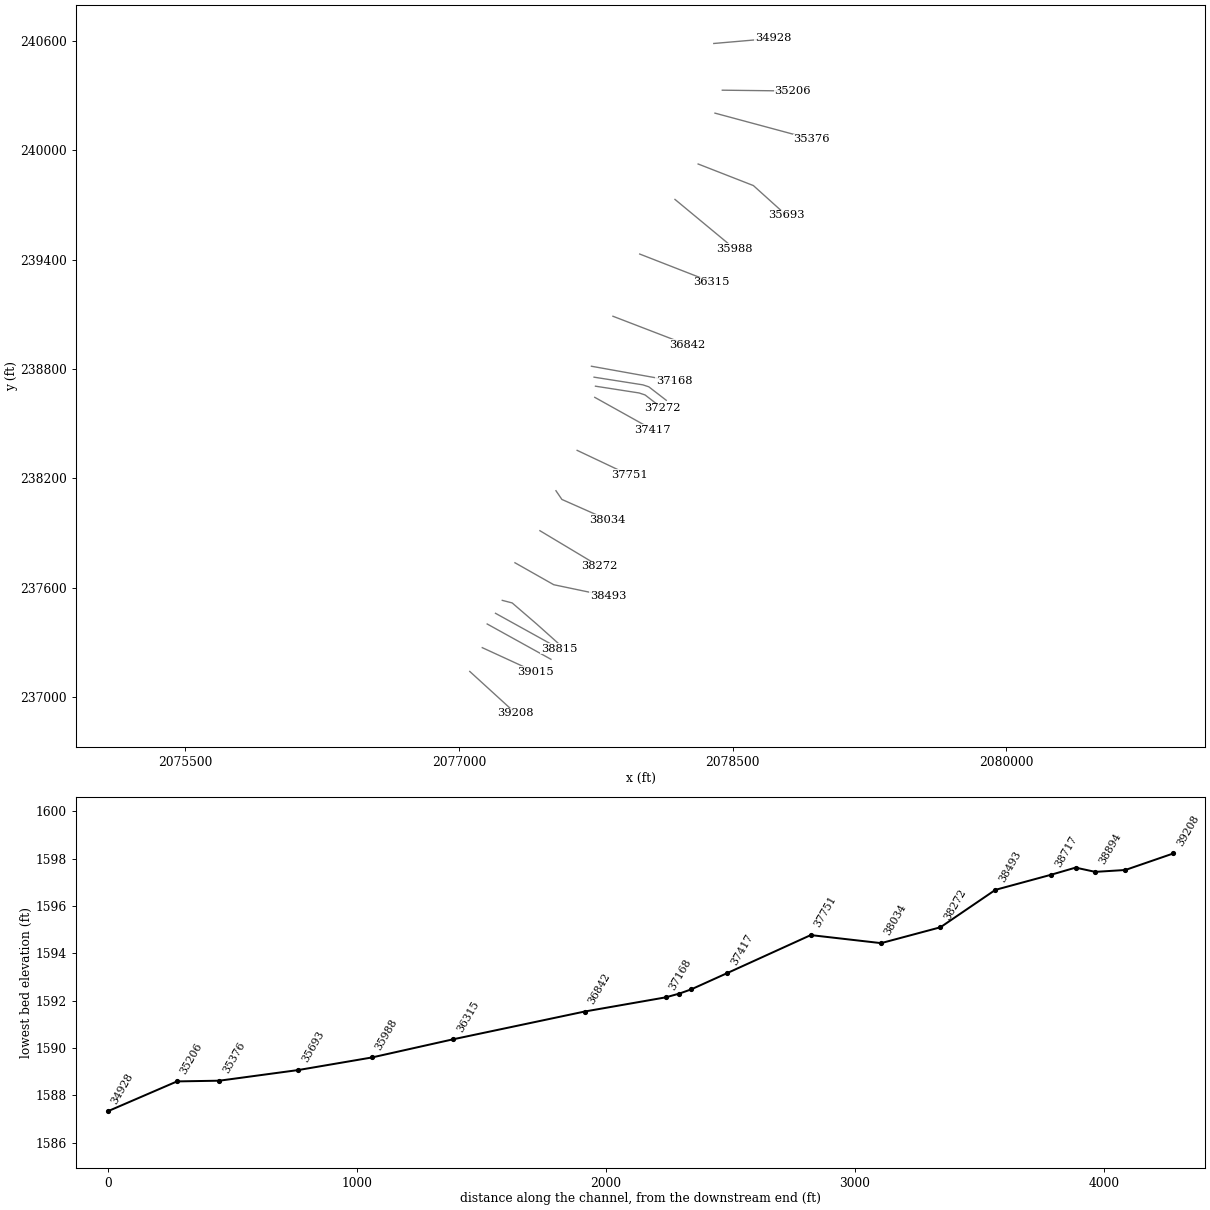
HEC-RAS study WOLFCK.prj: WOLFCK

--- WOLFCK.g01 (geometry) --- (continued)

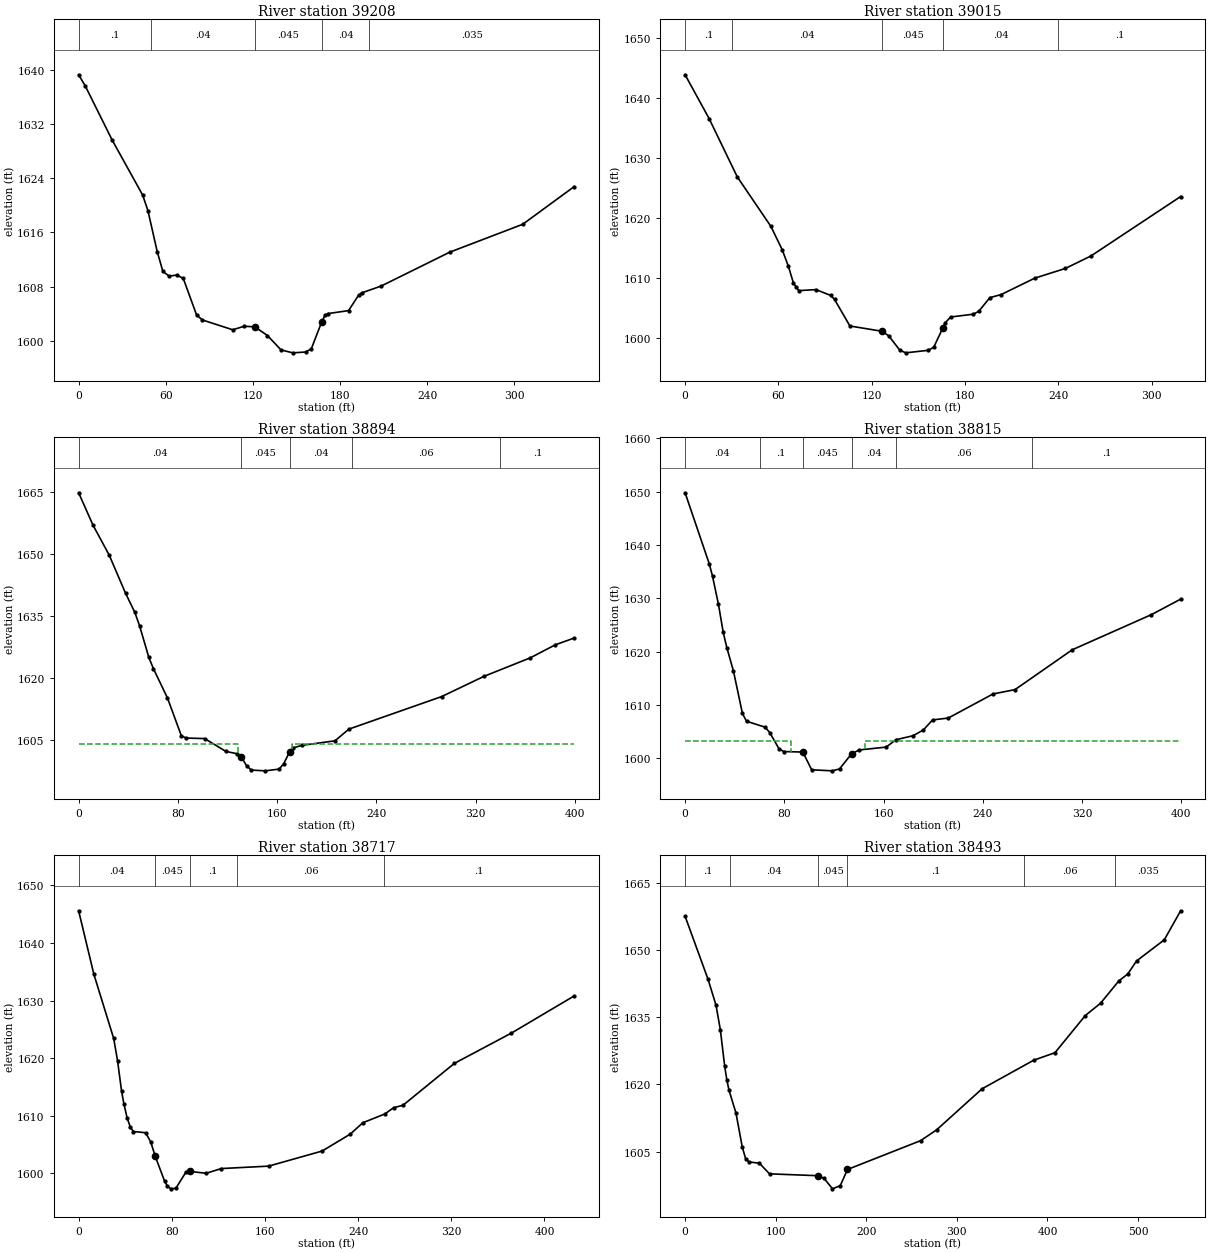
Type RM Length L Ch R = 1 ,39208   ,182.5,193.2,202
XS GIS Cut Line= 2
      2077059.81      237141.503     2077311.777       236911.62
#Sta/Elev= 30
       0 1639.25     4.6 1637.59      23 1629.65    44.1 1621.49    47.7  1619.2
    54.1 1613.15      58 1610.23    62.3 1609.54    67.4 1609.69      72 1609.22
    81.2  1603.8    85.2 1603.07   106.1 1601.62   113.8 1602.14   121.3 1602.06
     130 1600.77   139.3 1598.65   147.4 1598.22   156.3 1598.34   160.2 1598.83
   167.31602.774   169.5 1603.74   171.8 1604.02   185.8 1604.45   192.7 1606.72
     195 1607.08   208.3 1608.08   255.4 1613.07   305.7 1617.19   341.1 1622.75
#Mann= 5 ,-1 , 0
       0      .1       0      50     .04       0   121.3    .045       0
   167.3     .04       0     200    .035       0
Bank Sta=121.3,167.3
XS Rating Curve= 0 ,0
Exp/Cntr=0.3,0.1

Type RM Length L Ch R = 1 ,39015   ,123.1,120.8,118.5
XS GIS Cut Line= 2
     2077128.386      237271.928     2077417.875      237138.725
#Sta/Elev= 30
       0 1643.83    15.5 1636.51    33.5 1626.85    55.2 1618.57    62.4 1614.72
    66.4 1611.96    69.6 1609.22    71.3  1608.5    73.2 1607.88    84.1 1608.05
    93.6 1607.09    96.1 1606.42     106 1601.99   126.81601.105     131 1600.34
   138.1 1597.96   141.9 1597.52   156.3 1597.94   159.9 1598.44   165.81601.692
   167.1 1602.48   170.8 1603.49   185.2 1603.95   188.8 1604.42     196 1606.71
   203.3 1607.23   224.9 1609.96   244.5 1611.57     261 1613.65   318.7 1623.55
#Mann= 5 ,-1 , 0
       0      .1       0      30     .04       0   126.8    .045       0
   165.8     .04       0     240      .1       0
Bank Sta=126.8,165.8
XS Rating Curve= 0 ,0
Exp/Cntr=0.5,0.3

Type RM Length L Ch R = 1 ,38894   ,77.5,79,77.4
XS GIS Cut Line= 2
     2077155.296      237401.703     2077504.681       237208.17
#Sta/Elev= 30
       0 1664.84    11.6 1656.99    24.6 1649.75    37.8  1640.5    45.3 1635.85
    49.1 1632.61    56.6 1624.92    60.3 1622.19    71.6  1615.1    82.8 1605.93
    86.6 1605.39   101.6 1605.26   118.7 1602.15   127.8 1601.58     1311600.858
   135.3 1598.71   139.1 1597.63   150.3 1597.44   161.6 1597.86   165.3 1599.18
   170.21602.123   172.8    1603   180.3 1603.64   206.6 1604.71   217.8 1607.55
   292.5 1615.43   326.6 1620.33   364.1 1624.84   384.2 1627.99   399.4 1629.63
#Mann= 5 ,-1 , 0
       0     .04       0     131    .045       0   170.2     .04       0
     220     .06       0     340      .1       0
#XS Ineff= 2 , 0
          128.34 1603.92  172.09         1603.85
Permanent Ineff=
       F       F
Bank Sta=131,170.2
XS Rating Curve= 0 ,0
Exp/Cntr=0.5,0.3

Type RM Length L Ch R = 1 ,38815   ,101.1,98,94.8
XS GIS Cut Line= 2
     2077200.869      237460.297     2077550.254      237266.764
#Sta/Elev= 30
       0 1649.77    19.5 1636.43    22.1 1634.12    26.9 1628.83    30.7 1623.63
    33.6 1620.75      39 1616.31    46.2 1608.39    49.5 1606.92    64.5 1605.81
    68.2 1604.81    75.7 1601.75    79.5 1601.24    94.91601.141     102 1597.82
   118.6 1597.62   124.5 1597.98   134.2 1600.83   140.4 1601.54     162 1602.07
     170 1603.46   183.8 1604.21     192 1605.28   199.5 1607.17   212.1 1607.52
   248.2 1612.04   265.9 1612.85     312 1620.32   375.8 1626.91   399.4 1629.82
#Mann= 6 ,-1 , 0
       0     .04       0      60      .1       0    94.9    .045       0
   134.2     .04       0     170     .06       0     280      .1       0
#XS Ineff= 2 , 0
           85.25 1603.27  144.65         1603.14
Permanent Ineff=
       F       F
Bank Sta=94.9,134.2
XS Rating Curve= 0 ,0
Exp/Cntr=0.5,0.3

Type RM Length L Ch R = 1 ,38717   ,216.2,224.3,227
XS GIS Cut Line= 4
     2077237.978       237531.26     2077292.231      237517.154
     2077425.695      237402.137     2077569.785      237273.274
#Sta/Elev= 30
       0 1645.58    13.1 1634.55    30.1 1623.42    33.4 1619.58    36.9 1614.24
    38.9 1612.03    41.6 1609.66    44.3 1608.08      47 1607.27    57.5 1607.06
    61.9 1605.47    65.81602.957    73.8 1598.67    76.2 1597.81    79.2 1597.32
    83.5 1597.42    92.2 1600.24    95.21600.355   109.5 1600.02   122.5 1600.84
   163.1 1601.26   209.1 1603.88   233.4 1606.84     244 1608.79     263 1610.32
   270.4  1611.4   278.5 1611.82   322.6 1619.09   371.6 1624.35   425.5  1630.8
#Mann= 5 ,-1 , 0
       0     .04       0    65.8    .045       0    95.2      .1       0
  136.06     .06       0  262.24      .1       0
Bank Sta=65.8,95.2
XS Rating Curve= 0 ,0
Exp/Cntr=0.3,0.1

Type RM Length L Ch R = 1 ,38493   ,220.1,220.6,219.3
XS GIS Cut Line= 3
     2077307.422      237737.423     2077520.096      237616.981
     2077816.278      237554.949
#Sta/Elev= 30
       0 1657.58    25.3 1643.52    34.1 1637.73    38.9 1632.23    43.7 1624.07
    46.1    1621    48.5 1618.68    56.2 1613.59      63 1606.12    66.8 1603.41
    70.6 1602.68    81.9 1602.42    93.2 1600.03   146.61599.615   153.5    1599
   162.7 1596.68   171.3 1597.39   179.21601.005     260 1607.45   277.6 1609.85
   327.8 1619.03   384.7 1625.41   408.3  1627.1   441.8 1635.41   458.6 1638.15
   478.7 1643.12   488.7  1644.7   498.3 1647.59     529 1652.33     547 1658.81
#Mann= 6 ,-1 , 0
       0      .1       0      50     .04       0   146.6    .045       0
   179.2      .1       0  374.41     .06       0  474.41    .035       0
Bank Sta=146.6,179.2
XS Rating Curve= 0 ,0
Exp/Cntr=0.3,0.1

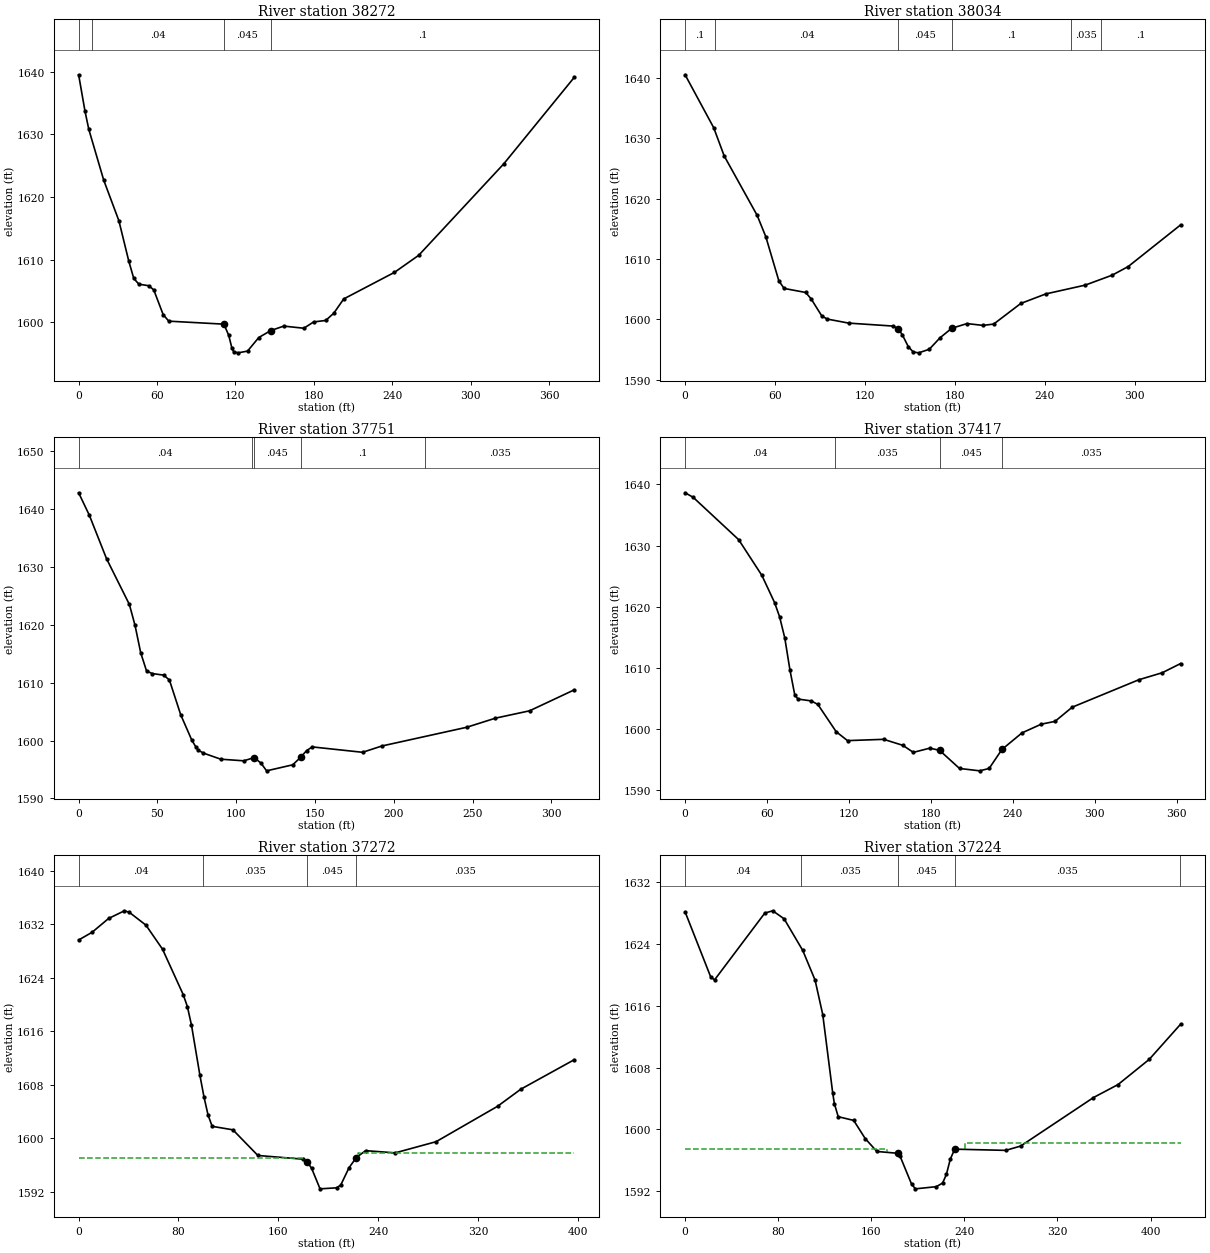
Type RM Length L Ch R = 1 ,38272   ,234.6,238.3,239.8
XS GIS Cut Line= 2
     2077444.141      237913.205     2077769.438      237718.152
#Sta/Elev= 30
       0 1639.52     4.9 1633.67     7.8 1630.79    19.2 1622.69    30.8 1616.21
    38.4 1609.74    42.2 1606.99    46.1 1606.07    53.7 1605.82    57.5 1605.16
    64.7 1601.21      69 1600.16   111.21599.683   114.9 1597.89   117.3 1595.87
   118.7 1595.26   122.1  1595.1   129.3 1595.38   137.9 1597.55   147.11598.661
     157 1599.37   172.4 1599.03   179.9 1600.04   189.1 1600.27   195.3 1601.43
   202.9 1603.71   241.7 1607.95   260.3 1610.68   325.4 1625.29   379.3 1639.09
#Mann= 4 ,-1 , 0
       0      .1       0      10     .04       0   111.2    .045       0
   147.1      .1       0
Bank Sta=111.2,147.1
XS Rating Curve= 0 ,0
Exp/Cntr=0.3,0.1

Type RM Length L Ch R = 1 ,38034   ,282.4,282.6,280.7
XS GIS Cut Line= 3
     2077532.032      238132.389     2077564.584      238084.645
      2077814.15      237973.968
#Sta/Elev= 30
       0 1640.54    19.1 1631.76    26.1 1627.08    48.1 1617.23    53.9 1613.67
    62.6 1606.36    66.1 1605.11    80.5 1604.44    84.1 1603.39    91.3 1600.53
    94.9 1600.03   109.2 1599.36   138.8 1598.87   142.31598.422   145.1 1597.38
     149 1595.45   152.3 1594.57   155.9 1594.43     163 1595.02   170.2 1596.93
     1781598.505   188.2 1599.28   198.9 1598.98     206  1599.2   224.1 1602.62
   240.8  1604.2   267.1 1605.66   285.1 1607.31   295.8 1608.74   330.8 1615.65
#Mann= 6 ,-1 , 0
       0      .1       0      20     .04       0   142.3    .045       0
     178      .1       0  257.79    .035       0  277.79      .1       0
Bank Sta=142.3,178
XS Rating Curve= 0 ,0
Exp/Cntr=0.3,0.1

Type RM Length L Ch R = 1 ,37751   ,328.4,334.4,327.5
XS GIS Cut Line= 2
     2077648.134      238353.743     2077932.422      238219.194
#Sta/Elev= 30
       0 1642.76     6.8 1638.88    17.7 1631.39    32.2 1623.49    35.8 1619.87
    39.4 1615.14    43.1 1612.01    46.7 1611.56    53.9 1611.29    57.6 1610.46
    64.8 1604.44    71.8 1600.08    74.3 1598.94    75.7 1598.38    79.2 1597.83
    90.2 1596.78   104.8  1596.5   111.41597.057   115.7 1596.11   119.3 1594.77
   135.9 1595.81   140.91597.109   144.7 1598.27   148.3  1598.9   180.2 1597.97
   192.5 1599.06   246.3 1602.29   264.5 1603.86   286.2 1605.13   314.5 1608.74
#Mann= 5 ,-1 , 0
       0     .04       0     110      .1       0   111.4    .045       0
   140.9      .1       0     220    .035       0
Bank Sta=111.4,140.9
XS Rating Curve= 0 ,0
Exp/Cntr=0.3,0.1

Type RM Length L Ch R = 1 ,37417   ,130.1,145.1,152.4
XS GIS Cut Line= 2
     2077744.698      238644.368     2078061.546      238467.675
#Sta/Elev= 30
       0 1638.62     5.9 1637.88    39.2 1630.96    56.2 1625.12    65.5 1620.68
    69.2 1618.34      73 1614.87    76.7 1609.73    80.3 1605.57    82.7  1604.9
    92.4  1604.6    97.2 1604.02   110.6 1599.57   118.9 1598.11   145.4 1598.32
   159.4 1597.34   167.1 1596.19   179.2 1596.88   186.31596.521   200.9 1593.56
   215.7 1593.17   222.6 1593.56     2321596.672   246.7 1599.38   260.8  1600.8
   270.8 1601.25   283.4 1603.57   332.2 1608.06   349.4 1609.21   362.8 1610.71
#Mann= 4 ,-1 , 0
       0     .04       0     110    .035       0   186.3    .045       0
     232    .035       0
Bank Sta=186.3,232
XS Rating Curve= 0 ,0
Exp/Cntr=0.5,0.3

Type RM Length L Ch R = 1 ,37272   ,49.9,48,48.2
XS GIS Cut Line= 4
     2077748.604      238705.566     2077987.761      238668.413
     2078020.313      238657.562     2078115.799      238583.777
#Sta/Elev= 30
       0 1629.63    10.8 1630.78      24 1632.84    36.7 1633.99    40.6 1633.76
    53.9 1631.85    67.2 1628.26    83.8 1621.47    87.1  1619.7    90.4 1616.93
    97.1 1609.49   100.4 1606.22   103.7 1603.49     107 1601.81   123.6 1601.29
   143.6 1597.46   179.7 1596.91   183.21596.495   186.7 1595.53   193.4 1592.48
   206.6 1592.63     210 1593.05   216.6 1595.62   222.41597.144   229.9 1598.18
   253.6 1597.85   286.4 1599.52   335.6  1604.8   354.3 1607.36     397 1611.75
#Mann= 4 ,-1 , 0
       0     .04       0     100    .035       0   183.2    .045       0
   222.4    .035       0
#XS Ineff= 2 , 0
          180.84 1597.06  223.63         1597.77
Permanent Ineff=
       F       F
Bank Sta=183.2,222.4
XS Rating Curve= 0 ,0
Exp/Cntr=0.5,0.3

Type RM Length L Ch R = 1 ,37224   ,56.2,55.2,53.2
XS GIS Cut Line= 4
     2077740.792      238755.045     2078008.377      238712.901
     2078040.929       238702.05     2078136.415      238628.265
#Sta/Elev= 30
       0 1628.16      22 1619.74    25.3 1619.35    68.5    1628    75.3  1628.3
    85.1 1627.26   101.1 1623.17   111.7 1619.33   118.3 1614.87   126.9 1604.68
   128.3 1603.33   131.6 1601.64   144.9 1601.16   154.8 1598.81   164.8 1597.14
   182.81596.901   184.7 1596.55   194.7 1592.89     198  1592.3   215.9 1592.58
   221.3 1593.05   224.6 1594.17   227.9 1596.13   231.71597.437   275.6 1597.28
   288.4 1597.84     351 1604.12   372.1  1605.8   398.9 1609.06   425.9 1613.62
#Mann= 5 ,-1 , 0
       0     .04       0     100    .035       0   182.8    .045       0
   231.7    .035       0   425.2     .06       0
#XS Ineff= 2 , 0
          173.74 1597.52  240.91         1598.23
Permanent Ineff=
       F       F
Bank Sta=182.8,231.7
XS Rating Curve= 0 ,0
Exp/Cntr=0.5,0.3

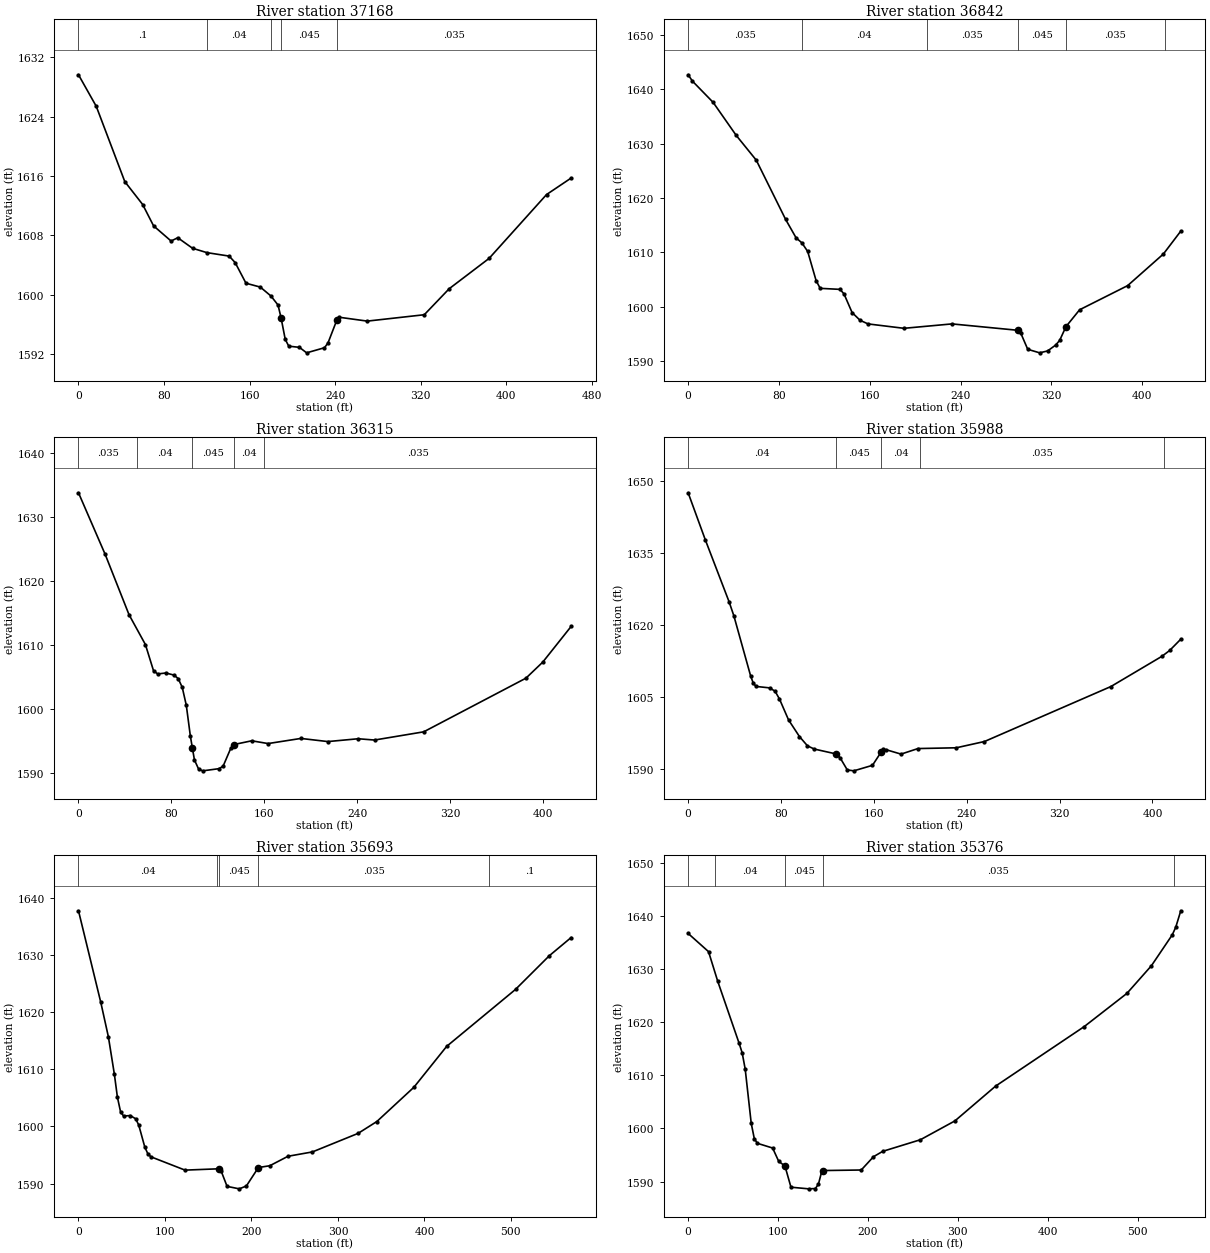
Type RM Length L Ch R = 1 ,37168   ,327.5,326,316.3
XS GIS Cut Line= 2
     2077726.469      238814.941     2078179.818      238733.517
#Sta/Elev= 30
       0 1629.65    16.6  1625.4    43.3 1615.24      60 1612.15    70.2 1609.27
    86.6 1607.22    92.8 1607.67   106.6 1606.25     120 1605.66   140.9 1605.19
   146.5 1604.31   156.6 1601.53     170 1601.01     180  1599.8   186.6 1598.58
   189.51596.789   193.3 1593.96   196.6 1593.04   206.6 1592.88   213.3 1592.14
     230 1592.83   233.3 1593.48   241.71596.618   243.3 1596.95     270 1596.42
   323.3 1597.28   346.6 1600.79   383.9 1604.88   437.6 1613.49   460.6 1615.72
#Mann= 5 ,-1 , 0
       0      .1       0     120     .04       0     180    .035       0
   189.5    .045       0   241.7    .035       0
Bank Sta=189.5,241.7
XS Rating Curve= 0 ,0
Exp/Cntr=0.3,0.1

Type RM Length L Ch R = 1 ,36842   ,521.9,527.1,521.7
XS GIS Cut Line= 2
     2077844.308      239089.029     2078249.263       238933.17
#Sta/Elev= 30
       0 1642.67     3.8  1641.5      22  1637.6    42.4 1631.51      60 1626.97
    85.9 1616.06    95.1 1612.68   100.2 1611.76   105.3 1610.18   112.7 1604.83
   116.3  1603.4   133.8 1603.21   137.3 1602.37   144.4 1598.95   151.4 1597.53
   158.4 1596.86   190.1 1596.05   232.4 1596.86   290.41595.686   293.1  1595.1
   299.1 1592.19   309.6 1591.54   316.6 1591.89   323.7 1592.97   327.2 1593.82
   332.81596.365   344.8 1599.46   387.1  1603.9   418.6 1609.72   433.9 1613.92
#Mann= 6 ,-1 , 0
       0    .035       0     100     .04       0     210    .035       0
   290.4    .045       0   332.8    .035       0     420      .1       0
Bank Sta=290.4,332.8
XS Rating Curve= 0 ,0
Exp/Cntr=0.3,0.1

Type RM Length L Ch R = 1 ,36315   ,336,327.2,316.7
XS GIS Cut Line= 2
     2077991.016      239430.132     2078385.981      239276.052
#Sta/Elev= 30
       0 1633.79      23 1624.16    43.5 1614.75    57.6 1610.09    64.6 1605.99
    68.2  1605.5    75.2 1605.65    82.2 1605.32    85.8 1604.78    89.3 1603.41
    92.8  1600.6    96.3 1595.78      98 1593.96    99.8 1592.07   103.4 1590.64
   106.9 1590.37     121 1590.71   124.5 1591.11     131 1593.86   133.71594.475
   149.1 1595.06   163.2 1594.63   191.4 1595.43   214.6 1594.94   240.7 1595.38
   254.8 1595.18   297.1 1596.46   385.1 1604.84   399.6 1607.35     424 1612.92
#Mann= 5 ,-1 , 0
       0    .035       0      50     .04       0      98    .045       0
   133.7     .04       0     160    .035       0
Bank Sta=98,133.7
XS Rating Curve= 0 ,0
Exp/Cntr=0.3,0.1

Type RM Length L Ch R = 1 ,35988   ,283.7,295.4,303.9
XS GIS Cut Line= 2
     2078184.159      239729.611     2078510.974      239458.821
#Sta/Elev= 30
       0 1647.62    14.8  1637.8    35.3 1624.86    39.4 1621.94    53.9 1609.35
    56.2 1607.84    58.6 1607.21    70.2 1606.91    74.9 1606.21    78.7 1604.58
    86.5 1600.23    95.9 1596.75   102.8 1594.82   108.6 1594.15   127.31593.136
   130.8 1592.37   137.1 1589.79   142.7  1589.6   158.8 1590.75   166.51593.603
   168.1 1594.06   170.4 1594.02   183.4 1593.09     198 1594.25     231 1594.41
   255.3 1595.72   364.2 1607.19   408.1 1613.49   414.8 1614.71   424.4 1617.07
#Mann= 5 ,-1 , 0
       0     .04       0   127.3    .045       0   166.5     .04       0
     200    .035       0     410      .1       0
Bank Sta=127.3,166.5
XS Rating Curve= 0 ,0
Exp/Cntr=0.3,0.1

Type RM Length L Ch R = 1 ,35693   ,312.9,317.1,320.8
XS GIS Cut Line= 3
     2078311.112      239923.838     2078613.846      239805.566
     2078795.445      239641.755
#Sta/Elev= 30
       0  1637.8    25.8 1621.74    34.6 1615.69    41.5 1609.15      45 1605.13
    48.6  1602.6    52.1 1601.83    59.9 1601.91    66.2 1601.34    69.7 1600.23
    76.7 1596.37    80.3 1595.18    83.8 1594.68   123.2 1592.35   162.51592.585
   164.8 1592.25   171.8  1589.5   185.9 1589.07   194.1 1589.57     2081592.801
   221.2 1593.12   242.3 1594.78   270.5 1595.54   323.3 1598.79     345 1600.87
   387.8 1606.87   425.7 1614.04   505.3 1624.02   544.5 1629.94   569.6 1633.11
#Mann= 5 ,-1 , 0
       0     .04       0     160    .035       0   162.5    .045       0
     208    .035       0  475.02      .1       0
Bank Sta=162.5,208
XS Rating Curve= 0 ,0
Exp/Cntr=0.3,0.1

Type RM Length L Ch R = 1 ,35376   ,161.5,169.9,180.9
XS GIS Cut Line= 2
     2078403.343      240202.701     2078932.597      240060.158
#Sta/Elev= 30
       0 1636.74    22.7 1633.31    32.9 1627.74    56.7 1616.05    60.1 1614.26
    63.5 1611.17    70.2 1600.95    73.6 1598.09      77  1597.2      94 1596.31
   100.8 1593.79   107.7 1592.93   114.4 1588.93     134 1588.62   141.6 1588.68
     145 1589.53   148.4 1591.74   150.11592.066   192.6 1592.17   206.2 1594.67
   216.4 1595.68   258.4 1597.87   296.8 1601.42   342.1 1607.98   440.6 1619.18
   488.2 1625.45   515.4 1630.65   538.6 1636.47   542.5 1637.91   548.1 1641.01
#Mann= 5 ,-1 , 0
       0    .035       0      30     .04       0   107.7    .045       0
   150.1    .035       0     540      .1       0
Bank Sta=107.7,150.1
XS Rating Curve= 0 ,0
Exp/Cntr=0.3,0.1

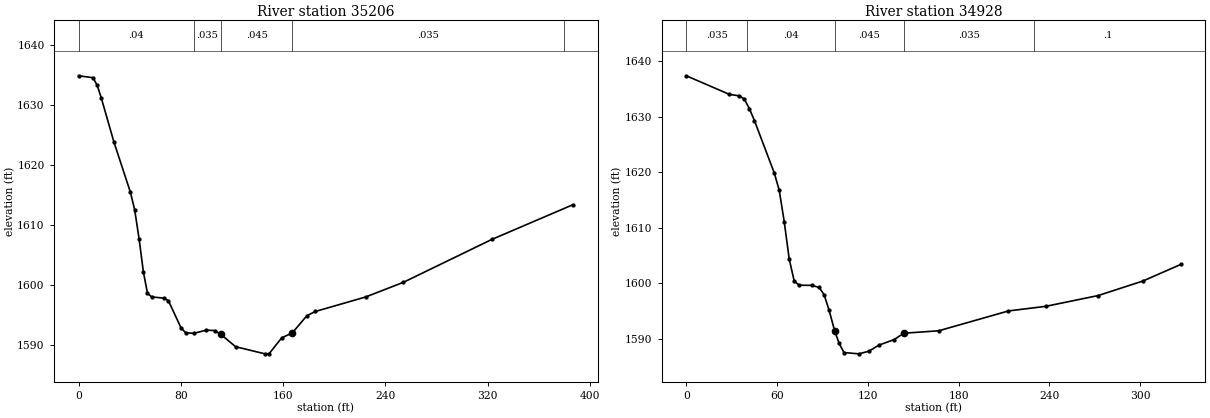
Type RM Length L Ch R = 1 ,35206   ,273.6,277.7,282.8
XS GIS Cut Line= 2
      2078443.49      240328.569     2078830.167      240324.047
#Sta/Elev= 30
       0 1634.92    11.3  1634.6    14.6 1633.32    17.8  1631.2    27.7 1623.85
    40.6 1615.48    43.9 1612.57    47.4 1607.65    50.7 1602.23    53.9 1598.68
    57.2 1598.07      67 1597.87    70.3 1597.43    80.2 1592.89    83.7 1592.12
      90    1592    99.9 1592.54   106.4 1592.47   111.4 1591.82   122.8 1589.78
   145.8 1588.59   149.1 1588.63   158.9 1591.26   167.1 1592.06   178.6 1594.95
   185.2 1595.65   224.5 1598.06   254.1 1600.51   323.2 1607.65   386.7 1613.44
#Mann= 5 ,-1 , 0
       0     .04       0      90    .035       0   111.4    .045       0
   167.1    .035       0     380      .1       0
Bank Sta=111.4,167.1
XS Rating Curve= 0 ,0
Exp/Cntr=0.3,0.1

Type RM Length L Ch R = 1 ,34928   ,261.8,266.3,271
XS GIS Cut Line= 2
     2078396.832      240584.645     2078722.353      240612.857
#Sta/Elev= 30
       0 1637.36    28.5 1634.01    35.1 1633.75    38.4 1633.14    41.7 1631.43
      45 1629.31    58.2 1619.82    61.4 1616.75    64.7 1611.13      68 1604.38
    71.3 1600.42    74.6 1599.68      83 1599.65    87.8 1599.27    91.1 1597.95
    94.4 1595.13      981591.495     101  1589.2   104.2 1587.56   114.1 1587.33
   120.7 1587.81   127.3  1588.9   137.2 1589.88   143.8 1591.04   166.8 1591.48
   212.9 1595.05   237.6 1595.88   272.2 1597.82   301.8 1600.44   326.7 1603.41
#Mann= 5 ,-1 , 0
       0    .035       0      40     .04       0      98    .045       0
   143.8    .035       0     230      .1       0
Bank Sta=98,143.8
XS Rating Curve= 0 ,0
Exp/Cntr=0.3,0.1