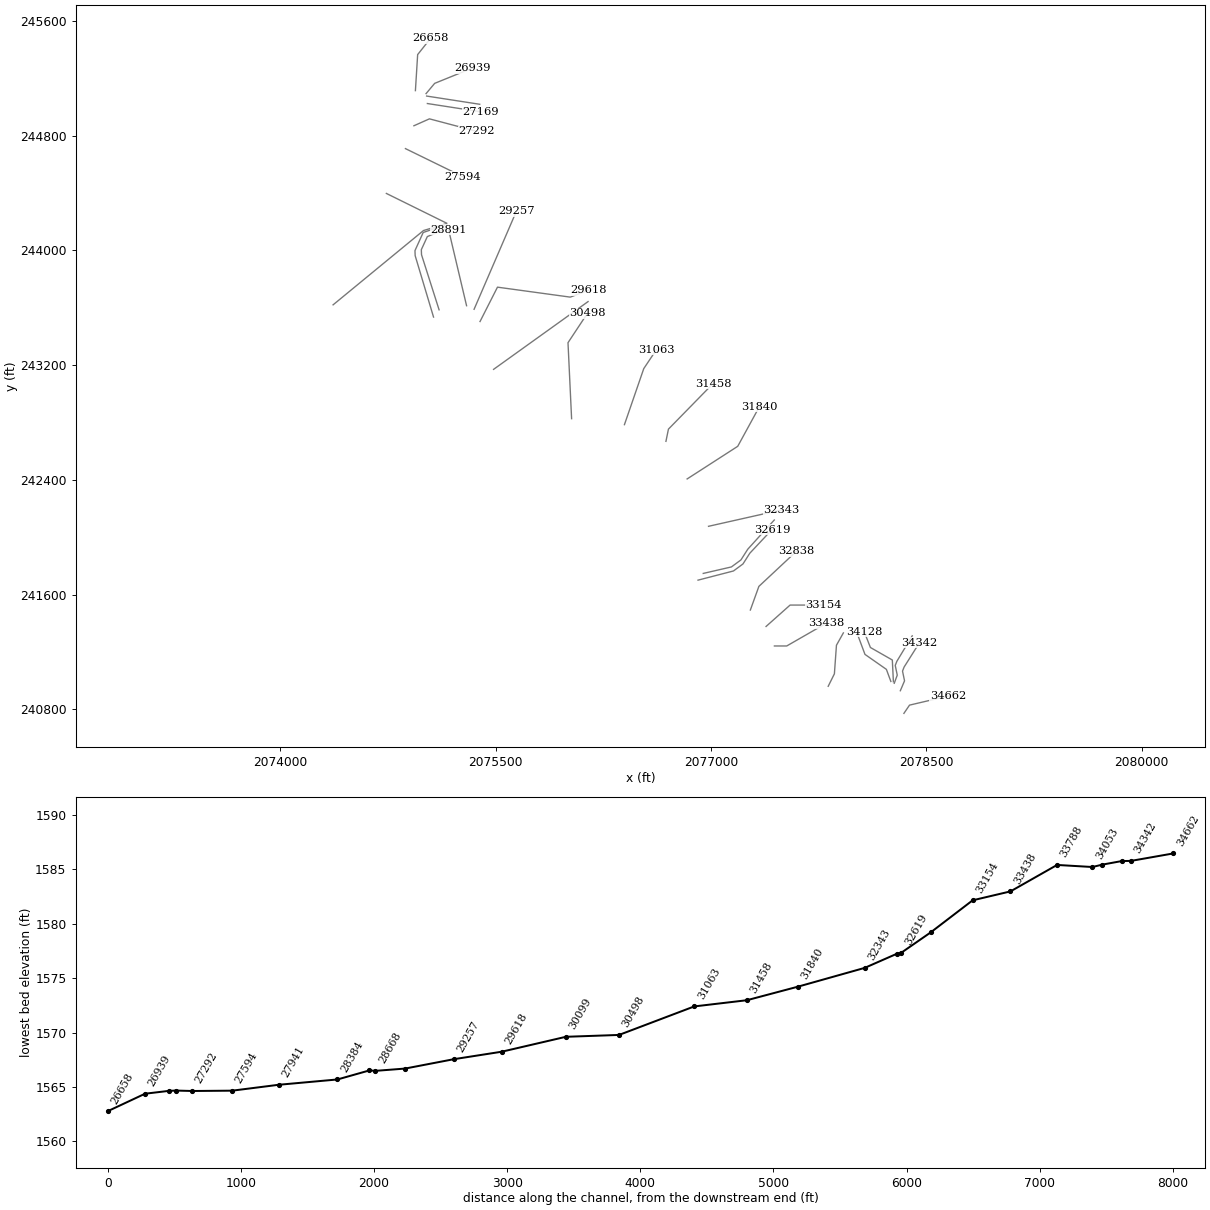
HEC-RAS study WOLFCK.prj: WOLFCK

--- WOLFCK.g01 (geometry) --- (continued)

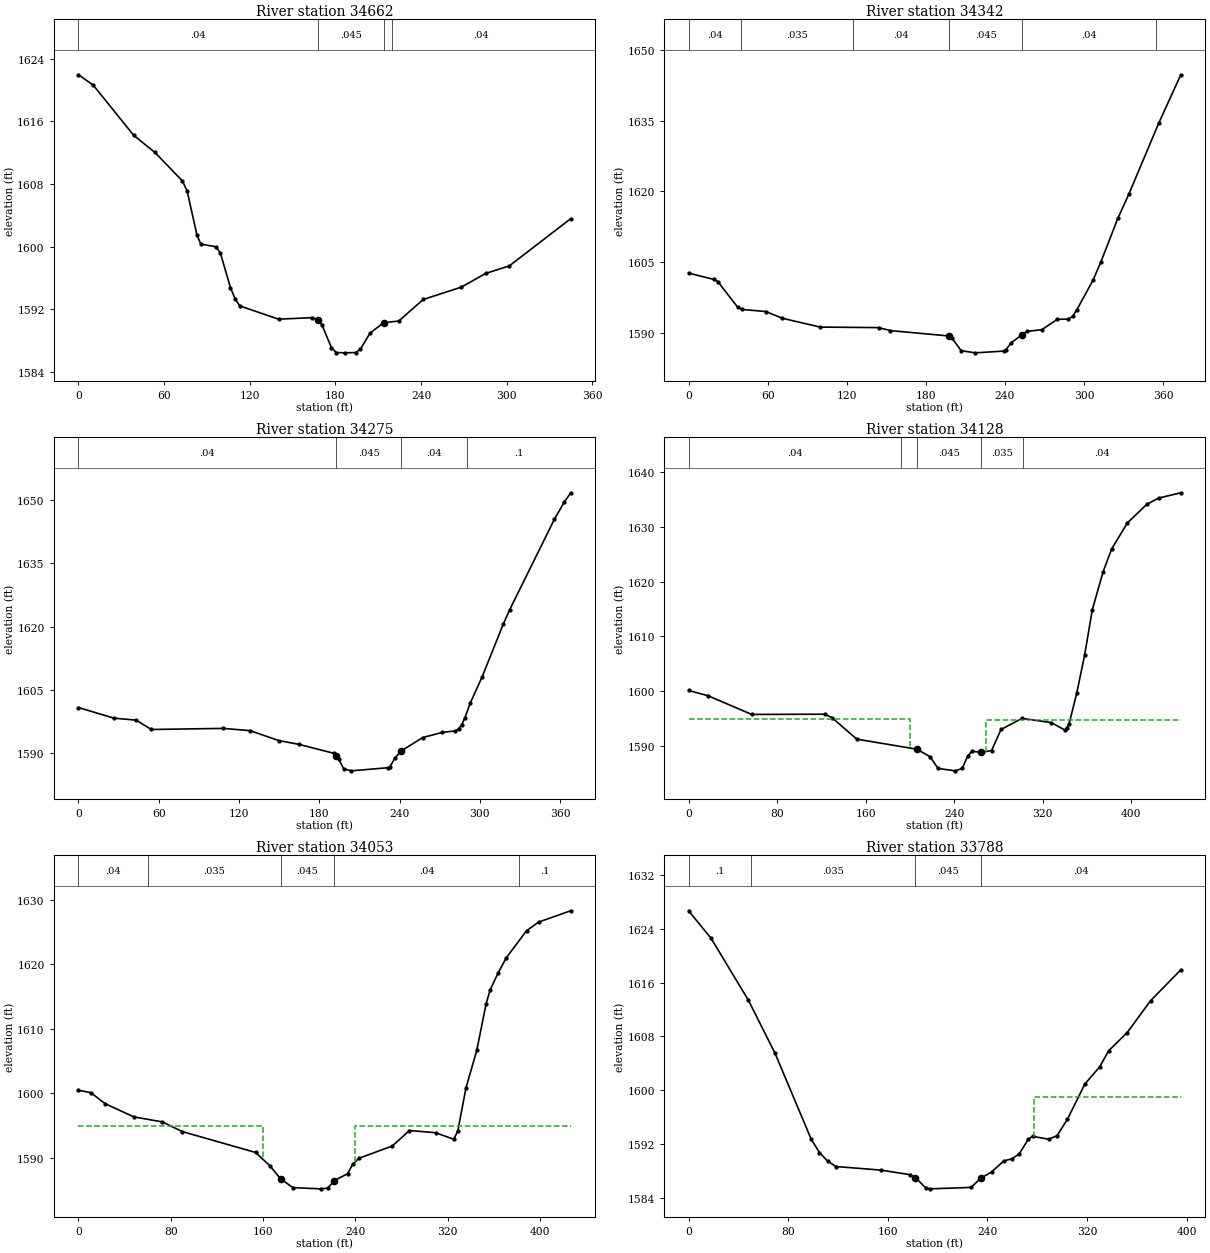
Type RM Length L Ch R = 1 ,34662   ,288,319.8,342.8
XS GIS Cut Line= 3
     2078343.664      240772.363     2078382.726      240829.871
     2078650.738      240892.805
#Sta/Elev= 30
       0 1621.96    10.3 1620.65    38.7 1614.23    53.6 1612.04    72.8 1608.41
    76.1 1607.14      83 1601.51    85.7 1600.35    96.3    1600    99.4 1599.21
   106.5 1594.77   109.8 1593.34     113 1592.45   140.2 1590.76   163.7 1590.95
   167.81590.686   170.5 1590.06   177.2 1587.14   180.6  1586.5   186.7 1586.46
   194.1  1586.5   197.4 1586.89   204.2 1588.96   213.71590.305   224.4 1590.52
   241.5 1593.27   268.2 1594.85   285.2 1596.59   301.9 1597.57   344.8 1603.58
#Mann= 4 ,-1 , 0
       0     .04       0   167.8    .045       0   213.7    .035       0
  219.52     .04       0
Bank Sta=167.8,213.7
XS Rating Curve= 0 ,0
Exp/Cntr=0.3,0.1

Type RM Length L Ch R = 1 ,34342   ,67.6,66.7,66.9
XS GIS Cut Line= 5
     2078318.707      240930.175     2078348.004      240999.142
     2078333.985      241066.981     2078345.096      241095.453
     2078451.078      241263.508
#Sta/Elev= 30
       0 1602.67    19.3 1601.32    22.2 1600.86    37.2 1595.45    40.7 1594.96
    58.5 1594.53    71.1  1593.1    99.7 1591.23   144.2 1591.12   153.1 1590.48
   197.61589.347   199.7 1588.92   206.8 1586.22   217.6 1585.77   238.9 1586.14
   240.8 1586.47   244.8 1587.92   252.9  1589.6   256.7 1590.32     268 1590.68
   279.6 1592.86   288.1 1592.94   291.3  1593.5   294.3 1594.78   306.8 1601.17
   312.7    1605   325.7 1614.33   333.9 1619.36   356.6 1634.43   373.4 1644.72
#Mann= 6 ,-1 , 0
       0     .04       0      40    .035       0  124.93     .04       0
   197.6    .045       0   252.9     .04       0  354.77      .1       0
Bank Sta=197.6,252.9
XS Rating Curve= 0 ,0
Exp/Cntr=0.3,0.1

Type RM Length L Ch R = 1 ,34275   ,85.7,147.5,202.7
XS GIS Cut Line= 5
     2078276.346      240982.258      2078297.31      241038.725
      2078283.29      241106.564     2078294.402      241135.036
     2078401.599      241312.988
#Sta/Elev= 30
       0 1600.78    26.4 1598.27    43.2 1597.78    54.4 1595.57   108.3 1595.83
   128.3 1595.29   149.6 1592.95   164.5 1592.06   190.6 1589.94   192.5 1589.35
   194.4 1588.58   198.2 1586.26   203.8 1585.76   231.4  1586.5   232.7  1586.7
   236.6 1588.83   241.21590.484   257.2 1593.65     272 1594.89   281.6 1595.23
     284 1595.74   286.4 1596.66   288.8 1598.36   292.8 1601.85   301.7 1608.09
   317.5  1620.6   322.2 1623.95   355.7 1645.47   362.9 1649.44   367.8 1651.73
#Mann= 4 ,-1 , 0
       0     .04       0   192.5    .045       0   241.2     .04       0
  290.07      .1       0
Bank Sta=192.5,241.2
XS Rating Curve= 0 ,0
Exp/Cntr=0.5,0.3

Type RM Length L Ch R = 1 ,34128   ,78.4,74.5,73.5
XS GIS Cut Line= 4
2078270.46426878 240992.584790372078262.91653802241144.378042441
 2078110.2846492241231.5962646262078067.51417485241340.619042357
#Sta/Elev= 30
       0 1600.11    17.7 1599.13      57 1595.73   122.9 1595.77   129.4 1595.17
     152 1591.22   206.3 1589.38   218.2 1588.02   225.5 1585.87   240.9 1585.43
   247.3 1585.86   252.1 1588.07     256 1589.01   264.71588.804   273.8 1589.14
   282.4 1592.98   301.3 1595.01   327.8 1594.24   340.2 1592.87   341.8 1593.26
   343.8 1593.91   350.8  1599.6   357.9  1606.5   364.9 1614.84   374.7 1621.82
   382.5 1625.98   396.6 1630.71   414.2 1634.11   424.8 1635.24   444.9 1636.21
#Mann= 5 ,-1 , 0
       0     .04       0  191.98    .035       0   206.3    .045       0
   264.7    .035       0  301.98     .04       0
#XS Ineff= 2 , 0
          200.03 1594.98  268.49         1594.78
Permanent Ineff=
       F       F
Bank Sta=206.3,264.7
XS Rating Curve= 0 ,0
Exp/Cntr(USF)=0,0
Exp/Cntr=0.5,0.3

Type RM Length L Ch R = 1 ,34053   ,301.8,265.4,234.1
XS GIS Cut Line= 4
     2078252.735      240994.7582078221.64035471 241079.11217522
2078072.39944018241183.5257991632078018.49178209241328.209452993
#Sta/Elev= 30
       0 1600.48    10.6 1600.13      23 1598.42      48 1596.36    72.5 1595.59
    89.9 1594.09   153.4 1590.85   165.7 1588.81   175.21586.755   185.8  1585.4
   209.8 1585.21   215.9 1585.31   221.6 1586.49   233.1 1587.55   237.8 1589.07
   242.9 1589.94     272 1591.86   286.7 1594.25   309.4 1593.91   325.2 1592.89
   328.7 1594.23   335.7 1600.84   345.1  1606.7   353.2 1613.92   356.7 1616.06
   363.7 1618.72   370.7 1621.04   388.2 1625.22   398.7 1626.56   426.4 1628.31
#Mann= 5 ,-1 , 0
       0     .04       0      60    .035       0   175.2    .045       0
   221.6     .04       0  382.04      .1       0
#XS Ineff= 2 , 0
          159.96 1594.93   239.6         1594.93
Permanent Ineff=
       F       F
Bank Sta=175.2,221.6
XS Rating Curve= 0 ,0
Exp/Cntr=0.5,0.3

Type RM Length L Ch R = 1 ,33788   ,377.3,349.9,312.2
XS GIS Cut Line= 4
     2077816.278      240961.199     2077859.419      241048.144
     2077873.742      241247.363     2077921.919        241333.3
#Sta/Elev= 30
       0 1626.65    18.1 1622.55    47.9 1613.41    69.4 1605.51    98.5 1592.74
   105.1 1590.78   111.7 1589.51   118.3 1588.71   154.5 1588.18   177.5 1587.51
   182.21587.077   190.7 1585.48   193.9  1585.4   226.8 1585.61   234.61586.971
   243.3  1587.9   253.1 1589.53   259.7 1589.86   265.6  1590.6   272.9 1592.78
   276.2 1593.19   289.3 1592.76   295.9 1593.29   304.2 1595.71   318.3 1600.96
   330.1 1603.49   337.4 1605.89   352.2 1608.57     371 1613.31   395.3 1617.89
#Mann= 4 ,-1 , 0
       0      .1       0      50    .035       0   182.2    .045       0
   234.6     .04       0
#XS Ineff= 2 , 0
                          277.17         1599.03
Permanent Ineff=
       F       F
Bank Sta=182.2,234.6
XS Rating Curve= 0 ,0
Exp/Cntr=0.3,0.1

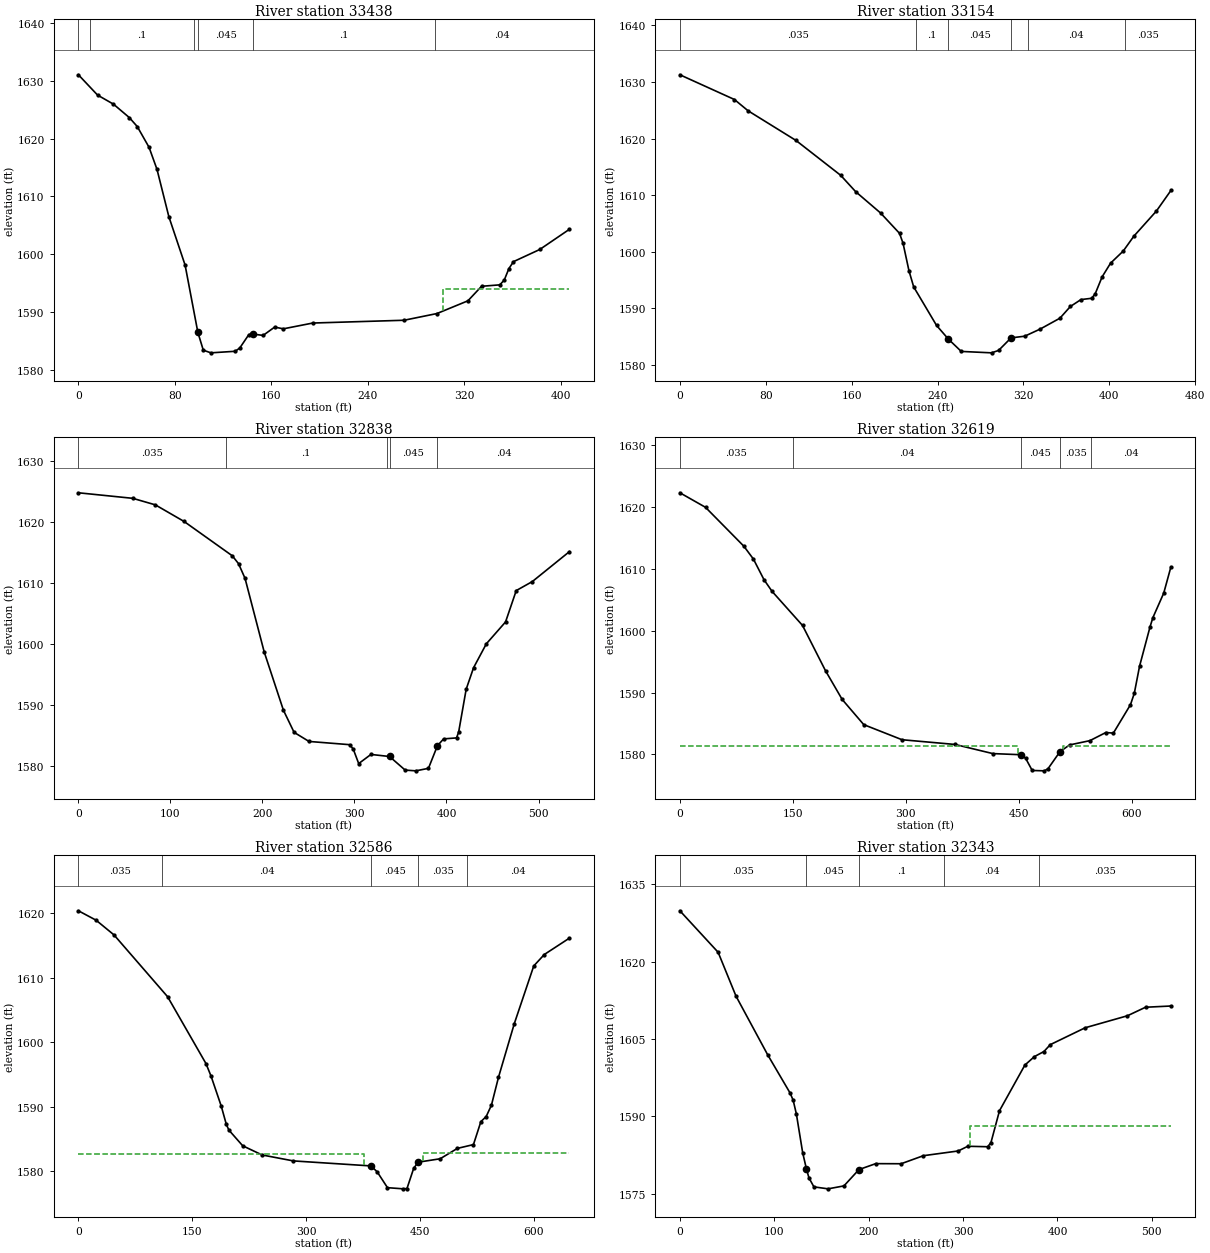
Type RM Length L Ch R = 1 ,33438   ,295.7,284.2,264.7
XS GIS Cut Line= 3
      2077441.45      241242.154     2077527.388      241242.154
     2077806.034       241402.31
#Sta/Elev= 30
       0 1631.02    15.9 1627.51    29.1 1625.94    42.2 1623.63    48.8 1622.08
    58.6 1618.49    65.2 1614.67      75 1606.52    88.5 1598.14    99.11586.499
   103.6 1583.43   109.9 1582.97   130.1 1583.24   133.9 1583.82   141.4 1586.13
     1451586.208   153.2 1585.98   162.8 1587.42     170 1587.12   194.4 1588.12
   270.1  1588.6   297.4 1589.76   323.1 1591.96   334.4 1594.47   349.6 1594.72
   353.3 1595.57   357.1 1597.53   360.9 1598.73   382.7 1600.83   407.3 1604.32
#Mann= 6 ,-1 , 0
       0    .035       0      10      .1       0   95.94    .035       0
    99.1    .045       0     145      .1       0  295.94     .04       0
#XS Ineff= 2 , 0
                          302.02         1593.94
Permanent Ineff=
       F       F
Bank Sta=99.1,145
XS Rating Curve= 0 ,0
Exp/Cntr=0.3,0.1

Type RM Length L Ch R = 1 ,33154   ,286,315.3,341.1
XS GIS Cut Line= 3
      2077383.37      241378.092     2077550.825       241527.31
     2077783.898       241527.31
#Sta/Elev= 30
       0 1631.29    50.8 1626.92    63.5 1624.93   108.1 1619.69   149.8 1613.52
   163.7 1610.64   186.9 1606.87   204.6 1603.27   207.9  1601.5   213.4 1596.65
   217.8  1593.8   239.1 1586.99   250.2 1584.56   262.1  1582.4   290.3 1582.15
   296.9 1582.58   308.51584.795   321.2 1585.09   335.6 1586.35     354 1588.27
   363.8 1590.35   373.6 1591.56   383.5 1591.79   386.8 1592.55   393.3 1595.57
   401.2    1598     413 1600.14   422.9 1602.77   443.9 1607.21   457.4 1610.84
#Mann= 6 ,-1 , 0
       0    .035       0     220      .1       0   250.2    .045       0
   308.5      .1       0  324.29     .04       0  414.29    .035       0
Bank Sta=250.2,308.5
XS Rating Curve= 0 ,0
Exp/Cntr=0.3,0.1

Type RM Length L Ch R = 1 ,32838   ,216,219.7,222
XS GIS Cut Line= 3
     2077273.995      241492.675     2077333.377      241657.519
     2077595.096       241902.31
#Sta/Elev= 30
       0  1624.8    59.1 1623.89    83.6 1622.82   114.9 1620.09   167.2 1614.47
     174 1613.18   181.1 1610.76   201.9  1598.7   222.8 1589.14   234.4 1585.51
   250.6 1584.02   294.8 1583.49   298.7 1582.76   304.6 1580.39   317.9 1581.89
   338.11581.552   355.1 1579.32   366.7  1579.2   380.4 1579.61   390.2 1583.33
   396.9 1584.44   410.9  1584.6   413.2 1585.54   421.4 1592.58   429.4  1596.1
   443.3 1600.03   464.2 1603.62   475.8 1608.76   493.3 1610.24   533.6 1615.15
#Mann= 5 ,-1 , 0
       0    .035       0     160      .1       0  335.21     .04       0
   338.1    .045       0   390.2     .04       0
Bank Sta=338.1,390.2
XS Rating Curve= 0 ,0
Exp/Cntr=0.5,0.3

Type RM Length L Ch R = 1 ,32619   ,29.8,32.2,31.8
XS GIS Cut Line= 5
     2076909.412      241701.008     2077156.294      241764.941
     2077222.483      241813.769     2077270.226      241888.639
     2077424.523      242053.352
#Sta/Elev= 30
       0 1622.31      34 1619.96    84.9 1613.67    97.6 1611.59   111.7 1608.24
   122.4 1606.36   162.8 1600.85   193.3 1593.53   215.4 1588.89   244.1 1584.81
   294.9 1582.37   365.1 1581.61   415.4 1580.13   452.21579.948   458.8  1579.4
   467.7  1577.4   483.9 1577.34   488.7 1577.69   504.61580.448   517.3 1581.53
   544.2 1582.22   565.5 1583.54   575.4 1583.44   598.1 1588.03   603.2 1589.87
   610.2 1594.27   624.1 1600.63   627.9 1602.12   642.3 1606.09   651.8 1610.32
#Mann= 5 ,-1 , 0
       0    .035       0     150     .04       0   452.2    .045       0
   504.6    .035       0  546.07     .04       0
#XS Ineff= 2 , 0
          448.28 1581.28  507.94         1581.29
Permanent Ineff=
       F       F
Bank Sta=452.2,504.6
XS Rating Curve= 0 ,0
Exp/Cntr=0.5,0.3

Type RM Length L Ch R = 1 ,32586   ,257.2,243.8,209.4
XS GIS Cut Line= 5
      2076945.87      241747.883     2077142.188      241793.152
     2077208.377      241841.981      2077256.12       241916.85
     2077440.662      242120.279
#Sta/Elev= 30
       0 1620.36    23.3  1618.9      47 1616.61   117.6 1607.03   168.1 1596.68
   174.8 1594.74   188.3 1590.07     195 1587.23   198.4 1586.35   216.6 1583.92
   242.2  1582.5   283.3 1581.58   385.61580.803   393.8 1579.89   407.4 1577.43
   428.3 1577.25   433.1  1577.3   441.9 1580.42   447.7 1581.38   476.8 1581.91
   499.5 1583.52   520.7 1584.11   530.5 1587.67   537.5 1588.46   544.4 1590.22
   553.7 1594.54   574.6 1602.88   600.2 1611.81   614.1 1613.58   647.2 1616.12
#Mann= 5 ,-1 , 0
       0    .035       0     110     .04       0   385.6    .045       0
   447.7    .035       0  512.52     .04       0
#XS Ineff= 2 , 0
          376.16 1582.61  453.94         1582.88
Permanent Ineff=
       F       F
Bank Sta=385.6,447.7
XS Rating Curve= 0 ,0
Exp/Cntr=0.5,0.3

Type RM Length L Ch R = 1 ,32343   ,485.6,502.7,503.2
XS GIS Cut Line= 2
     2076982.683      242076.356     2077490.141      242190.592
#Sta/Elev= 30
       0  1629.9    40.5 1621.85    59.5 1613.32    93.1 1601.92   116.7 1594.55
     120 1593.14   123.4 1590.48   130.1 1582.94   134.11579.765   136.8 1578.04
     142 1576.32     157 1575.94   173.8 1576.51   189.71579.677   207.5 1580.83
   234.4 1580.81   257.9 1582.37   294.9 1583.29     305  1584.2     326 1584.11
   329.5 1584.88   338.6  1591.1   365.5 1599.96   375.6  1601.6   385.7 1602.59
   392.4 1603.92   429.4  1607.2   474.2 1609.53   493.3 1611.18   520.2 1611.42
#Mann= 5 ,-1 , 0
       0    .035       0   134.1    .045       0   189.7      .1       0
     280     .04       0     380    .035       0
#XS Ineff= 2 , 0
                          307.88         1588.19
Permanent Ineff=
       F       F
Bank Sta=134.1,189.7
XS Rating Curve= 0 ,0
Exp/Cntr=0.3,0.1

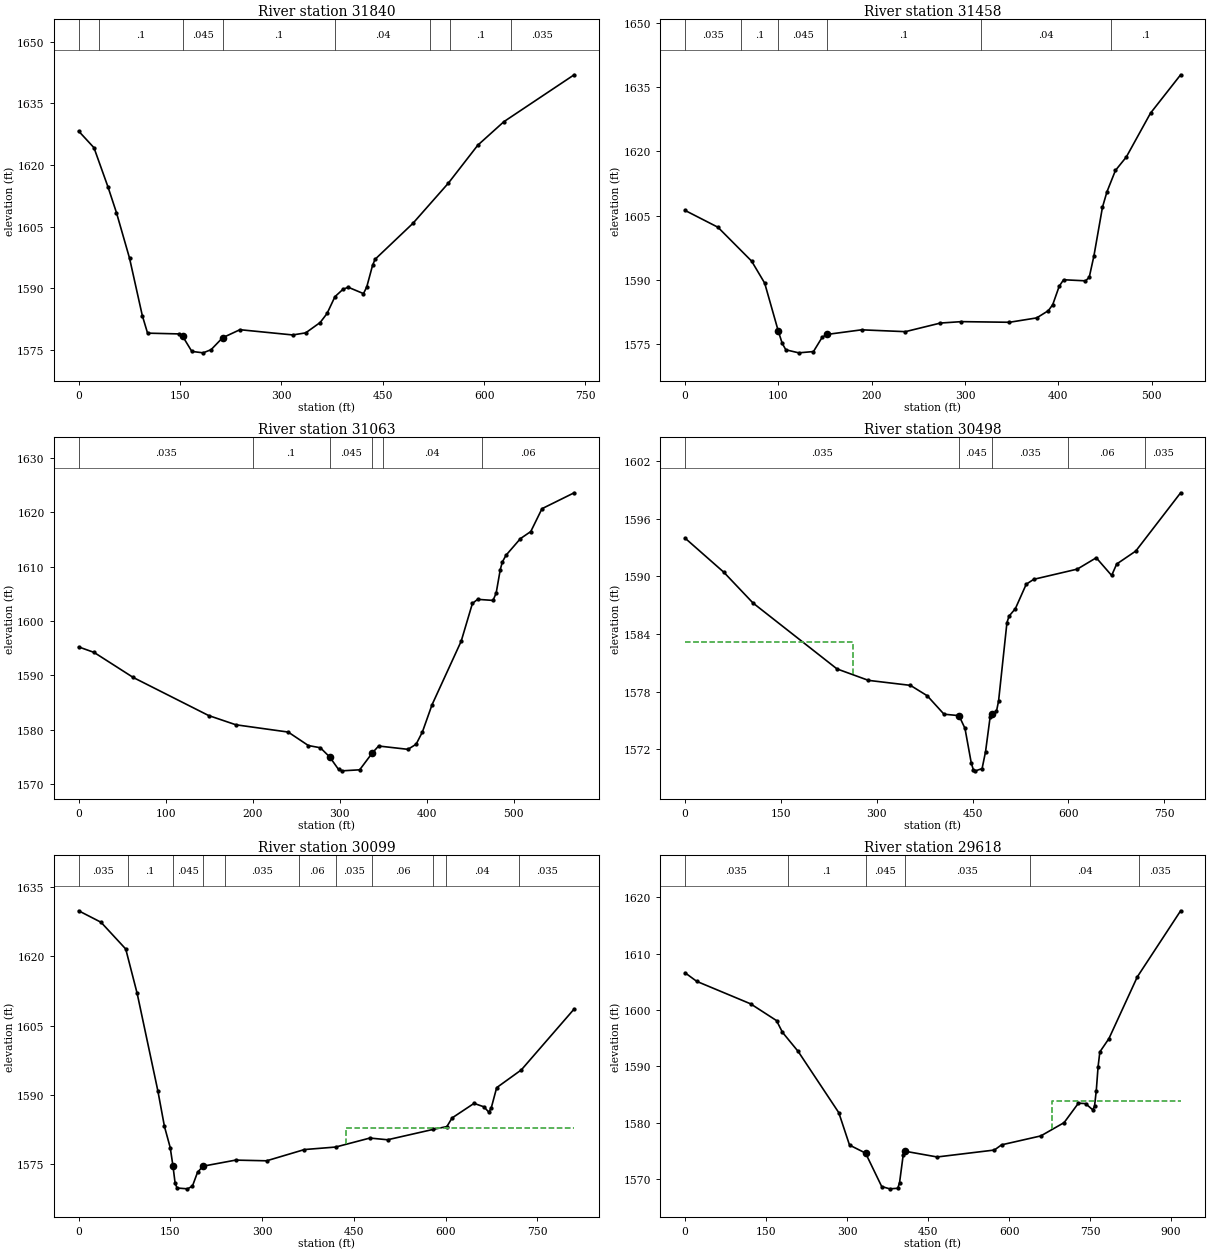
Type RM Length L Ch R = 1 ,31840   ,373.3,381.6,390.6
XS GIS Cut Line= 3
     2076833.594      242406.434     2077186.025      242633.864
     2077336.495      242909.342
#Sta/Elev= 30
       0 1628.26    22.7 1624.21    43.5 1614.62      56 1608.37    75.3  1597.3
    94.2 1583.31     102 1579.01   148.9 1578.82     154 1578.22   167.5 1574.56
   184.2 1574.21     196 1574.98     2131577.885   238.7 1579.85   316.8 1578.57
     336 1579.08   357.4  1581.6   367.6  1583.8   379.3  1587.9     391 1589.67
   398.8 1590.21   421.5 1588.65   426.3 1590.24   434.9  1595.5   438.6    1597
   494.7 1605.78     547 1615.55   590.7 1624.83   629.4 1630.57   733.3 1641.99
#Mann= 8 ,-1 , 0
       0    .035       0      30      .1       0     154    .045       0
     213      .1       0     380     .04       0  519.44    .035       0
  549.44      .1       0  639.44    .035       0
Bank Sta=154,213
XS Rating Curve= 0 ,0
Exp/Cntr=0.3,0.1

Type RM Length L Ch R = 1 ,31458   ,378.7,395.5,408.6
XS GIS Cut Line= 3
     2076686.025      242668.586     2076703.386      242753.656
      2077014.15      243071.364
#Sta/Elev= 30
       0 1606.19    35.2 1602.27    71.3 1594.37    85.3 1589.24    99.9 1578.04
   104.1 1575.18     108 1573.68   121.8 1572.97   137.6 1573.27     147 1576.62
   152.21577.267   189.2 1578.34   236.1 1577.91   273.7 1579.92   296.2 1580.25
   347.7  1580.1   376.9 1581.12   389.4 1582.81   394.1 1584.22     401 1588.49
   405.7 1590.02   429.2 1589.77   433.2 1590.58   438.2 1595.54   447.4 1606.94
   452.2 1610.53   461.3 1615.52     473 1618.67   498.9 1628.89   531.2 1637.84
#Mann= 6 ,-1 , 0
       0    .035       0      60      .1       0    99.9    .045       0
   152.2      .1       0  316.82     .04       0  456.82      .1       0
Bank Sta=99.9,152.2
XS Rating Curve= 0 ,0
Exp/Cntr=0.3,0.1

Type RM Length L Ch R = 1 ,31063   ,548.2,564.9,574.1
XS GIS Cut Line= 3
     2076396.847      242784.884     2076531.511      243175.531
     2076618.317      243305.739
#Sta/Elev= 30
       0 1595.22    17.7 1594.21    62.8 1589.59   149.5 1582.58   180.8 1580.88
   240.9 1579.54   264.1 1577.06   277.9 1576.65   288.61574.961   298.8 1572.66
   302.8  1572.4   323.1 1572.59   337.81575.735   344.9 1576.97   378.6 1576.36
     388  1577.3   395.2 1579.55   406.3 1584.57   439.8 1596.27   452.7 1603.22
   458.7 1603.98   476.4 1603.78     480 1605.12   484.7 1609.42   487.1 1610.85
   491.3 1612.09   507.9 1615.16   519.8 1616.46   532.7 1620.67   569.7  1623.6
#Mann= 6 ,-1 , 0
       0    .035       0     200      .1       0   288.6    .045       0
   337.8      .1       0     350     .04       0  463.21     .06       0
Bank Sta=288.6,337.8
XS Rating Curve= 0 ,0
Exp/Cntr=0.3,0.1

Type RM Length L Ch R = 1 ,30498   ,420.6,398.8,354.5
XS GIS Cut Line= 3
     2076028.791      242826.551     2076003.733      243356.086
      2076139.15      243560.948
#Sta/Elev= 30
       0 1593.98    60.4 1590.45   106.4 1587.23   237.8 1580.38     287 1579.19
   352.7 1578.67     379 1577.59   405.3 1575.67   428.71575.523   438.1  1574.2
     448 1570.58   451.3 1569.88   454.5 1569.78   464.9 1570.01   470.3 1571.77
   477.5 1575.39     4811575.658   487.4 1575.97   490.7 1577.04   503.8 1585.19
   507.1 1585.87     517 1586.65     534 1589.19   545.8  1589.7   613.9 1590.76
   643.6 1591.94   667.7  1590.1   675.6 1591.29   705.5 1592.64   775.7  1598.7
#Mann= 5 ,-1 , 0
       0    .035       0   428.7    .045       0     481    .035       0
  600.13     .06       0  720.13    .035       0
#XS Ineff= 2 , 0
          263.43  1583.2
Permanent Ineff=
       F       F
Bank Sta=428.7,481
XS Rating Curve= 0 ,0
Exp/Cntr=0.3,0.1

Type RM Length L Ch R = 1 ,30099   ,501.1,481.5,448.7
XS GIS Cut Line= 2
     2075485.388      243170.301     2076143.535      243642.623
#Sta/Elev= 30
       0  1629.9    36.6 1627.41      77 1621.61    95.7 1611.97   129.5 1590.87
   140.3 1583.13   149.7 1578.57   154.21574.583   157.8 1570.77     161 1569.79
   177.9 1569.61     186 1570.19   194.4  1573.2   203.31574.521   256.7 1575.84
   307.3 1575.69   369.2 1578.13   420.1 1578.67   476.1 1580.62   505.1 1580.25
     580 1582.51     602 1583.11   610.5 1584.98   646.4 1588.14   662.6 1587.39
   670.6 1586.23   674.7 1587.23   683.4 1591.55   723.7  1595.4   810.1 1608.61
#Mann= 11 ,-1 , 0
       0    .035       0      80      .1       0   154.2    .045       0
   203.3      .1       0     240    .035       0     360     .06       0
     420    .035       0     480     .06       0     580    .035       0
     600     .04       0     720    .035       0
#XS Ineff= 2 , 0
                             437         1582.88
Permanent Ineff=
       F       F
Bank Sta=154.2,203.3
XS Rating Curve= 0 ,0
Exp/Cntr=0.3,0.1

Type RM Length L Ch R = 1 ,29618   ,297.9,361.1,406.5
XS GIS Cut Line= 4
     2075390.886      243503.656     2075512.414      243743.239
     2076019.358      243673.795      2076147.83      243722.406
#Sta/Elev= 30
       0  1606.6    21.7 1605.08   121.4 1601.09   169.3 1598.12   180.3 1596.04
   209.4 1592.64   284.6 1581.77   304.5 1576.01   334.21574.583   364.1 1568.65
   378.9 1568.24   393.9 1568.34   397.2 1569.36   403.9 1574.25   406.41574.935
   466.8  1573.9   572.7 1575.13     586 1576.05   658.8 1577.64   701.9    1580
   728.4 1583.45   741.6 1583.38   754.9 1582.27   758.2 1582.89   761.5  1585.7
   764.8 1589.92   768.1 1592.56   784.9 1594.92   837.5 1605.89   917.7 1617.62
#Mann= 6 ,-1 , 0
       0    .035       0     190      .1       0   334.2    .045       0
   406.4    .035       0  638.64     .04       0  840.32    .035       0
#XS Ineff= 2 , 0
                           679.8         1583.89
Permanent Ineff=
       F       F
Bank Sta=334.2,406.4
XS Rating Curve= 0 ,0
Exp/Cntr=0.3,0.1

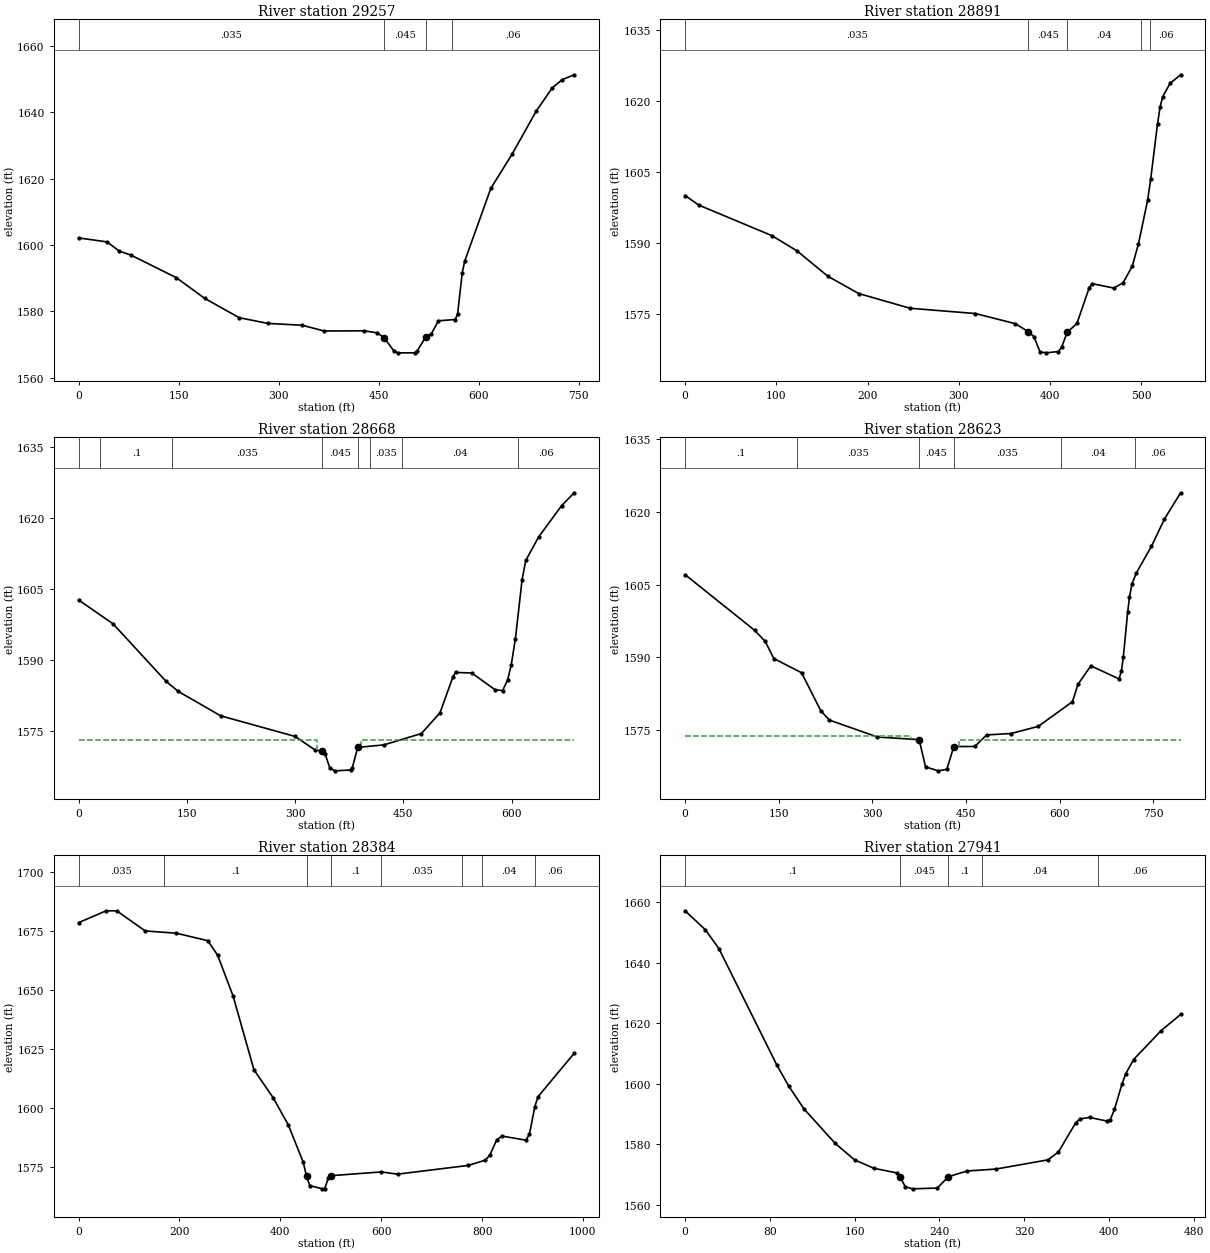
Type RM Length L Ch R = 1 ,29257   ,344.8,365.5,392.5
XS GIS Cut Line= 2
     2075349.516      243589.029     2075643.787      244271.321
#Sta/Elev= 30
       0 1602.15    42.8 1600.94    60.7  1598.2    78.6 1596.96   146.5 1590.17
   189.3 1583.91   240.8 1578.13   283.3 1576.42   335.4 1575.85     368 1574.13
   428.1 1574.18     448 1573.55   458.31572.009     473 1568.04   478.7 1567.55
   503.8 1567.56   507.3    1568   520.51572.388   528.8 1573.26   539.5  1577.2
   564.5 1577.58   568.1 1579.11   575.2 1591.66   578.8 1595.13   618.1  1617.1
   650.2 1627.45     686 1640.29   710.1 1647.31   725.1  1649.8     743 1651.26
#Mann= 4 ,-1 , 0
       0    .035       0   458.3    .045       0   520.5    .035       0
     560     .06       0
Bank Sta=458.3,520.5
XS Rating Curve= 0 ,0
Exp/Cntr=0.3,0.1

Type RM Length L Ch R = 1 ,28891   ,219.7,222.7,224.8
XS GIS Cut Line= 2
     2075297.136      243613.899     2075172.136      244142.545
#Sta/Elev= 30
       0 1599.97    14.9 1597.95    95.3 1591.47   122.7 1588.25   156.5 1582.89
   190.2 1579.24   246.6 1576.12   318.3    1575   362.1 1572.85   376.31571.156
   382.3 1570.14   389.1 1566.89   395.8 1566.69   409.3 1566.97   412.7 1567.87
   418.91571.048   429.5  1572.9     443 1580.46   446.4 1581.32     470 1580.39
   480.1  1581.5   490.2 1585.03     497 1589.77   507.1 1599.05   510.4 1603.48
   517.9 1615.17   520.6 1618.59   523.4 1620.81   531.6 1623.69   543.2 1625.51
#Mann= 5 ,-1 , 0
       0    .035       0   376.3    .045       0   418.9     .04       0
     500    .035       0     510     .06       0
Bank Sta=376.3,418.9
XS Rating Curve= 0 ,0
Exp/Cntr=0.5,0.3

Type RM Length L Ch R = 1 ,28668   ,45.6,45,44.9
XS GIS Cut Line= 5
      2075105.73      243585.253     2074983.334      243969.368
     2074982.032      244004.524     2075023.698       244095.67
     2075160.417      244152.961
#Sta/Elev= 30
       0 1602.61    47.9 1597.54     121 1585.43   138.2 1583.27   196.8 1578.12
   300.1 1573.75   327.3 1570.93   337.6  1570.6   341.4 1570.14   348.2 1567.06
   355.2 1566.48   376.9 1566.66   379.3 1567.12   386.81571.434     423 1571.97
   475.1 1574.37   500.9 1578.77   518.9 1586.41   522.5 1587.29   544.9 1587.17
   576.9 1583.65   587.6 1583.44   594.6 1585.72   599.6 1588.89   605.4 1594.46
   614.6 1606.89   619.7 1610.97   637.4 1615.91   669.4 1622.56   686.8 1625.28
#Mann= 8 ,-1 , 0
       0    .035       0      30      .1       0     130    .035       0
   337.6    .045       0   386.8      .1       0  403.14    .035       0
  448.32     .04       0  608.54     .06       0
#XS Ineff= 2 , 0
          331.01 1572.93  391.44          1573.1
Permanent Ineff=
       F       F
Bank Sta=337.6,386.8
XS Rating Curve= 0 ,0
Exp/Cntr=0.5,0.3

Type RM Length L Ch R = 1 ,28623   ,279,239.8,195.8
XS GIS Cut Line= 5
     2075066.985      243534.884     2074939.063      243962.857
     2074937.761      243998.014     2074995.053      244124.316
     2075159.115      244180.305
#Sta/Elev= 30
       0 1607.04   111.3 1595.55   128.4 1593.24   142.1 1589.71   186.6 1586.78
   217.4 1578.92   231.1    1577   308.2 1573.51     375 1572.96   385.2 1567.34
   405.7 1566.52   419.4 1566.83   430.41571.541     464 1571.55   483.1 1573.94
   522.3 1574.23   565.9 1575.71   620.6  1580.8   629.4 1584.38   650.1 1588.21
   695.2  1585.5     699 1587.12   702.1 1590.05     709 1599.24   711.9 1602.36
     716 1605.14   722.9 1607.39   747.2 1612.91     768 1618.53   793.9 1623.95
#Mann= 6 ,-1 , 0
       0      .1       0     180    .035       0     375    .045       0
   430.4    .035       0  601.86     .04       0  720.55     .06       0
#XS Ineff= 2 , 0
          362.02 1573.78  438.79         1572.85
Permanent Ineff=
       F       F
Bank Sta=375,430.4
XS Rating Curve= 0 ,0
Exp/Cntr=0.5,0.3

Type RM Length L Ch R = 1 ,28384   ,480.8,442.3,402.1
XS GIS Cut Line= 3
     2074367.333      243619.954     2074997.181      244138.022
      2075157.25      244185.939
#Sta/Elev= 30
       0 1678.43    54.6 1683.45    75.8  1683.4     132 1674.91     194 1673.94
     256 1670.79   275.5  1664.7   306.3 1647.33   347.7 1616.09     386 1604.18
   415.9 1592.69   445.4 1576.96     4521570.929   458.2 1567.07   483.5 1565.69
   487.9 1565.76   495.1  1570.2   501.11571.277     600 1572.85   632.3 1571.91
   772.5  1575.6   806.5 1577.84   815.5 1580.01   828.8 1586.36   839.1 1588.05
     887 1586.29   893.9 1588.82   904.6 1600.54     911 1604.73   982.6  1623.1
#Mann= 8 ,-1 , 0
       0    .035       0     170      .1       0     452    .045       0
   501.1      .1       0     600    .035       0     760      .1       0
     800     .04       0  905.54     .06       0
Bank Sta=452,501.1
XS Rating Curve= 0 ,0
Exp/Cntr=0.3,0.1

Type RM Length L Ch R = 1 ,27941   ,347,347.6,347.6
XS GIS Cut Line= 2
     2074738.542      244396.451     2075157.813       244189.42
#Sta/Elev= 30
       0 1657.19    19.2 1650.88    31.9 1644.68    86.7 1606.06    97.7 1599.23
   112.2 1591.64   141.6 1580.25   159.9 1574.78   178.2 1571.99   200.2 1570.44
   202.71569.281   207.8 1565.87   214.8  1565.2     238 1565.46   248.51569.232
     266  1571.1   293.5 1571.75   342.5  1574.8   352.3 1577.41   368.5 1586.99
   372.2 1588.31   381.7 1588.83   397.8 1587.64   401.3 1588.13   405.1 1591.46
   412.4 1600.01   415.8 1603.28   423.2 1607.97     449 1617.48   467.6 1622.89
#Mann= 5 ,-1 , 0
       0      .1       0   202.7    .045       0   248.5      .1       0
     280     .04       0     390     .06       0
Bank Sta=202.7,248.5
XS Rating Curve= 0 ,0
Exp/Cntr=0.3,0.1

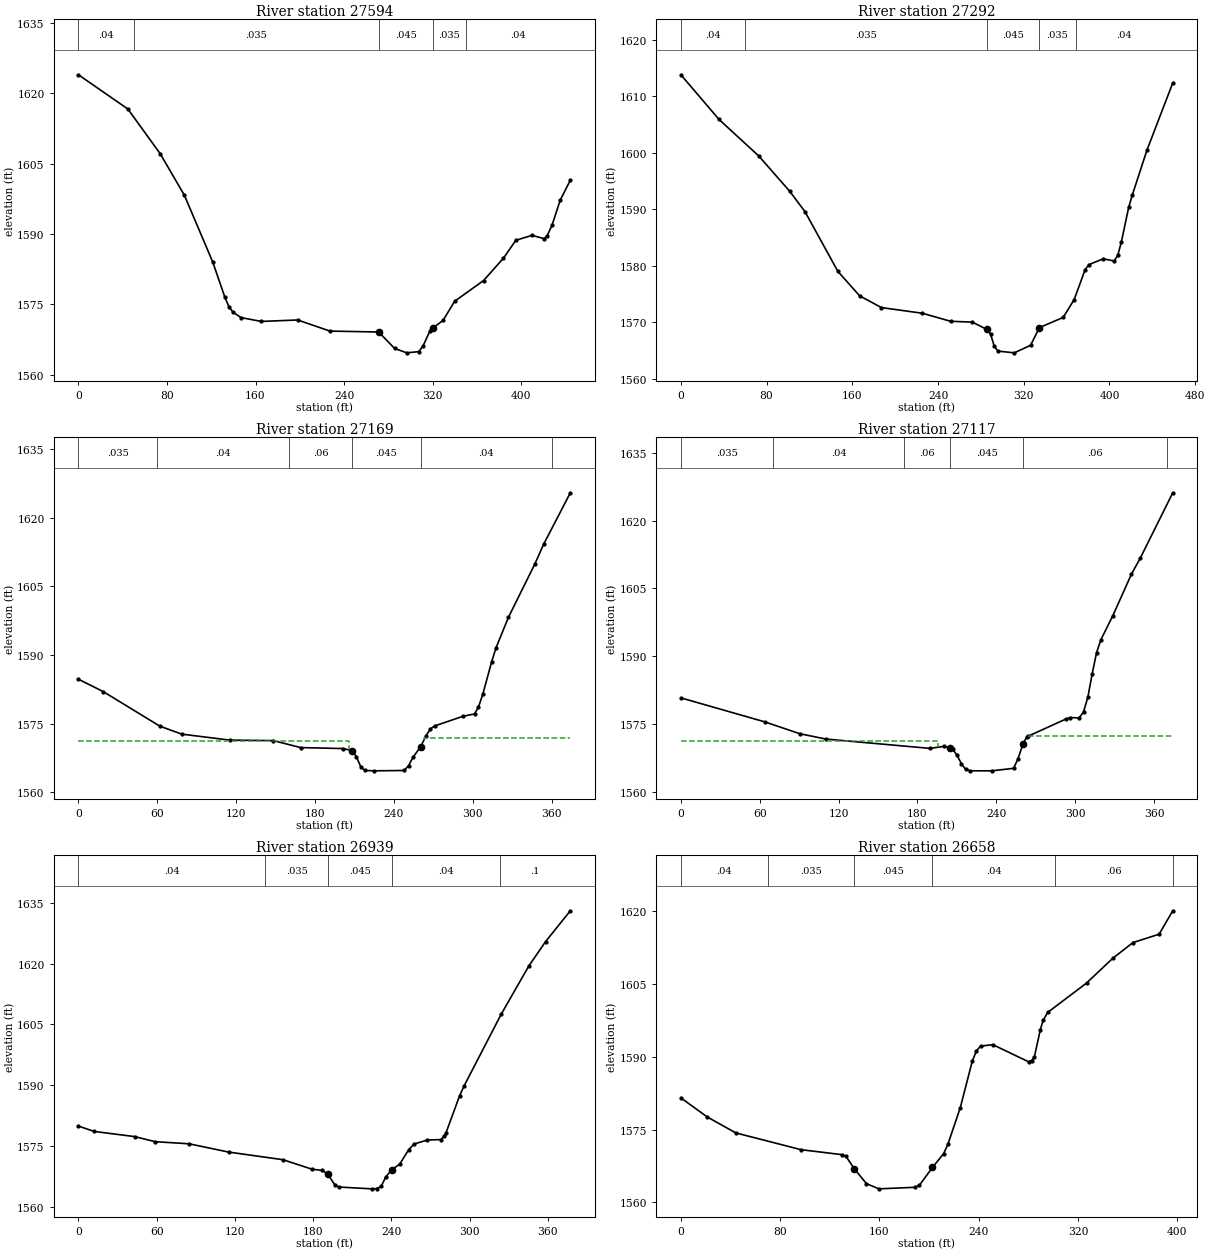
Type RM Length L Ch R = 1 ,27594   ,294.5,301.4,308
XS GIS Cut Line= 2
     2074871.355      244708.951      2075270.66      244513.639
#Sta/Elev= 30
       0 1623.98    44.7 1616.67    73.9 1607.13    95.8 1598.25   121.4 1584.01
   132.3 1576.54     136 1574.49   139.6 1573.35   146.9 1572.18   165.2 1571.36
   198.1 1571.67   227.3  1569.3   271.31569.103   285.7  1565.6   296.7 1564.66
   307.6 1564.92   311.3 1566.08   317.8  1569.4   320.3 1569.96   329.5 1571.58
   339.9 1575.65   366.1 1580.08   384.1 1584.86   395.3 1588.68   409.9 1589.72
   420.8 1589.02   423.3  1589.5     428 1591.91   435.4 1597.26   444.5 1601.48
#Mann= 5 ,-1 , 0
       0     .04       0      50    .035       0   271.3    .045       0
   320.3    .035       0     350     .04       0
Bank Sta=271.3,320.3
XS Rating Curve= 0 ,0
Exp/Cntr=0.3,0.1

Type RM Length L Ch R = 1 ,27292   ,120.4,123.4,128
XS GIS Cut Line= 3
     2074930.382      244868.239     2075038.455      244916.416
     2075367.882      244829.177
#Sta/Elev= 30
       0 1613.79    35.6 1605.89    72.7 1599.43   101.4 1593.23   115.8  1589.6
   146.5 1579.04   166.8 1574.71   187.2 1572.63   225.4 1571.63   251.7 1570.21
   272.1 1570.06   285.41568.786     289 1567.97   292.4 1565.86   295.8 1564.94
   311.2 1564.63   326.4 1565.97   334.61569.089   356.9  1570.9   367.1 1574.06
   377.3 1579.34   380.7 1580.22   394.2 1581.25   404.4 1580.87   407.8 1581.88
   411.2  1584.3     418  1590.4   421.3 1592.51     435 1600.47   459.1 1612.35
#Mann= 5 ,-1 , 0
       0     .04       0      60    .035       0   285.4    .045       0
   334.6    .035       0  368.32     .04       0
Bank Sta=285.4,334.6
XS Rating Curve= 0 ,0
Exp/Cntr=0.5,0.3

Type RM Length L Ch R = 1 ,27169   ,53.9,51.8,52.4
XS GIS Cut Line= 2
     2075024.132      245023.187     2075393.924      244965.895
#Sta/Elev= 30
       0 1584.71    18.8 1582.01      62 1574.43    78.6  1572.7   115.1 1571.39
   148.3 1571.28     169 1569.76   201.4 1569.54   208.21569.101   211.4 1567.79
     215 1565.41     218 1564.76   224.6 1564.67   247.9 1564.75   251.2 1565.83
   254.5 1567.62   260.31569.927   264.5 1572.38   267.8 1573.85   271.1  1574.5
   292.6 1576.61   301.3 1577.11   304.3 1578.61   307.6 1581.41   314.3 1588.49
   317.6 1591.52   327.1 1598.24   347.3 1609.97   354.1 1614.35   374.2 1625.49
#Mann= 6 ,-1 , 0
       0    .035       0      60     .04       0     160     .06       0
   208.2    .045       0   260.3     .04       0     360      .1       0
#XS Ineff= 2 , 0
          205.66 1571.15  263.03         1571.92
Permanent Ineff=
       F       F
Bank Sta=208.2,260.3
XS Rating Curve= 0 ,0
Exp/Cntr=0.5,0.3

Type RM Length L Ch R = 1 ,27117   ,160.6,178.4,200.5
XS GIS Cut Line= 2
     2075018.924       245075.27     2075388.716      245017.979
#Sta/Elev= 30
       0 1580.79    63.9 1575.47    90.5 1572.85   110.4 1571.67   189.5 1569.61
     200 1570.05     2051569.693   206.7 1569.42     210 1568.14   213.3 1566.26
   216.6 1564.96   219.9 1564.65   236.5 1564.64   253.1  1565.2   256.5 1567.33
   260.31570.644   263.1 1572.14   264.1  1572.3     293 1576.12   296.3 1576.44
   302.9 1576.34   306.3 1577.69   309.6 1580.95   312.9 1586.12   316.2 1590.78
   319.5 1593.64   328.5 1598.92   342.8  1608.2   349.4 1611.67   374.2 1626.18
#Mann= 6 ,-1 , 0
       0    .035       0      70     .04       0     170     .06       0
     205    .045       0   260.3     .06       0     370      .1       0
#XS Ineff= 2 , 0
          195.56 1571.31  263.84         1572.39
Permanent Ineff=
       F       F
Bank Sta=205,260.3
XS Rating Curve= 0 ,0
Exp/Cntr=0.5,0.3

Type RM Length L Ch R = 1 ,26939   ,245.3,281.1,325
XS GIS Cut Line= 3
     2075015.018      245092.198     2075074.914      245163.812
     2075337.935      245270.583
#Sta/Elev= 30
       0 1579.88    12.1 1578.56    43.2 1577.28    58.8 1576.03    84.8 1575.51
   115.2 1573.46   156.8 1571.58     179 1569.24     187 1568.92   191.21567.999
   196.7 1565.32   199.6 1564.83   224.8 1564.38   228.6 1564.43   232.1 1564.97
   235.6 1567.27   240.21569.109   246.3 1570.45   253.3 1574.08   257.5 1575.47
   267.6 1576.44   278.1 1576.55   280.2 1577.36   281.7 1578.08   292.3 1587.38
   295.8 1589.85   324.2 1607.53   345.4 1619.45   358.2 1625.45   377.2 1633.07
#Mann= 5 ,-1 , 0
       0     .04       0  143.36    .035       0   191.2    .045       0
   240.2     .04       0  323.36      .1       0
Bank Sta=191.2,240.2
XS Rating Curve= 0 ,0
Exp/Cntr=0.3,0.1

Type RM Length L Ch R = 1 ,26658   ,218.6,183.9,149.4
XS GIS Cut Line= 3
     2074940.799      245113.031     2074956.424      245364.333
     2075046.268      245477.614
#Sta/Elev= 30
       0 1581.53    21.3 1577.58    44.3  1574.3    96.9 1570.84   129.8 1569.82
     133 1569.49   139.6 1566.96   149.5 1563.85   159.5 1562.77   188.9 1563.09
   192.2  1563.5   202.71567.173   211.8 1570.04   215.2 1571.99   225.1 1579.45
   234.9 1589.17   238.2 1591.22   241.5  1592.2   251.4  1592.5   280.2 1588.97
   282.6 1589.22   284.8 1589.92   289.6  1595.5   291.9 1597.53   295.6 1599.15
   326.9  1605.2   347.9 1610.28   364.3 1613.55   385.4 1615.28   396.4 1620.11
#Mann= 6 ,-1 , 0
       0     .04       0      70    .035       0   139.6    .045       0
   202.7     .04       0  301.79     .06       0  396.37      .1       0
Bank Sta=139.6,202.7
XS Rating Curve= 0 ,0
Exp/Cntr=0.3,0.1