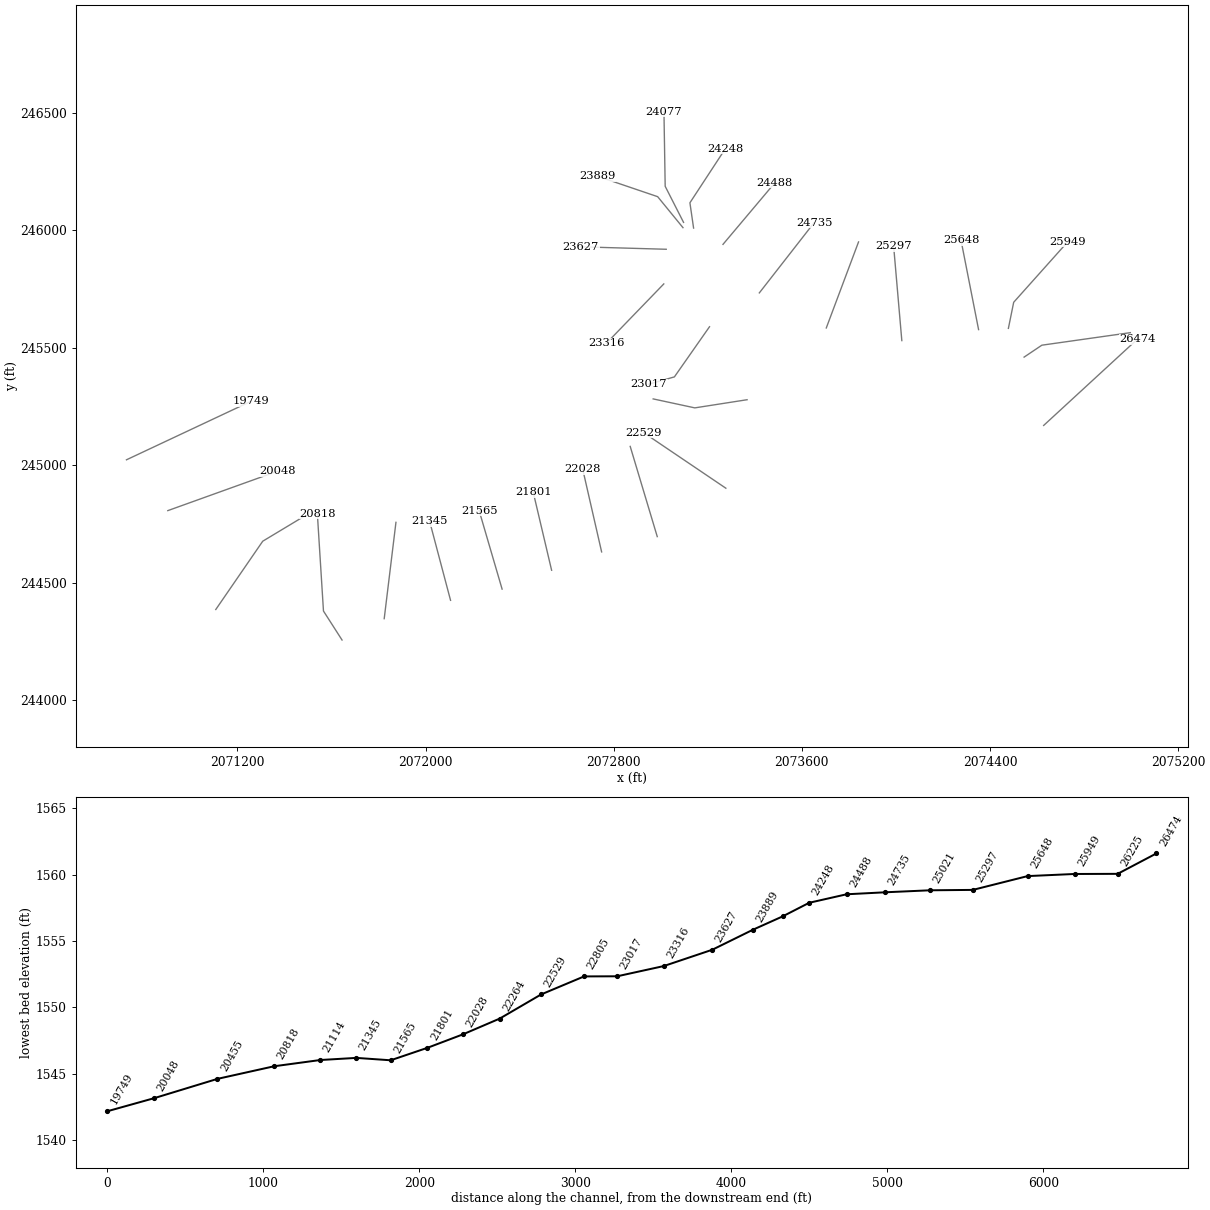
HEC-RAS study WOLFCK.prj: WOLFCK

--- WOLFCK.g01 (geometry) --- (continued)

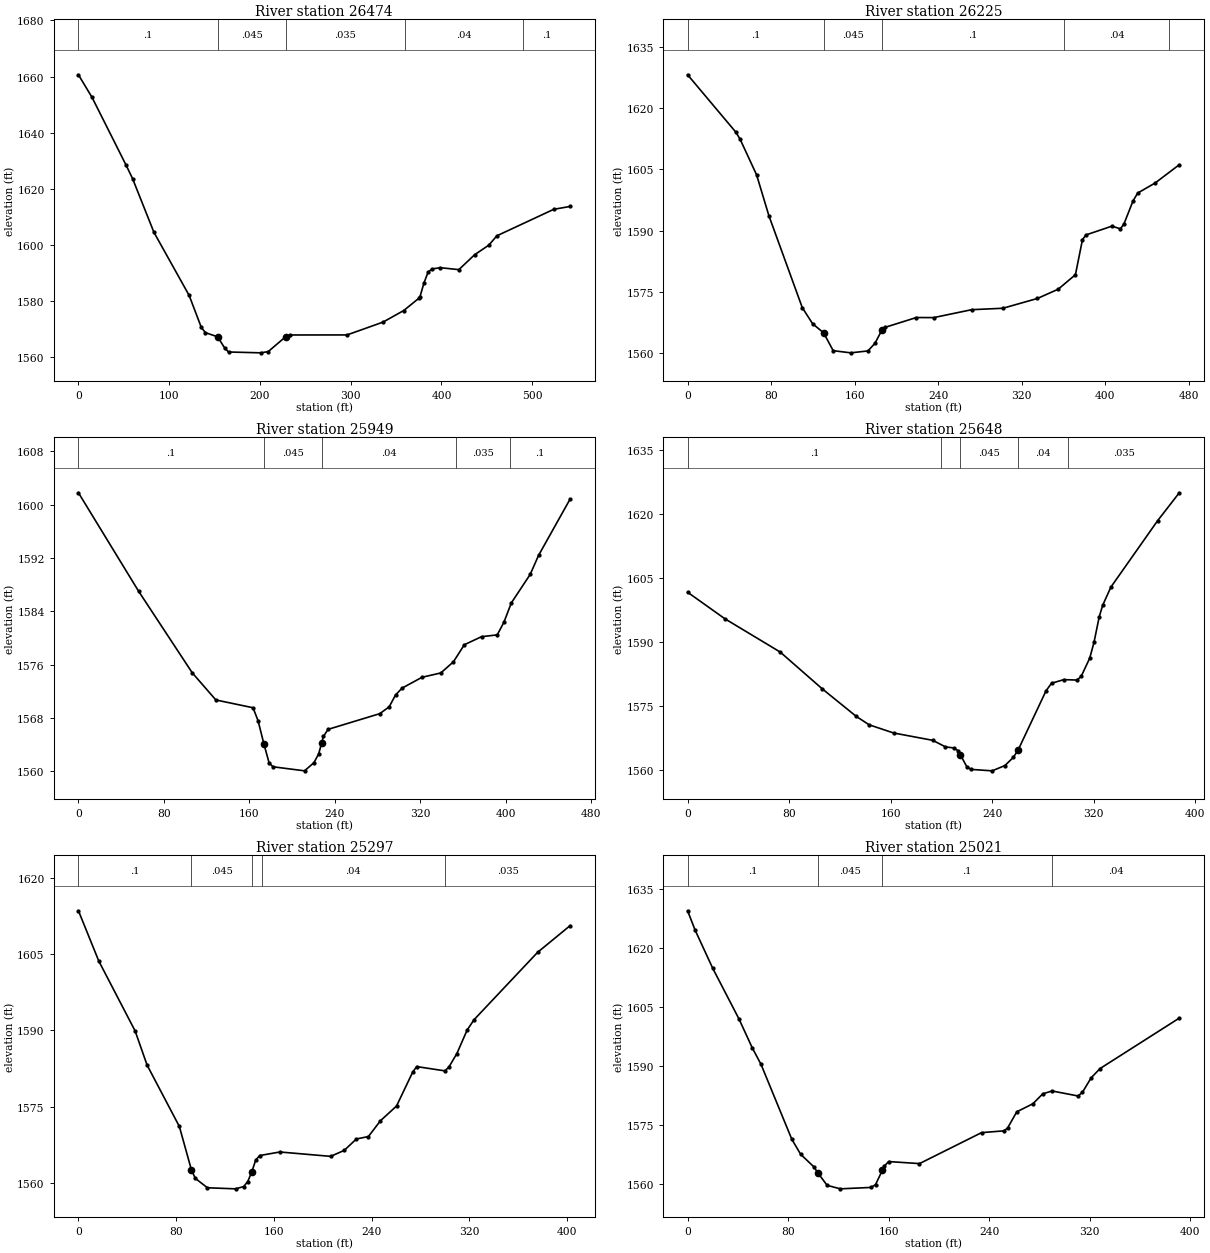
Type RM Length L Ch R = 1 ,26474   ,273.2,248.7,221.8
XS GIS Cut Line= 2
     2074628.162      245169.758     2075026.599      245536.946
#Sta/Elev= 30
       0 1660.66      15  1652.6    52.3  1628.6    59.6 1623.71    83.2 1604.53
     122 1582.06   135.4 1570.67   139.9  1568.8   153.41567.318   161.4 1563.19
   165.5 1561.91   200.9 1561.61   209.1 1562.05   228.51567.393   233.4 1567.97
     296 1567.99   335.6 1572.55   358.5 1576.69   375.1 1581.04   376.3 1581.53
   380.8 1586.55   385.3 1590.36   389.7 1591.49   398.7 1591.94   419.2 1591.25
   436.6 1596.56   452.2 1599.97   461.1  1603.3   523.7 1612.73   541.8 1613.76
#Mann= 5 ,-1 , 0
       0      .1       0   153.4    .045       0   228.5    .035       0
     360     .04       0     490      .1       0
Bank Sta=153.4,228.5
XS Rating Curve= 0 ,0
Exp/Cntr=0.3,0.1

Type RM Length L Ch R = 1 ,26225   ,246.4,276.3,304.2
XS GIS Cut Line= 3
     2074544.966      245460.687     2074620.487      245511.468
     2074996.789      245564.854
#Sta/Elev= 30
       0 1628.18    46.3  1614.1    50.3  1612.4    66.1 1603.67    77.9 1593.65
   109.9 1571.13   119.8 1567.19   130.31564.982   139.5  1560.6   156.3 1560.07
   172.8 1560.54   179.5  1562.4     186 1565.56   189.4 1566.33   219.2 1568.72
   235.8  1568.7   272.2 1570.64   302.1 1570.99   335.2 1573.39   355.1 1575.66
   371.6 1579.21   378.3 1587.76   381.6 1588.94   406.5  1591.1   414.7 1590.45
   418.1 1591.65   426.8 1597.29   431.3 1599.22   447.9 1601.66   471.1 1606.15
#Mann= 5 ,-1 , 0
       0      .1       0   130.3    .045       0     186      .1       0
  361.01     .04       0  461.01      .1       0
Bank Sta=130.3,186
XS Rating Curve= 0 ,0
Exp/Cntr=0.3,0.1

Type RM Length L Ch R = 1 ,25949   ,258.4,300.9,334
XS GIS Cut Line= 3
     2074478.126      245583.083     2074500.695      245694.194
     2074731.598      245952.875
#Sta/Elev= 30
       0 1601.76    56.4 1586.97   106.5 1574.76   128.6 1570.69   163.4 1569.52
   168.1 1567.57   173.5 1564.12   178.4 1561.26     182 1560.67   211.6 1560.06
   220.4 1561.29   224.8  1562.6   227.7  1564.3   229.2 1565.21   233.6 1566.28
   281.9 1568.63   290.8 1569.66   296.7 1571.43   302.8 1572.46   321.5 1574.09
   339.1 1574.74   350.9 1576.41   361.1 1578.97   377.2 1580.18   391.9 1580.45
   398.1 1582.33   405.1 1585.25   422.7 1589.51   430.6 1592.38   460.1 1600.82
#Mann= 5 ,-1 , 0
       0      .1       0   173.5    .045       0   227.7     .04       0
  353.38    .035       0  403.38      .1       0
Bank Sta=173.5,227.7
XS Rating Curve= 0 ,0
Exp/Cntr=0.3,0.1

Type RM Length L Ch R = 1 ,25648   ,354.1,351.1,340.2
XS GIS Cut Line= 2
     2074351.389      245577.875     2074276.737      245958.083
#Sta/Elev= 30
       0 1601.69    29.4 1595.48      73 1587.69   106.1 1579.09     133 1572.62
   143.1 1570.67   162.3 1568.76   193.2 1567.04   203.2 1565.51   209.9 1565.25
   213.3 1564.59   214.91563.689     220 1560.88   223.3 1560.24     240  1559.9
   250.1 1561.14   256.7 1563.05   260.51564.782   282.5 1578.63   286.8 1580.39
   296.5 1581.24   306.9 1581.14   310.2 1582.01   316.9 1586.25   320.3 1589.98
   324.4 1595.95   327.2 1598.69   333.6 1602.89   370.4 1618.42   387.5 1624.96
#Mann= 5 ,-1 , 0
       0      .1       0     200     .04       0   214.9    .045       0
   260.5     .04       0     300    .035       0
Bank Sta=214.9,260.5
XS Rating Curve= 0 ,0
Exp/Cntr=0.3,0.1

Type RM Length L Ch R = 1 ,25297   ,290.9,275.3,256.1
XS GIS Cut Line= 2
     2074025.001         245531.     2073990.278      245932.041
#Sta/Elev= 30
       0 1613.49    16.7 1603.59    46.4 1589.88    56.2 1583.17    82.6 1571.12
    92.5 1562.57    95.7 1560.91   105.6 1559.07   128.7 1558.86   135.3 1559.31
   138.6  1560.3   141.9 1562.18   145.1 1564.51   148.4  1565.4   164.9  1566.1
   206.5 1565.24   217.6 1566.42   227.5 1568.65   237.4 1569.14   247.2 1572.23
   260.4 1575.13   273.6 1581.78   276.9 1582.88   299.9 1582.04   303.2 1582.76
   309.8 1585.44   318.2 1590.06   323.9  1592.1   375.9 1605.33   402.5 1610.57
#Mann= 5 ,-1 , 0
       0      .1       0    92.5    .045       0   141.9      .1       0
     150     .04       0     300    .035       0
Bank Sta=92.5,141.9
XS Rating Curve= 0 ,0
Exp/Cntr=0.3,0.1

Type RM Length L Ch R = 1 ,25021   ,297.4,286,274.8
XS GIS Cut Line= 2
      2073703.82      245584.819     2073840.973      245951.139
#Sta/Elev= 30
       0 1629.46     5.9 1624.61    19.9 1614.91    40.9 1601.97    51.4 1594.67
    58.4 1590.46    82.9 1571.43    89.9 1567.63   100.4 1564.43   103.8 1562.81
     111 1559.72   121.5 1558.83     146 1559.19   149.5  1559.9   154.9 1563.49
   156.5 1564.61     160 1565.76   184.5 1565.24   233.9 1573.11   251.7 1573.56
   254.6 1574.28   261.9  1578.4   274.7 1580.43   282.6 1582.97     290 1583.69
   310.6 1582.42   314.1 1583.33   321.1 1587.04   328.2 1589.39   391.2  1602.2
#Mann= 4 ,-1 , 0
       0      .1       0   103.8    .045       0   154.9      .1       0
     290     .04       0
Bank Sta=103.8,154.9
XS Rating Curve= 0 ,0
Exp/Cntr=0.3,0.1

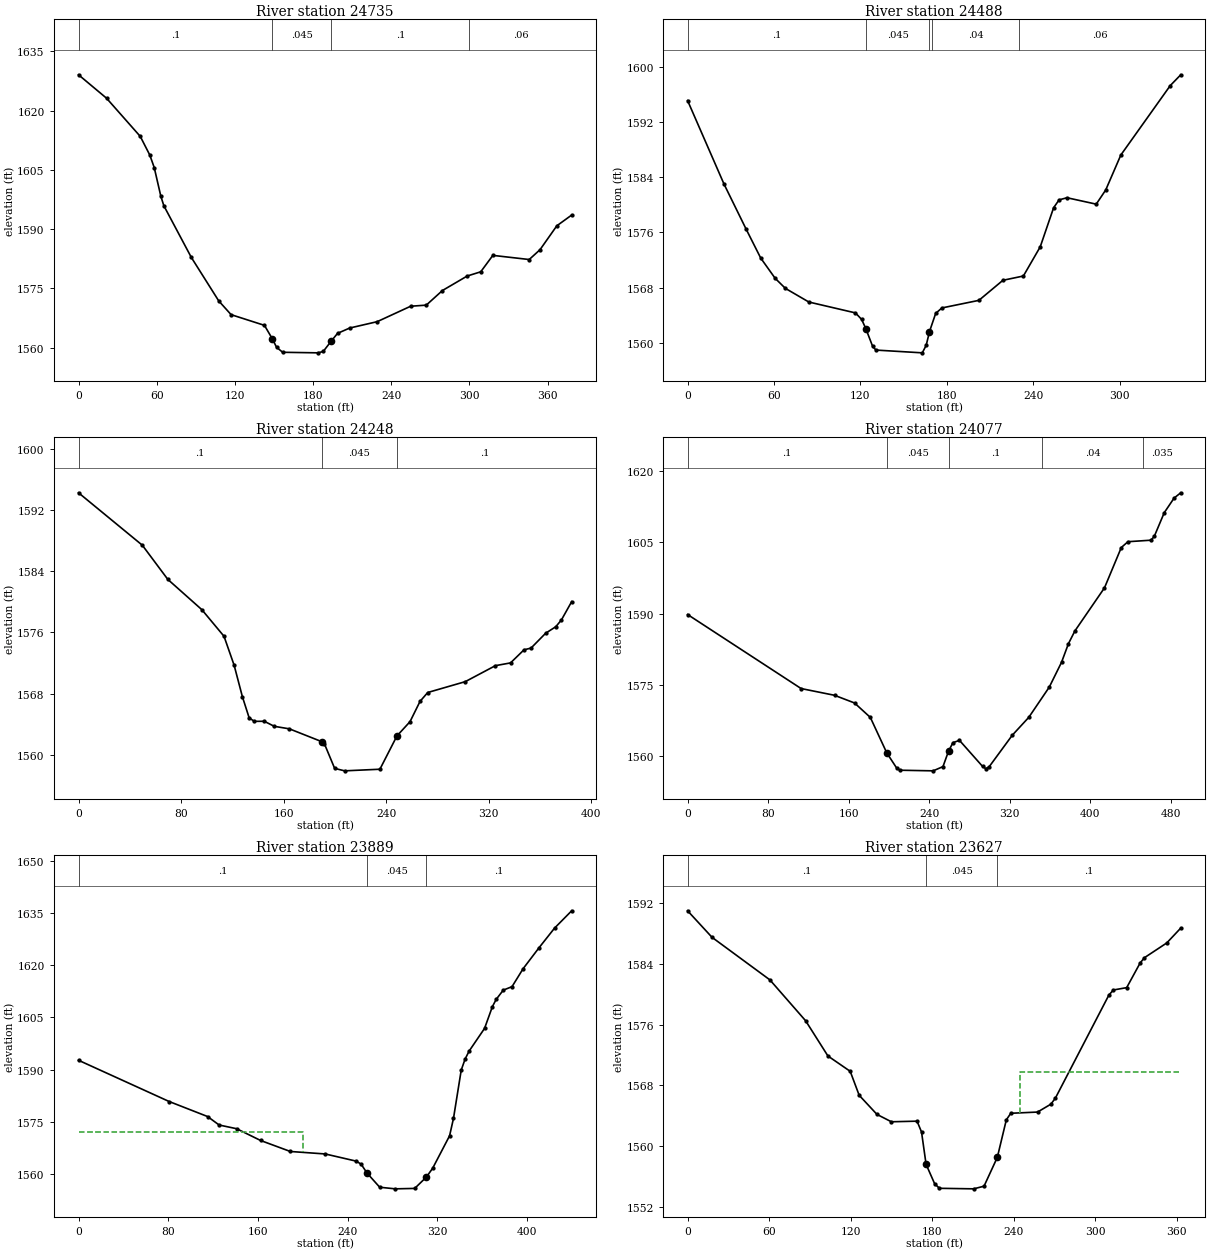
Type RM Length L Ch R = 1 ,24735   ,248.9,247.7,245.7
XS GIS Cut Line= 2
     2073419.098      245734.125     2073651.737      246032.736
#Sta/Elev= 30
       0 1629.09    21.5 1623.16    47.4 1613.48    54.7 1608.77    58.1 1605.61
    63.2 1598.31    65.5 1595.92    86.6 1582.83   107.6 1571.84   117.1 1568.35
   142.7 1565.64   148.8  1562.2     152 1560.09   156.7 1558.82   183.7 1558.68
   187.8 1559.02   194.1 1561.71   198.8 1563.61   208.1 1564.96   229.2 1566.57
   254.9 1570.48   266.9 1570.76   279.3 1574.46   298.3 1578.13   308.7  1579.2
     318 1583.36   345.9 1582.31   354.2  1584.8   367.1 1590.85   378.5 1593.57
#Mann= 4 ,-1 , 0
       0      .1       0   148.8    .045       0   194.1      .1       0
     300     .06       0
Bank Sta=148.8,194.1
XS Rating Curve= 0 ,0
Exp/Cntr=0.3,0.1

Type RM Length L Ch R = 1 ,24488   ,236.4,239.7,244.9
XS GIS Cut Line= 2
     2073264.584      245940.722      2073485.07      246202.875
#Sta/Elev= 30
       0 1595.11    25.3    1583    40.6 1576.49    50.8 1572.27    60.8 1569.34
    67.9 1567.88    84.2  1565.9   116.6 1564.32   120.9 1563.37   123.8 1562.03
   128.5 1559.48   130.8 1558.93     163 1558.53   165.7 1559.62     168 1561.59
     168 1561.61   172.3 1564.25   176.6 1565.04   202.3 1566.14     219 1569.05
   233.2 1569.67   244.9  1573.9   254.2 1579.57     258 1580.71   263.5 1581.02
   283.8 1580.09   290.4 1582.15   300.9 1587.22   335.2 1597.28   342.5 1598.85
#Mann= 5 ,-1 , 0
       0      .1       0   123.8    .045       0     168      .1       0
     170     .04       0     230     .06       0
Bank Sta=123.8,168
XS Rating Curve= 0 ,0
Exp/Cntr=0.3,0.1

Type RM Length L Ch R = 1 ,24248   ,148.2,171,197.5
XS GIS Cut Line= 3
     2073139.584      246010.166     2073123.959      246117.805
     2073275.001      246348.708
#Sta/Elev= 30
       0 1594.24    49.8 1587.38    69.7 1582.91    96.2 1578.96   113.5 1575.48
   121.4 1571.69   127.8  1567.6   133.1 1564.82   137.1 1564.36   144.9 1564.37
   152.7 1563.71   164.5 1563.38   189.91561.695   191.8 1561.43   199.8 1558.21
   207.6 1557.89   235.1  1558.1   248.41562.456   258.6 1564.32   266.4 1566.97
   272.4 1568.13   301.7 1569.55   325.2 1571.64     337    1572   347.5 1573.71
     353 1573.94   364.4 1575.88   372.3 1576.73   376.7 1577.62   384.7 1580.01
#Mann= 3 ,-1 , 0
       0      .1       0   189.9    .045       0   248.4      .1       0
Bank Sta=189.9,248.4
XS Rating Curve= 0 ,0
Exp/Cntr=0.3,0.1

Type RM Length L Ch R = 1 ,24077   ,134.9,187.6,233
XS GIS Cut Line= 3
     2073096.912      246034.342     2073018.787      246187.988
     2073013.578      246505.696
#Sta/Elev= 30
       0  1589.8   112.8  1574.2     146 1572.78   165.9 1571.16   181.6 1568.12
     198 1560.62   207.9 1557.41   211.2 1556.99     244 1556.86   253.8 1557.75
   259.3 1560.99   263.7  1562.8   270.2 1563.28   293.2 1557.78   296.5  1557.3
   299.8 1557.75   322.7 1564.37   339.1 1568.14   359.4 1574.49   371.6 1579.72
   378.5 1583.66   384.9 1586.34   414.3 1595.42     431 1603.91   437.6 1605.14
   460.5 1605.46   463.8 1606.27   473.7 1611.26   483.5 1614.34   490.1 1615.45
#Mann= 5 ,-1 , 0
       0      .1       0     198    .045       0   259.3      .1       0
  352.37     .04       0  452.37    .035       0
Bank Sta=198,259.3
XS Rating Curve= 0 ,0
Exp/Cntr=0.3,0.1

Type RM Length L Ch R = 1 ,23889   ,250.1,262.7,275.2
XS GIS Cut Line= 3
     2073094.445      246011.902     2072986.806      246143.847
     2072731.598      246230.652
#Sta/Elev= 30
       0 1592.73    80.8 1580.91   115.1  1576.6   125.4 1574.17     141 1573.11
   162.4 1569.73   188.9 1566.58     220 1565.87   247.8  1563.8   252.1 1562.91
   257.3 1560.39   268.6 1556.33   282.4 1555.87   299.8 1555.99   310.2 1559.24
   315.8 1561.76   330.9 1571.07   334.4 1576.08   341.3 1589.93   344.8 1593.11
   348.3 1595.35   362.1 1601.87   369.1 1608.12   372.5  1610.2   378.8 1612.84
   386.6 1613.84   396.5 1618.99   410.6 1624.96   424.5 1630.61   439.8 1635.59
#Mann= 3 ,-1 , 0
       0      .1       0   257.3    .045       0   310.2      .1       0
#XS Ineff= 2 , 0
          199.91 1572.16
Permanent Ineff=
       F       F
Bank Sta=257.3,310.2
XS Rating Curve= 0 ,0
Exp/Cntr=0.3,0.1

Type RM Length L Ch R = 1 ,23627   ,270.8,311.1,344
XS GIS Cut Line= 2
     2073023.264      245919.889     2072660.417      245930.305
#Sta/Elev= 30
       0    1591      18  1587.5    60.6 1581.89    86.9  1576.5   103.3 1571.86
   119.7 1569.84   126.3 1566.68   139.4 1564.16     150 1563.19   168.9 1563.27
   172.2 1561.84   175.5 1557.64   175.5  1557.6   181.9    1555   185.4 1554.42
   210.6 1554.35   218.2  1554.7     228 1558.51   234.6 1563.44   237.9 1564.31
   257.6 1564.47   267.4 1565.51   270.7  1566.3   310.1 1579.89   313.4 1580.56
   323.2 1580.87   333.1 1584.12   336.3 1584.82   352.7 1586.76     363 1588.72
#Mann= 3 ,-1 , 0
       0      .1       0   175.5    .045       0     228      .1       0
#XS Ineff= 2 , 0
                          244.85         1569.81
Permanent Ineff=
       F       F
Bank Sta=175.5,228
XS Rating Curve= 0 ,0
Exp/Cntr=0.3,0.1

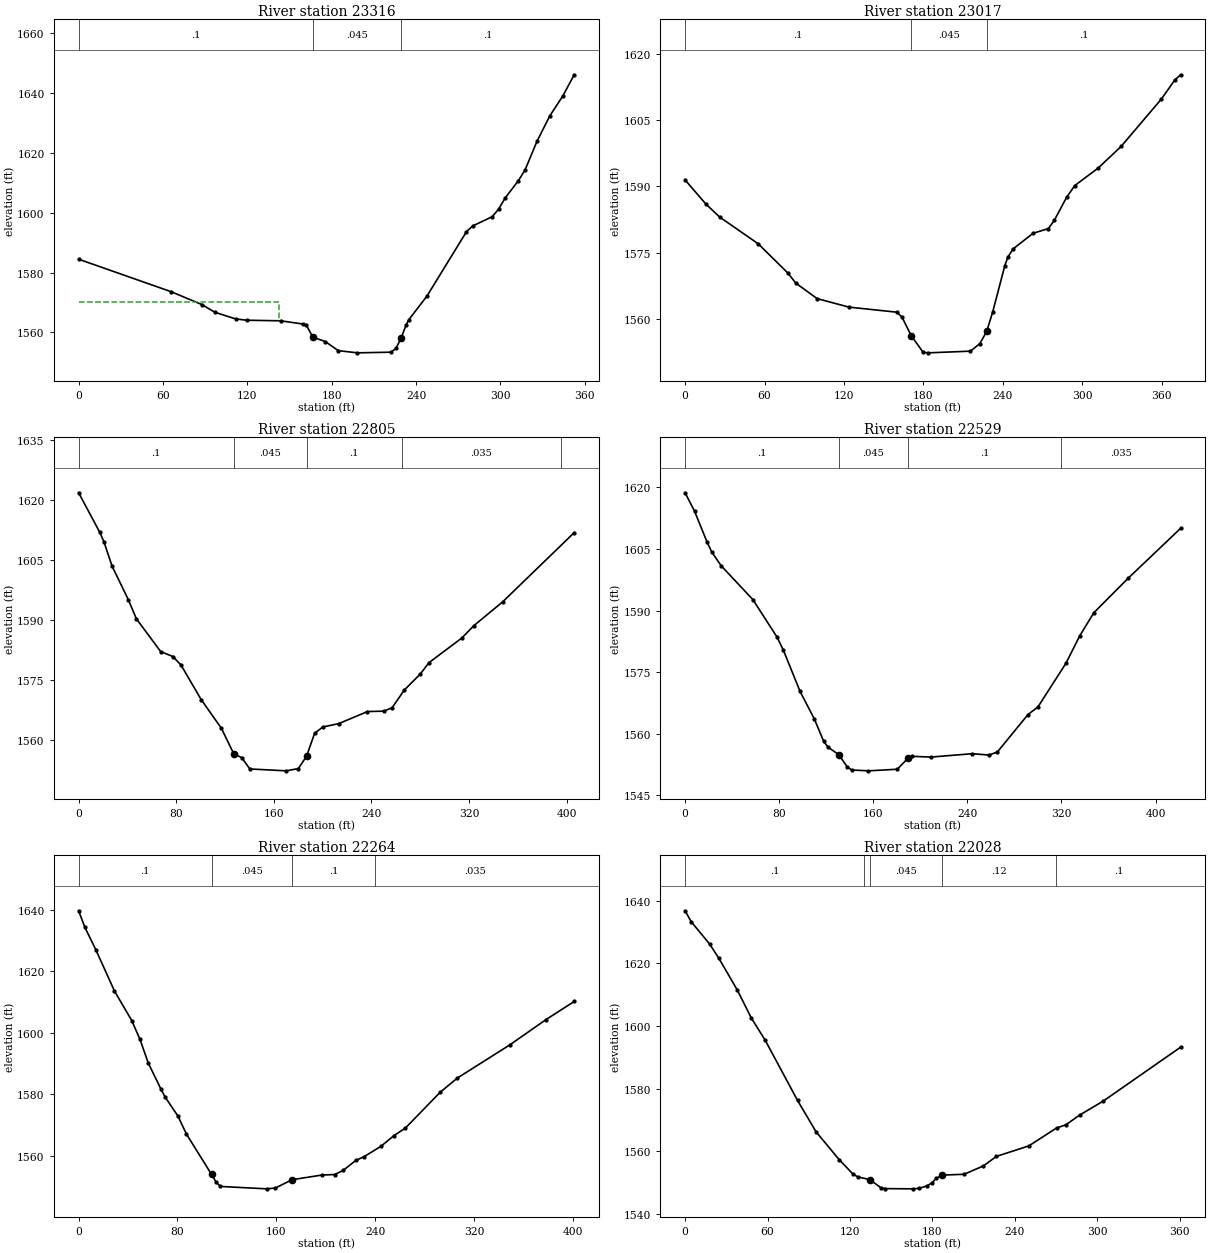
Type RM Length L Ch R = 1 ,23316   ,290.7,298.4,304.6
XS GIS Cut Line= 2
     2073012.848      245772.319     2072768.056      245518.847
#Sta/Elev= 30
       0 1584.45      66 1573.54    87.7 1569.26    96.9 1566.69   111.6 1564.48
   119.5 1564.03   143.6 1563.84   159.6 1562.76     162 1562.33   166.5 1558.39
   175.5 1556.88   184.6 1553.86   198.3 1553.12   222.2 1553.34   225.7 1554.63
   229.2 1557.92   232.8 1562.33   234.8 1564.19   247.8 1572.18   275.8 1593.65
   280.2 1595.58   294.2 1598.68   298.7 1601.27   303.4 1604.97   312.7 1610.72
   317.4 1614.23     326 1623.95   335.1 1632.43   344.3 1639.04   352.4 1646.16
#Mann= 3 ,-1 , 0
       0      .1       0   166.5    .045       0   229.2      .1       0
#XS Ineff= 2 , 0
          142.54 1570.28
Permanent Ineff=
       F       F
Bank Sta=166.5,229.2
XS Rating Curve= 0 ,0
Exp/Cntr=0.3,0.1

Type RM Length L Ch R = 1 ,23017   ,248.7,212.4,180.5
XS GIS Cut Line= 3
     2073207.292      245590.027     2073057.987      245376.486
     2072948.612      245345.236
#Sta/Elev= 30
       0 1591.46    15.7 1586.01    26.1 1583.07    55.3    1577    77.7 1570.38
    83.6 1568.13    99.7 1564.62   123.8 1562.69   159.8 1561.55   163.8 1560.45
   170.8 1556.23   179.8 1552.47   183.8 1552.35   215.5 1552.73   222.6 1554.42
   227.8  1557.2   232.3 1561.55   241.4 1571.96   243.8 1574.04   247.9 1575.89
   262.9 1579.41   274.4 1580.45   278.8 1582.29   288.1 1587.49   294.3 1590.18
   311.9 1594.12   329.3 1599.03   359.7 1609.74   369.9 1614.08   374.3 1615.25
#Mann= 3 ,-1 , 0
       0      .1       0   170.8    .045       0   227.8      .1       0
Bank Sta=170.8,227.8
XS Rating Curve= 0 ,0
Exp/Cntr=0.3,0.1

Type RM Length L Ch R = 1 ,22805   ,307.2,275.5,246.9
XS GIS Cut Line= 3
     2073367.014      245279.264     2073144.792      245244.541
     2072967.709      245282.736
#Sta/Elev= 30
       0 1621.81    17.4 1611.89    20.8 1609.51    27.4 1603.48    40.7 1595.12
    47.3 1590.34    67.2 1582.15    77.2  1580.9    83.8 1578.82   100.4 1570.15
     117 1562.97   127.11556.601   133.7 1555.63   140.3 1552.81   170.2 1552.34
   180.1 1552.91   186.8 1556.01   193.4 1561.73   200.1 1563.29   213.3 1564.15
   236.7 1567.15   250.1 1567.25   256.9 1568.11   266.9 1572.53   279.9  1576.5
   287.1 1579.37   313.9 1585.49     324 1588.64   347.5 1594.56   406.1 1611.85
#Mann= 5 ,-1 , 0
       0      .1       0   127.1    .045       0   186.8      .1       0
  264.92    .035       0  394.92      .1       0
Bank Sta=127.1,186.8
XS Rating Curve= 0 ,0
Exp/Cntr=0.3,0.1

Type RM Length L Ch R = 1 ,22529   ,293.7,265.5,237.5
XS GIS Cut Line= 2
     2073276.737      244902.527     2072927.778      245138.639
#Sta/Elev= 30
       0 1618.65       8 1614.19    18.7 1606.64    22.7 1604.22    30.6 1600.91
    57.6 1592.66    78.2 1583.52    83.6 1580.31    97.7 1570.34   109.9 1563.59
   117.8 1558.18   121.7 1556.69   130.61554.947   137.6 1552.03   141.5 1551.19
   155.9 1550.98   180.4 1551.37   189.41554.024     193 1554.51   208.9 1554.33
   244.2 1555.15   258.4 1554.82   265.5 1555.57   291.5 1564.67     300 1566.54
   323.8 1577.16   335.6 1583.87   347.5 1589.46   376.5  1597.8   421.3    1610
#Mann= 4 ,-1 , 0
       0      .1       0   130.6    .045       0   189.4      .1       0
     320    .035       0
Bank Sta=130.6,189.4
XS Rating Curve= 0 ,0
Exp/Cntr=0.3,0.1

Type RM Length L Ch R = 1 ,22264   ,239.4,236.2,233.1
XS GIS Cut Line= 2
      2072985.07      244696.364     2072870.053      245080.479
#Sta/Elev= 30
       0 1639.61       5 1634.27      14 1626.86      29 1613.51      43 1603.89
    49.6 1597.81    56.4 1590.04    66.7 1581.53    70.1 1578.96    80.4  1572.8
    87.2 1567.01   107.61553.825   111.2 1551.43   114.6 1549.94   152.3 1549.16
   159.2 1549.43   172.81552.138   196.8 1553.64   207.1 1553.81     214 1555.13
   224.2 1558.39   231.1 1559.64   244.8 1563.05   255.1 1566.45   264.4 1568.92
   292.7 1580.63   306.5 1585.21   348.7 1595.93   378.3 1604.24     401  1610.1
#Mann= 4 ,-1 , 0
       0      .1       0   107.6    .045       0   172.8      .1       0
     240    .035       0
Bank Sta=107.6,172.8
XS Rating Curve= 0 ,0
Exp/Cntr=0.3,0.1

Type RM Length L Ch R = 1 ,22028   ,226.3,226.6,226.8
XS GIS Cut Line= 2
     2072748.525       244631.26      2072668.23      244982.823
#Sta/Elev= 30
       0  1636.8     4.4 1633.32    17.9 1626.15    24.6  1621.6    38.1  1611.4
    48.2 1602.53    58.3 1595.43    81.8 1576.23    95.3 1566.19   112.1 1557.31
   122.2 1552.68   125.6  1551.8   134.4 1550.91   142.6 1548.28   145.8 1548.04
     166 1547.97     170 1548.11   176.1 1548.91   179.4 1549.83   182.8  1551.3
   186.91552.359     203 1552.62   217.1  1555.3   226.5 1558.33   250.1 1561.68
   270.3 1567.41     277  1568.4   287.1 1571.54   304.2 1575.98   360.6 1593.23
#Mann= 5 ,-1 , 0
       0      .1       0     130     .12       0   134.4    .045       0
   186.9     .12       0     270      .1       0
Bank Sta=134.4,186.9
XS Rating Curve= 0 ,0
Exp/Cntr=0.3,0.1

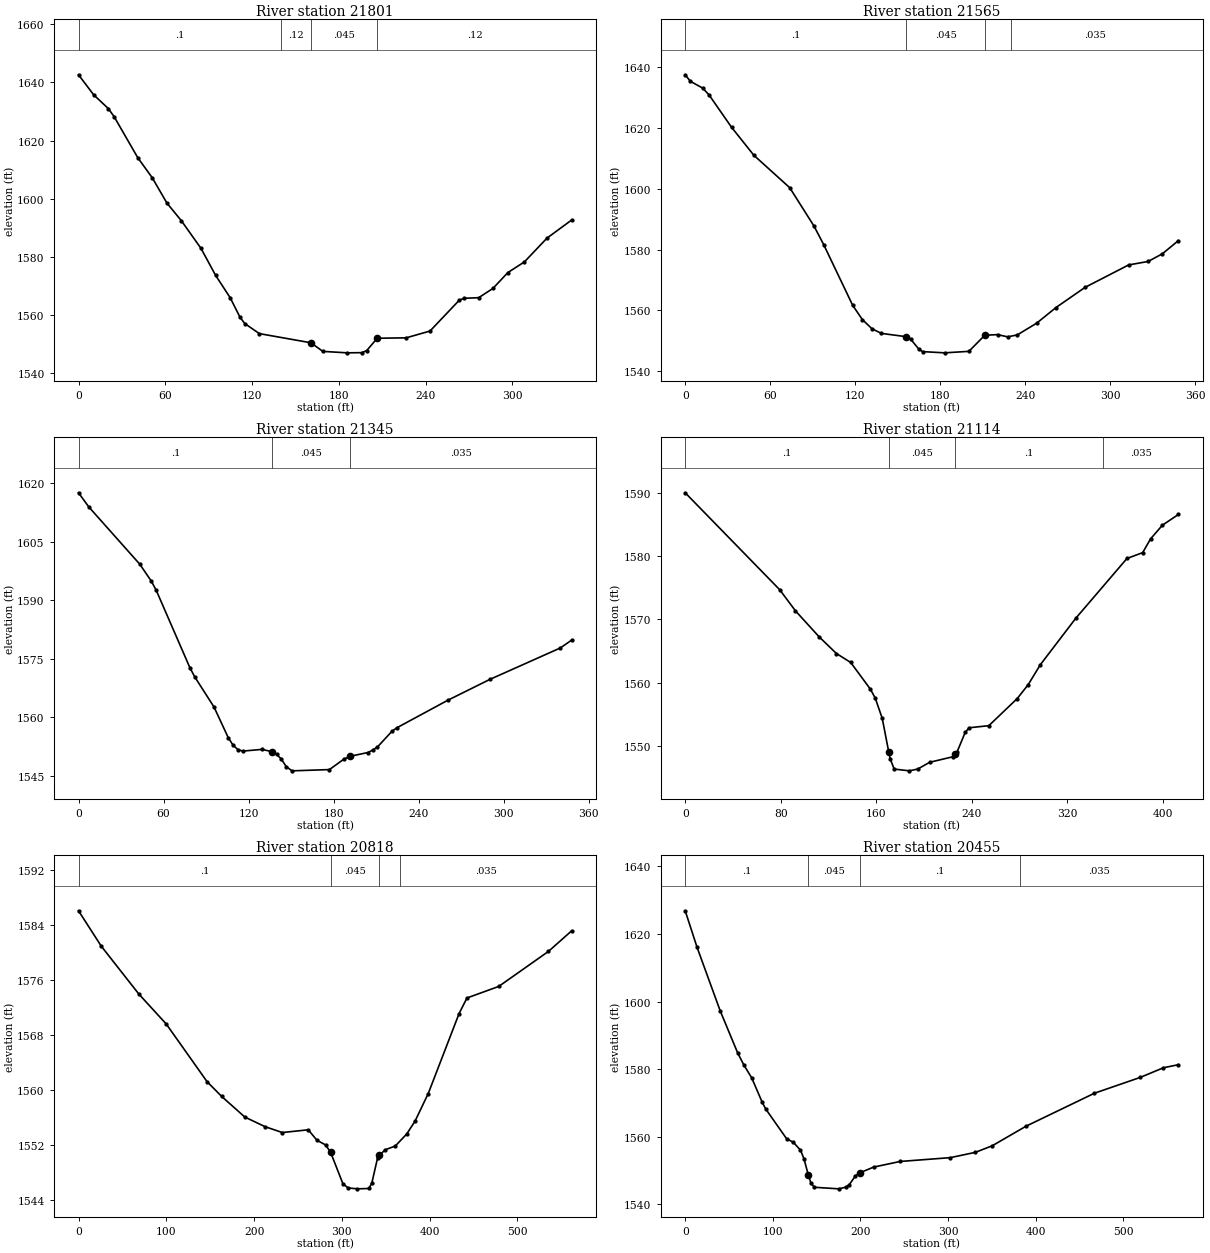
Type RM Length L Ch R = 1 ,21801   ,234.9,235.8,237.6
XS GIS Cut Line= 2
     2072535.851      244553.135     2072457.726      244885.166
#Sta/Elev= 30
       0 1642.63    10.5 1635.73    20.7 1630.97    24.7 1628.16      41 1614.09
      51  1607.2    61.1 1598.52    71.2 1592.38    84.7 1582.91    94.8 1573.64
   104.9 1565.92   111.7 1559.21     115 1557.04   125.1 1553.57   160.71550.429
     169 1547.46   185.8 1546.96   195.9 1547.02   199.3 1547.72   206.61551.982
   226.6 1552.12   243.1 1554.46   263.3 1565.04   266.7 1565.73   276.8 1565.94
   286.6 1569.11     297 1574.59   308.4 1578.25     324 1586.42   341.1 1592.67
#Mann= 4 ,-1 , 0
       0      .1       0     140     .12       0   160.7    .045       0
   206.6     .12       0
Bank Sta=160.7,206.6
XS Rating Curve= 0 ,0
Exp/Cntr=0.3,0.1

Type RM Length L Ch R = 1 ,21565   ,220.8,220.1,219
XS GIS Cut Line= 2
     2072325.348       244472.84     2072227.692      244807.041
#Sta/Elev= 30
       0 1637.46     3.6 1635.33    12.3 1633.09    16.8 1630.87    32.8 1620.15
    48.5 1610.98    73.8 1600.33    90.9 1587.74    97.8 1581.59   118.3  1561.6
   125.1 1556.95   131.9 1553.93   138.5 1552.42   156.2 1551.32   159.3 1550.46
   164.9 1547.27   167.6 1546.42   183.2 1546.02   200.3 1546.51   211.5  1551.8
   220.5 1552.01   227.7 1551.28   234.5 1551.92   248.2 1555.79   261.8 1560.92
   282.3 1567.54   313.1 1574.93   326.8 1576.06   336.9 1578.59   348.2 1582.92
#Mann= 4 ,-1 , 0
       0      .1       0   156.2    .045       0   211.5      .1       0
     230    .035       0
Bank Sta=156.2,211.5
XS Rating Curve= 0 ,0
Exp/Cntr=0.3,0.1

Type RM Length L Ch R = 1 ,21345   ,238.4,231,209.3
XS GIS Cut Line= 2
     2072106.164      244425.097     2072017.188      244761.468
#Sta/Elev= 30
       0 1617.59     7.3 1613.94    43.2 1599.26    51.3 1594.94    54.8 1592.57
    78.6 1572.65      82 1570.32    95.6 1562.58   105.7 1554.66   109.1 1552.75
   112.5 1551.64   115.9 1551.27   129.5 1551.71   136.61551.101   139.7 1550.46
   143.1  1549.2   146.5  1547.3   150.6  1546.2     177 1546.52   187.2  1549.2
   191.81549.952   204.1  1550.9   207.5 1551.51   210.9 1552.33   221.1 1556.35
   224.5 1557.24   260.6 1564.34   290.1 1569.66   339.9 1577.75   347.9 1579.77
#Mann= 3 ,-1 , 0
       0      .1       0   136.6    .045       0   191.8    .035       0
Bank Sta=136.6,191.8
XS Rating Curve= 0 ,0
Exp/Cntr=0.3,0.1

Type RM Length L Ch R = 1 ,21114   ,289.9,295.6,303.1
XS GIS Cut Line= 2
     2071824.046      244346.972     2071873.959      244757.128
#Sta/Elev= 30
       0    1590    79.2 1574.67    92.4 1571.33   112.3 1567.21   126.7 1564.59
   138.7 1563.17   155.2 1558.94   159.2 1557.55   165.1 1554.33   170.51549.068
   171.8 1547.91   175.1 1546.32   187.8 1546.04   194.9 1546.33   204.8 1547.39
   224.6 1548.28   226.31548.693   227.9 1549.08   234.6 1552.12   237.9 1552.85
   254.4 1553.18   278.2 1557.47   287.4 1559.67   297.6 1562.83   327.2 1570.15
   370.1 1579.61   383.3 1580.54   389.9 1582.71   399.8 1584.87   413.2 1586.57
#Mann= 4 ,-1 , 0
       0      .1       0   170.5    .045       0   226.3      .1       0
     350    .035       0
Bank Sta=170.5,226.3
XS Rating Curve= 0 ,0
Exp/Cntr=0.3,0.1

Type RM Length L Ch R = 1 ,20818   ,380.4,363.4,329.2
XS GIS Cut Line= 3
      2071644.75      244256.078     2071565.799      244379.524
     2071539.757       244794.02
#Sta/Elev= 30
       0 1586.07      26  1580.9    68.8 1573.93     100 1569.57   146.5 1561.17
   163.1 1559.03   189.4 1556.03   212.4 1554.63   232.2 1553.77   261.7 1554.17
   271.6 1552.65   281.5 1551.96   287.21550.879   301.2 1546.31   307.2  1545.7
   317.6 1545.57   330.8 1545.62   334.1 1546.39   340.6 1550.03   342.81550.447
   349.3 1551.26   360.8  1551.8   373.9 1553.56   383.4 1555.44   398.4 1559.45
   433.5 1571.09   442.5 1573.37   478.7 1575.05   535.2 1580.14   561.8 1583.15
#Mann= 4 ,-1 , 0
       0      .1       0   287.2    .045       0   342.8      .1       0
  366.53    .035       0
Bank Sta=287.2,342.8
XS Rating Curve= 0 ,0
Exp/Cntr=0.3,0.1

Type RM Length L Ch R = 1 ,20455   ,420.4,407.2,375.3
XS GIS Cut Line= 3
       2071107.9      244386.034     2071307.553      244676.833
     2071487.674       244785.34
#Sta/Elev= 30
       0 1626.89    13.5 1616.11      40 1597.25    59.9 1584.84      67 1581.24
    75.9 1577.47    87.8  1570.3    91.8 1568.29   115.7 1559.47   123.6 1558.35
   131.6 1556.07   135.6 1553.52   140.4 1548.86   143.5 1546.37   147.5 1545.08
   175.4 1544.62   183.3 1545.12   187.3 1545.84   194.4 1548.48   199.2 1549.35
   215.1 1551.05   245.4 1552.72   302.7 1553.85   331.3 1555.42   350.5 1557.36
     389 1563.14   467.2 1572.91   519.3 1577.57   545.9 1580.44     563 1581.35
#Mann= 4 ,-1 , 0
       0      .1       0   140.4    .045       0   199.2      .1       0
  382.74    .035       0
Bank Sta=140.4,199.2
XS Rating Curve= 0 ,0
Exp/Cntr=0.3,0.1

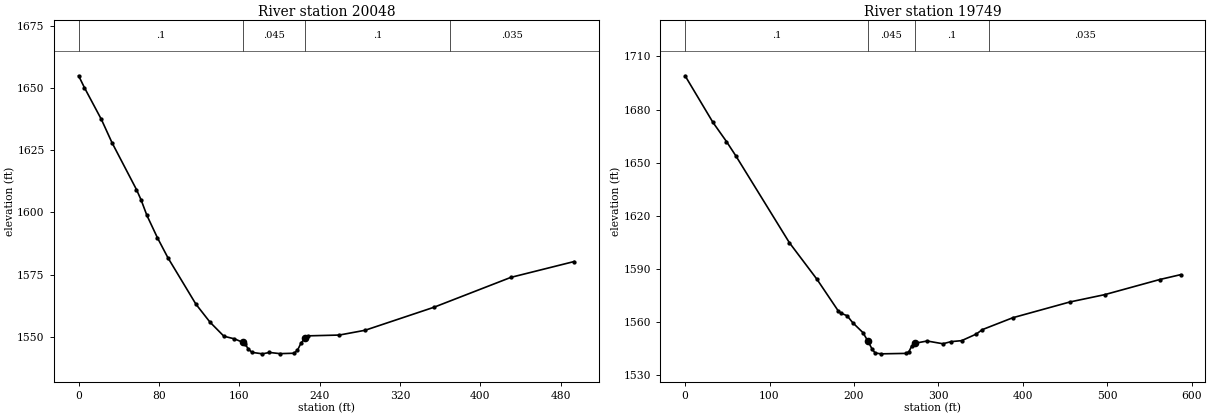
Type RM Length L Ch R = 1 ,20048   ,292,298.5,300.4
XS GIS Cut Line= 2
     2070903.907      244807.041     2071368.317      244974.142
#Sta/Elev= 30
       0 1654.92     5.8 1650.13    22.7 1637.35    33.2 1628.07    57.6  1609.2
    62.2 1605.05      68 1598.81    78.5  1589.8    88.9 1581.81   116.8 1563.14
   130.8 1555.92   144.7 1550.24   155.2 1549.18   163.41547.809   165.6 1547.17
   169.1  1545.1   172.6 1543.76   183.1 1543.16   190.1 1543.72   200.5 1543.24
   214.5  1543.4   217.9 1544.54   221.4 1547.37   225.51549.516   228.4 1550.39
   259.6 1550.71   285.3 1552.63   353.9 1561.88   430.6  1573.9   493.6 1580.26
#Mann= 4 ,-1 , 0
       0      .1       0   163.4    .045       0   225.5      .1       0
     370    .035       0
Bank Sta=163.4,225.5
XS Rating Curve= 0 ,0
Exp/Cntr=0.3,0.1

Type RM Length L Ch R = 1 ,19749   ,370.6,383.5,395.8
XS GIS Cut Line= 2
     2070728.084      245023.439     2071259.334      245273.439
#Sta/Elev= 30
       0 1699.05      33 1672.75      49 1661.97      60 1653.96   123.6 1604.85
   156.3  1584.2   181.7 1566.22   184.6 1565.13     192 1563.66   198.6 1559.75
   210.7 1554.16   216.51549.428   221.6 1544.81   225.2 1542.65   232.4 1542.18
   261.4 1542.43   265.1 1543.35   268.7 1546.72   272.21548.147   286.8 1549.42
   305.4 1547.87   315.3 1549.08   327.6 1549.61   344.9 1553.32   352.1 1555.83
   388.3 1562.56   455.8 1571.43   497.1 1575.57   562.4 1584.11   587.1 1586.85
#Mann= 4 ,-1 , 0
       0      .1       0   216.5    .045       0   272.2      .1       0
     360    .035       0
Bank Sta=216.5,272.2
XS Rating Curve= 0 ,0
Exp/Cntr=0.3,0.1