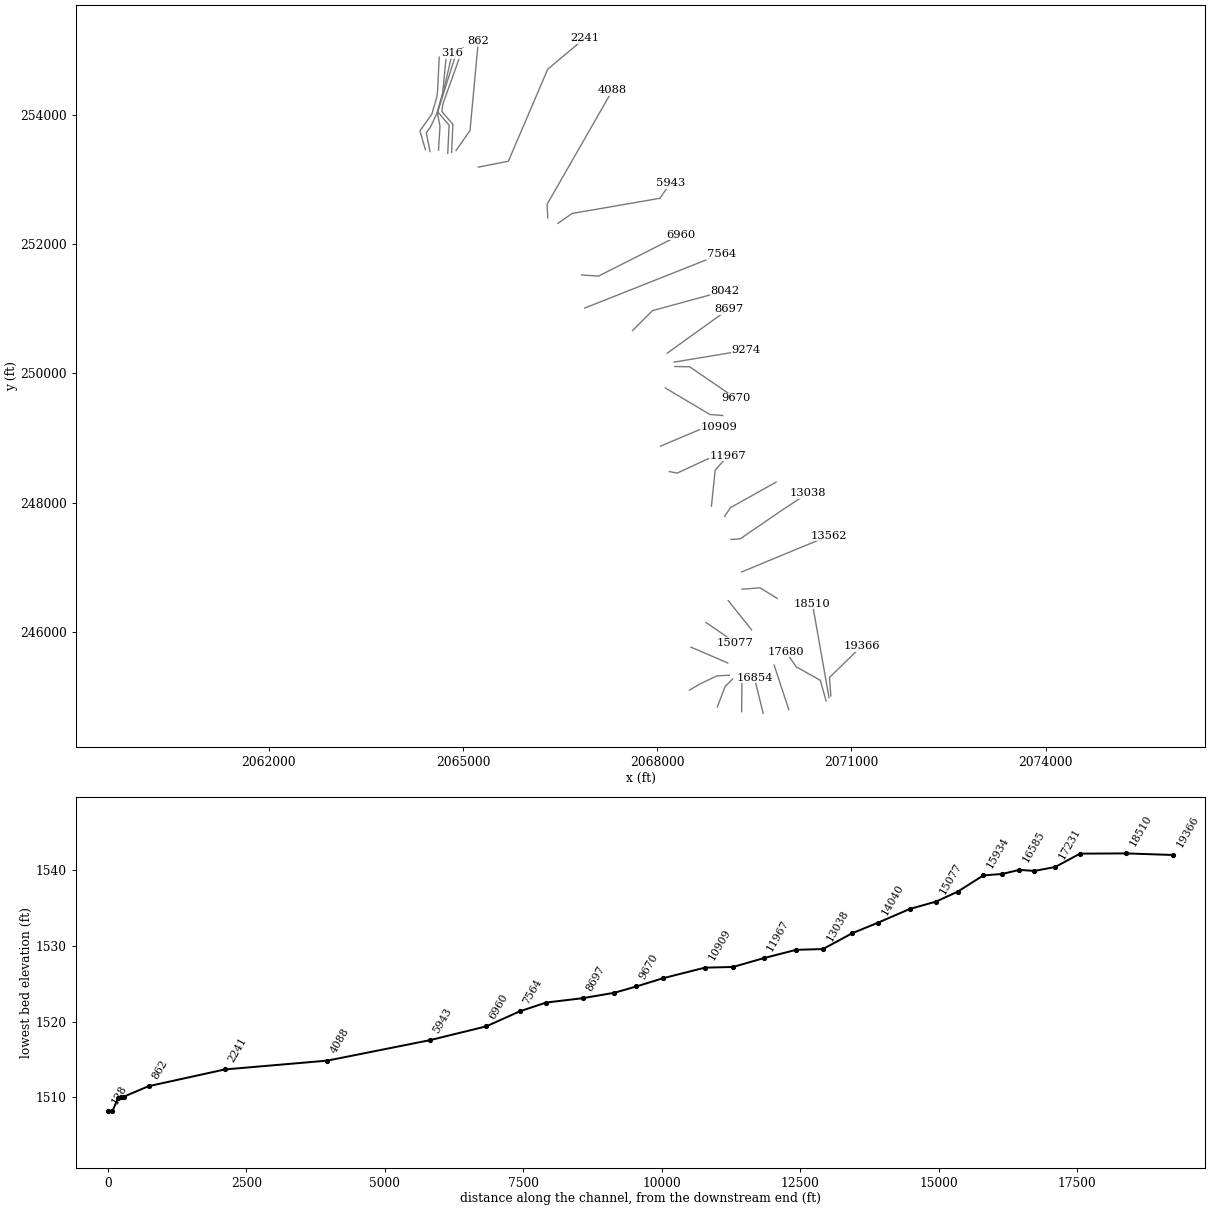
HEC-RAS study WOLFCK.prj: WOLFCK

--- WOLFCK.g01 (geometry) --- (continued)

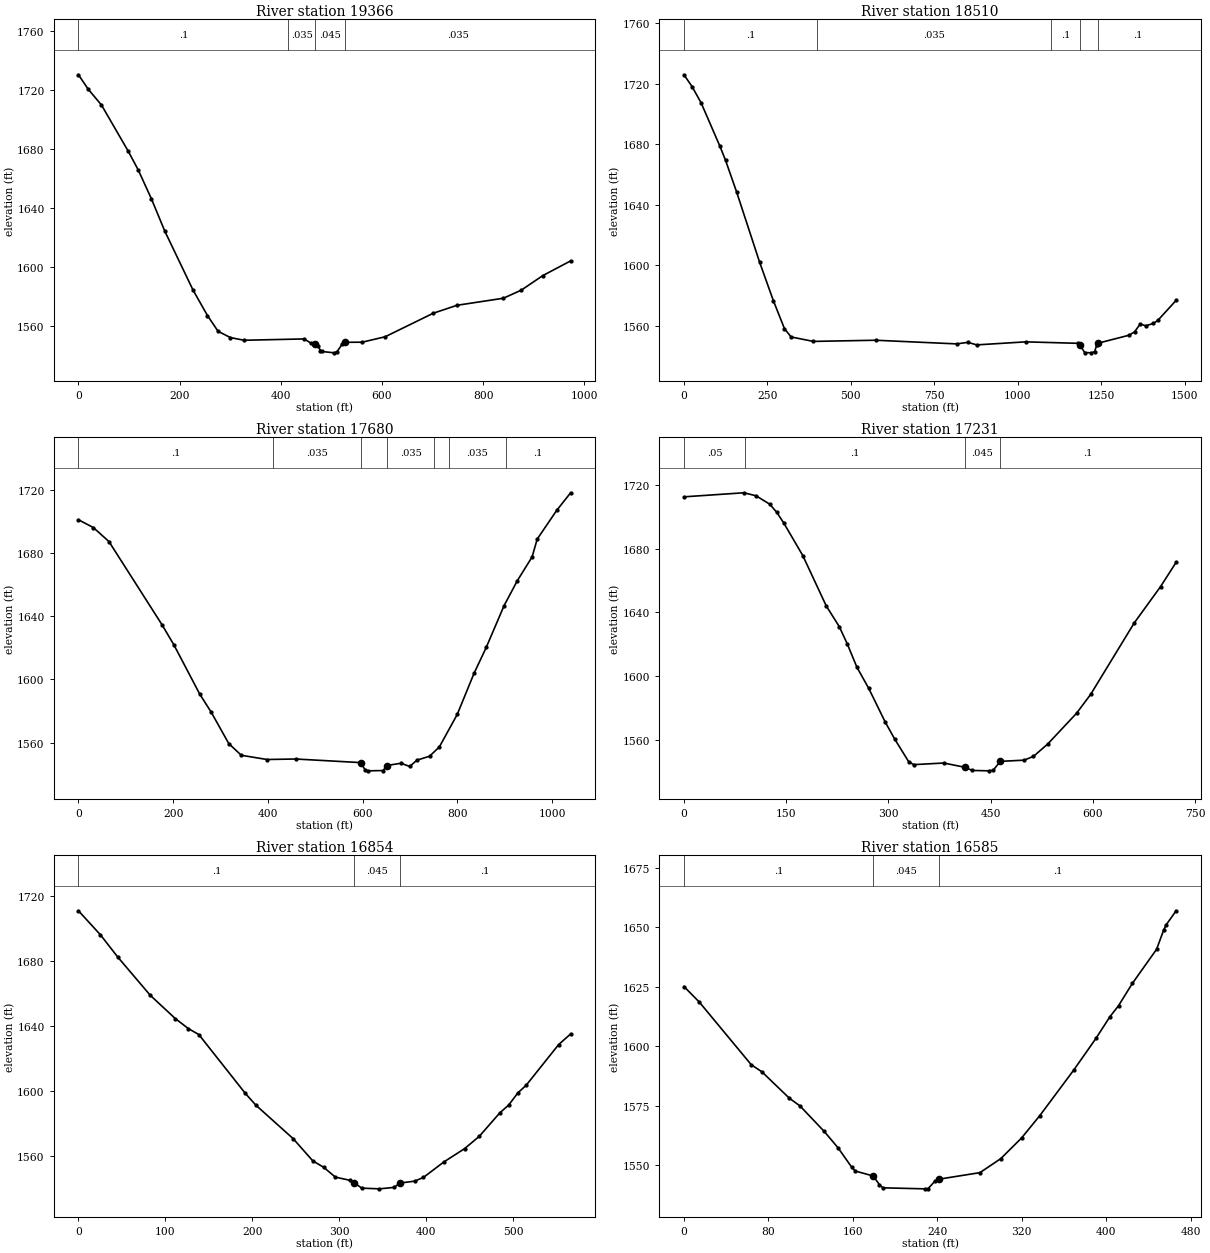
Type RM Length L Ch R = 1 ,19366   ,816.8,856.3,885.2
XS GIS Cut Line= 3
     2070682.945      245016.494     2070661.719      245300.531
     2071155.167      245780.383
#Sta/Elev= 30
       0 1730.14    19.4 1720.32    45.4 1709.73    98.4 1678.43   118.1  1665.8
   144.4 1646.06   170.7 1624.33   226.7 1584.31   255.1  1567.2     276 1556.55
   300.5 1552.29   327.5 1550.47   446.5 1551.38   460.3 1548.35   468.41548.024
     474 1546.48   478.5 1543.46   481.2 1542.89     506 1541.96   511.4 1542.81
   521.6 1547.94   527.41549.098   560.9 1549.16   606.4 1552.84   701.6 1568.78
   748.5 1574.14   840.1 1578.91   875.6 1584.39   917.9 1594.19   973.1 1604.19
#Mann= 4 ,-1 , 0
       0      .1       0  414.83    .035       0   468.4    .045       0
   527.4    .035       0
Bank Sta=468.4,527.4
XS Rating Curve= 0 ,0
Exp/Cntr=0.3,0.1

Type RM Length L Ch R = 1 ,18510   ,795.1,829.5,862.3
XS GIS Cut Line= 2
     2070655.167      244988.717     2070398.698      246441.156
#Sta/Elev= 30
       0 1725.99    24.5 1718.07    51.2 1707.49     108 1678.58   124.5 1669.47
   157.8 1648.47   226.6 1602.11   267.7 1576.76   301.1 1558.15     321 1552.67
   387.7 1549.73   574.2  1550.5   817.5 1548.08   850.8 1549.11   877.4 1547.43
    1024 1549.43  1180.6 1548.47  1186.51547.429  1200.6 1542.39  1220.6 1542.17
  1230.6 1542.94  1237.2 1547.46  1242.21548.626  1333.9 1553.82  1350.5 1556.08
  1367.2 1561.21  1383.8 1560.08  1406.8 1561.59  1420.5 1563.73  1474.9 1576.87
#Mann= 5 ,-1 , 0
       0      .1       0     400    .035       0    1100      .1       0
  1186.5    .045       0  1242.2      .1       0
Bank Sta=1186.5,1242.2
XS Rating Curve= 0 ,0
Exp/Cntr=0.3,0.1

Type RM Length L Ch R = 1 ,17680   ,475.5,448.8,420
XS GIS Cut Line= 4
     2070610.028      244936.633     2070521.094       245256.26
     2070146.094      245467.198     2069989.844      245696.364
#Sta/Elev= 30
       0 1701.04    31.5 1696.08    64.4 1687.25   176.3 1634.67   201.7 1621.79
   256.2 1590.66   280.2 1579.33   317.5 1559.37   343.9 1551.99   398.3 1549.31
   458.6 1549.63   595.81547.356   605.8 1542.57   611.6 1542.14   643.5 1542.32
   651.21545.507   681.1 1546.94   699.5 1544.91     715 1548.92   741.4 1551.37
   762.2 1557.28   799.9 1577.82   835.3 1603.75   861.3 1620.32   898.9 1646.71
   926.9 1662.49   958.1 1677.53   968.8 1688.78    1010 1706.96  1039.4 1718.11
#Mann= 7 ,-1 , 0
       0      .1       0  411.77    .035       0   595.8    .045       0
   651.2    .035       0  751.77      .1       0  782.02    .035       0
  902.02      .1       0
Bank Sta=595.8,651.2
XS Rating Curve= 0 ,0
Exp/Cntr=0.3,0.1

Type RM Length L Ch R = 1 ,17231   ,379.5,377.1,374.6
XS GIS Cut Line= 2
     2070033.639      244804.689     2069807.553      245490.635
#Sta/Elev= 30
       0 1712.56    87.9 1715.11   105.7 1713.23   125.9 1707.92   136.3 1702.74
   146.7 1695.91   174.3 1675.69   208.8 1643.98   227.9    1631   239.9 1619.87
   253.7 1605.54     271 1592.27   295.4 1570.95     309 1560.49   329.7 1546.14
   336.9 1544.27   381.1 1545.29   411.81542.655     423 1540.63   447.2 1540.38
   453.9 1540.82   464.1 1546.33     499 1547.09   512.8 1549.46   533.6 1557.17
     576 1576.53   596.8 1588.45   660.7 1633.32   699.4 1656.19   722.2 1671.45
#Mann= 4 ,-1 , 0
       0     .05       0      90      .1       0   411.8    .045       0
   464.1      .1       0
Bank Sta=411.8,464.1
XS Rating Curve= 0 ,0
Exp/Cntr=0.3,0.1

Type RM Length L Ch R = 1 ,16854   ,278.6,268.9,257
XS GIS Cut Line= 2
     2069637.806      244745.661     2069502.865      245295.323
#Sta/Elev= 30
       0 1710.63    25.2 1695.91    45.4 1682.07    82.6 1658.71   111.3 1644.46
   126.5 1638.24   138.4 1634.63   191.9 1598.49   204.2 1591.15   246.9 1570.69
   269.5 1557.04   282.2 1553.03   295.4 1547.06   312.3 1545.09   317.31543.526
   325.8 1540.29   346.1 1539.86     363 1540.74   369.7 1543.42   386.6 1544.58
   396.8  1546.9   420.4 1556.44   444.1 1564.56     461 1572.13   484.6 1586.54
   494.7 1591.27   505.3 1598.76     515 1603.55   552.2 1628.44     566 1634.99
#Mann= 3 ,-1 , 0
       0      .1       0   317.3    .045       0   369.7      .1       0
Bank Sta=317.3,369.7
XS Rating Curve= 0 ,0
Exp/Cntr=0.3,0.1

Type RM Length L Ch R = 1 ,16585   ,326.4,313.6,299
XS GIS Cut Line= 2
     2069304.948      244771.885     2069310.157      245238.031
#Sta/Elev= 30
       0 1624.99    14.6 1618.42    63.8  1592.1    73.7 1589.21    99.9 1578.04
   109.8 1574.87   132.7 1564.19   145.9 1557.26     159 1549.02   162.3 1547.48
   179.31545.387   185.2 1541.71   188.5 1540.43   227.9    1540   231.2 1540.08
   237.7 1543.22   241.21544.042   280.4 1546.81   300.1  1552.7   319.8 1561.38
   337.1 1570.79     369 1589.78   390.2 1603.18   403.4 1612.26   411.6 1616.92
   424.7  1626.3   447.7 1640.65   454.3 1648.62   456.5 1650.76   466.2 1656.82
#Mann= 3 ,-1 , 0
       0      .1       0   179.3    .045       0   241.2      .1       0
Bank Sta=179.3,241.2
XS Rating Curve= 0 ,0
Exp/Cntr=0.3,0.1

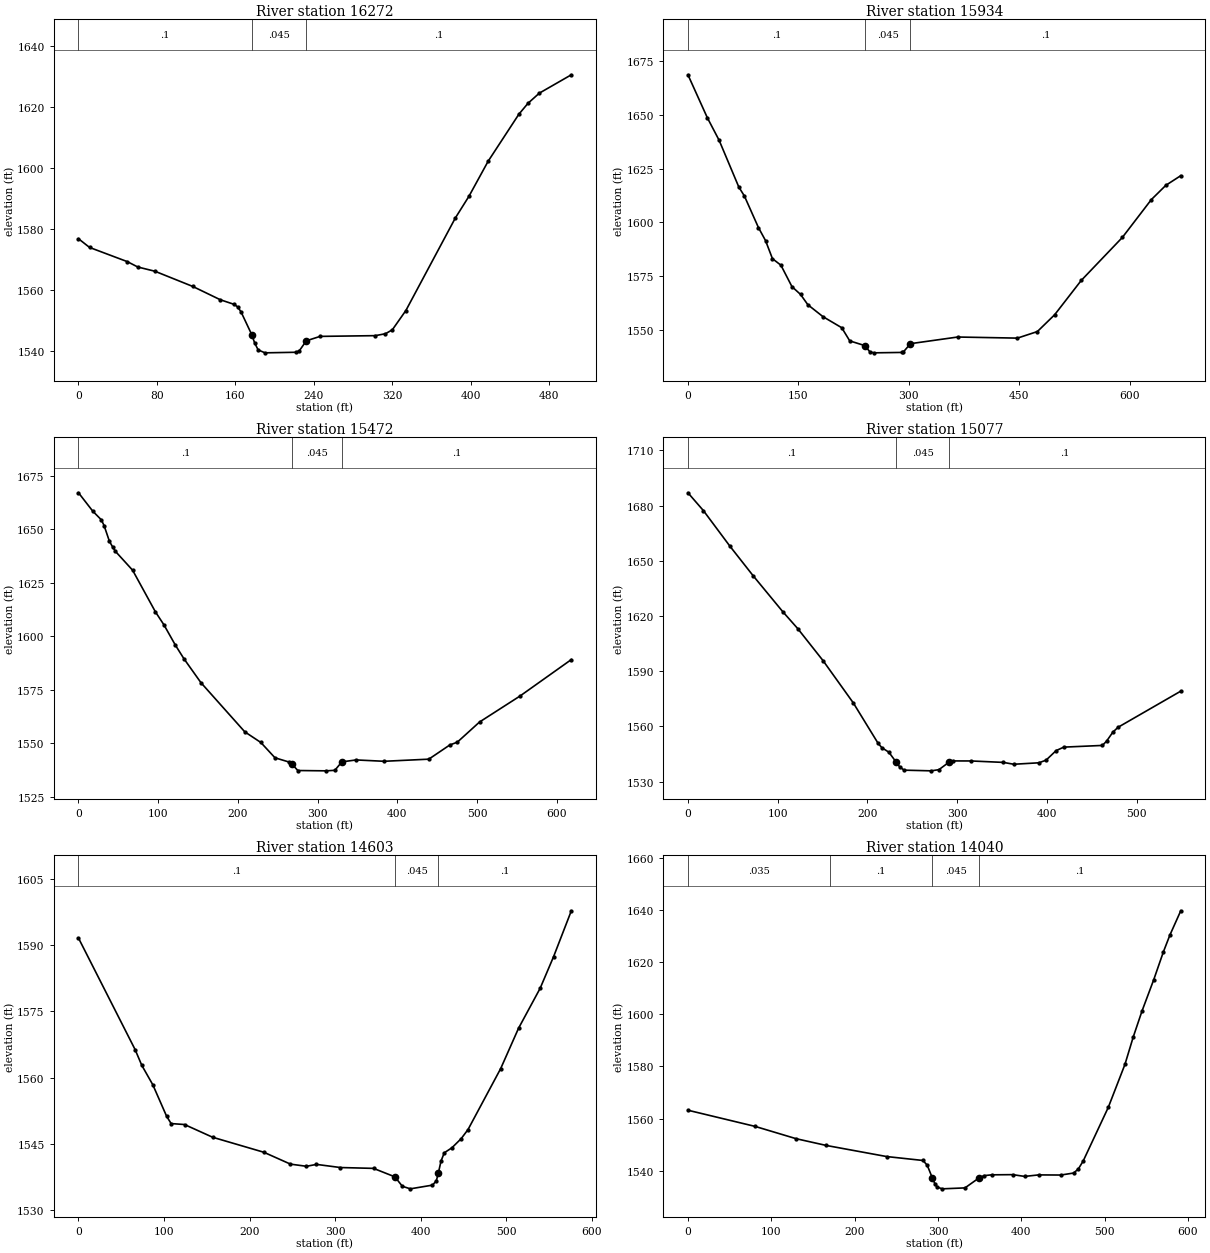
Type RM Length L Ch R = 1 ,16272   ,369.1,338.1,309.3
XS GIS Cut Line= 3
     2068929.948      244844.802      2069049.74      245159.906
     2069166.928      245277.093
#Sta/Elev= 30
       0 1576.84    11.3 1573.99    49.9 1569.33    60.5 1567.58      78 1566.19
   116.6 1561.21   144.7 1556.85   158.8 1555.34   162.3 1554.53   165.8 1552.89
   176.71545.458   179.8 1542.64   183.3 1540.42   190.3 1539.46   222.3 1539.65
   225.4 1540.19   232.4 1543.39   232.4  1543.4   246.5 1544.85   302.7 1545.09
   313.2 1545.72   320.2 1547.02     334 1553.33   384.4 1583.61   398.3 1590.73
   417.9 1602.22   449.3 1617.65   458.6 1621.22   470.1 1624.53   502.8 1630.56
#Mann= 3 ,-1 , 0
       0      .1       0   176.7    .045       0   232.4      .1       0
Bank Sta=176.7,232.4
XS Rating Curve= 0 ,0
Exp/Cntr=0.3,0.1

Type RM Length L Ch R = 1 ,15934   ,493.5,462,431.3
XS GIS Cut Line= 4
     2068500.261      245105.218     2068659.115      245198.968
      2068924.74      245326.573     2069114.844      245334.385
#Sta/Elev= 30
       0 1668.68    26.3 1648.72    42.4 1638.17    69.1 1616.44    76.7 1612.25
    95.8 1597.55   105.4 1591.51   114.8 1583.09   126.3 1580.05   141.3 1570.07
   152.9 1566.47   162.9 1561.65   183.4 1556.11   208.9 1550.96   219.8 1544.83
   240.11542.654   247.2 1539.72   252.6 1539.27   290.2 1539.46   292.6 1539.67
   302.31543.541   366.4 1546.63   447.5 1546.12   474.6 1549.17   498.1    1557
   534.2 1572.96     590 1592.96   629.4 1610.58   649.1 1617.23   669.4 1621.73
#Mann= 3 ,-1 , 0
       0      .1       0   240.1    .045       0   302.3      .1       0
Bank Sta=240.1,302.3
XS Rating Curve= 0 ,0
Exp/Cntr=0.3,0.1

Type RM Length L Ch R = 1 ,15472   ,401.2,394.8,386.1
XS GIS Cut Line= 2
     2068523.698      245769.281     2069091.407      245524.489
#Sta/Elev= 30
       0 1666.95    17.9 1658.37    28.6 1654.34    32.1 1651.65    38.8 1644.29
    42.9 1641.61    46.4 1639.57    67.9 1630.79    96.5 1611.35   107.2 1605.28
   121.5 1595.83   132.2  1589.5   153.6 1578.29   208.6 1555.34   228.7 1550.38
   246.5 1543.21   264.4 1541.21   268.21540.116   275.1 1537.28   310.6 1537.13
   321.5 1537.37   330.41541.327   348.3 1542.22   383.3 1541.59   439.4 1542.58
   465.7 1549.19   475.2 1550.52   503.1 1559.94   553.8 1572.05   618.2 1589.08
#Mann= 3 ,-1 , 0
       0      .1       0   268.2    .045       0   330.4      .1       0
Bank Sta=268.2,330.4
XS Rating Curve= 0 ,0
Exp/Cntr=0.3,0.1

Type RM Length L Ch R = 1 ,15077   ,482.3,474.3,450.1
XS GIS Cut Line= 2
     2068755.469      246149.489     2069208.594      245839.593
#Sta/Elev= 30
       0 1686.97    17.3 1677.24    46.7 1657.98    72.7 1641.83   105.7  1622.3
   122.3 1613.14   150.6 1595.66   184.2 1572.75   211.9 1550.72     216 1548.41
   223.8 1545.95     2321540.543   235.9 1537.94   240.8 1536.18     271 1535.81
   279.6 1536.45   290.81540.513   295.5  1541.2   315.4 1541.18   351.3  1540.4
     363 1539.39   390.9 1540.18   398.9  1541.6   410.2 1546.83   418.7  1548.7
   461.7 1549.62   466.4 1551.99   473.3  1556.8   479.1 1559.48     549 1579.13
#Mann= 3 ,-1 , 0
       0      .1       0     232    .045       0   290.8      .1       0
Bank Sta=232,290.8
XS Rating Curve= 0 ,0
Exp/Cntr=0.3,0.1

Type RM Length L Ch R = 1 ,14603   ,551.2,562.5,575.7
XS GIS Cut Line= 2
     2069099.219      246488.031     2069458.594       246037.51
#Sta/Elev= 30
       0 1591.58    66.2 1566.35      74 1562.79    86.9 1558.39     103 1551.28
   108.3 1549.61     124 1549.39   156.9 1546.51   216.7 1543.12   247.9 1540.43
   266.6 1539.94   278.3 1540.37   306.3 1539.66     345 1539.47     3701537.551
   378.7 1535.42     388 1534.84   413.9 1535.68   418.4 1536.64   420.7 1538.33
   423.9 1541.11   427.7 1542.99   436.7 1544.14   447.5  1546.2   455.5 1548.26
   493.7 1562.06   514.6 1571.19   539.8 1580.21   555.5 1587.36   576.3 1597.76
#Mann= 3 ,-1 , 0
       0      .1       0     370    .045       0   420.7      .1       0
Bank Sta=370,420.7
XS Rating Curve= 0 ,0
Exp/Cntr=0.3,0.1

Type RM Length L Ch R = 1 ,14040   ,444.7,478.5,518.6
XS GIS Cut Line= 3
     2069312.761      246665.114     2069588.803      246685.948
     2069857.032      246521.885
#Sta/Elev= 30
       0 1563.19    80.6 1556.99   129.9 1552.27   166.1 1549.68   238.5 1545.43
     282 1543.93   287.1 1542.11   293.21537.268   296.6 1534.79     299 1533.74
   305.1 1533.06   332.4 1533.42   348.91537.169   355.1 1538.11   364.6 1538.43
   389.7  1538.5     404 1537.82   420.7  1538.4   447.4 1538.35   462.8 1539.12
   468.5 1540.72   474.3 1543.79   504.3 1564.26   524.3 1580.74   534.3 1591.29
   544.8 1601.22   558.9 1613.25   570.5 1623.93   578.3 1630.36   591.3 1639.63
#Mann= 4 ,-1 , 0
       0    .035       0     170      .1       0   293.2    .045       0
   348.9      .1       0
Bank Sta=293.2,348.9
XS Rating Curve= 0 ,0
Exp/Cntr=0.3,0.1

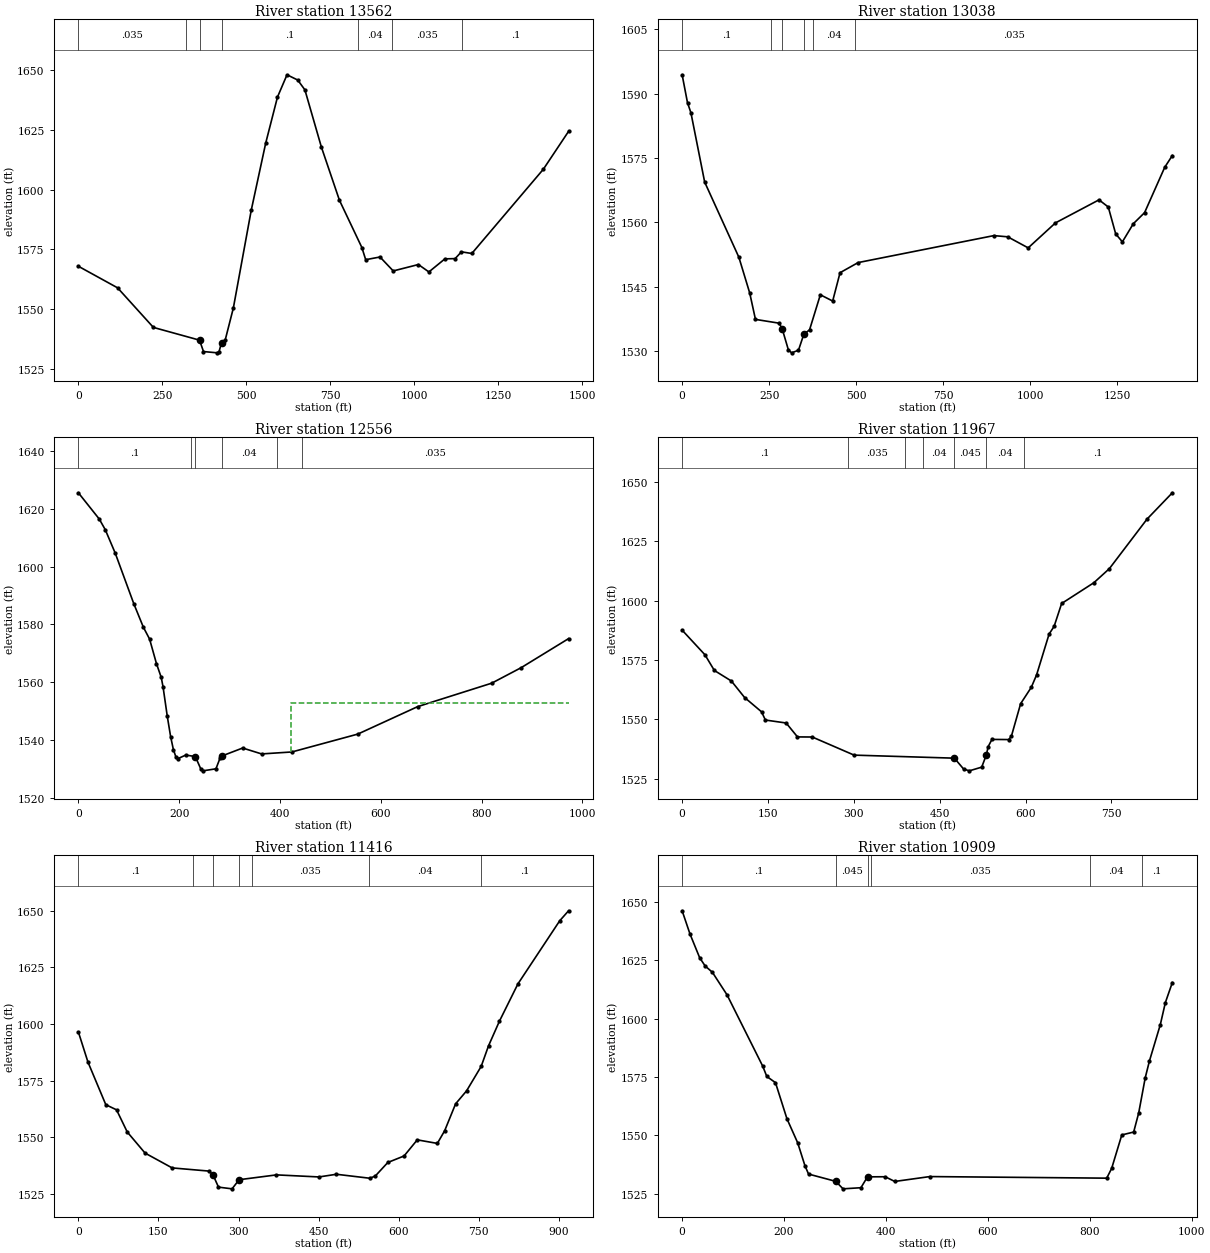
Type RM Length L Ch R = 1 ,13562   ,513.9,523.3,531.2
XS GIS Cut Line= 3
     2069304.948      246930.739      2069862.24       247162.51
2070653.49926671 247489.46087684
#Sta/Elev= 30
       0  1567.9   116.8 1558.86   223.4 1542.28   360.81536.945   372.6 1532.17
   413.8 1531.63   418.8 1532.06   426.41535.948   437.4 1537.08   461.5  1550.4
   514.8 1591.38   557.9 1619.51   592.9 1638.77   621.3 1648.11   653.3  1645.9
   674.6 1641.78   723.6 1617.86   777.5 1595.52   844.2 1575.75   855.6 1570.65
   898.2 1571.78   937.6 1565.94  1012.5 1568.62  1043.8 1565.52  1091.5    1571
  1121.9  1571.1  1140.6 1573.94  1171.6 1573.25  1384.6 1608.54  1459.7  1624.4
#Mann= 7 ,-1 , 0
       0    .035       0     320      .1       0   360.8    .045       0
   426.4      .1       0  833.57     .04       0  933.57    .035       0
 1143.57      .1       0
Bank Sta=360.8,426.4
XS Rating Curve= 0 ,0
Exp/Cntr=0.3,0.1

Type RM Length L Ch R = 1 ,13038   ,485.5,482,477.3
XS GIS Cut Line= 4
     2069138.282      247433.343     2069284.115       247443.76
     2069935.453      247891.1132070330.13527509248149.551008499
#Sta/Elev= 30
       0 1594.41    15.4 1587.89    25.2 1585.56    64.7 1569.39     163 1551.85
   194.1 1543.52   210.6 1537.36   278.4 1536.48   287.2 1535.22     305  1530.3
   314.4 1529.56   334.2 1530.17   349.51533.887     366 1534.93     397  1543.1
   432.4 1541.64   453.6 1548.25   505.5 1550.61   895.3  1556.9   935.2 1556.62
     994 1554.04  1072.4 1559.87  1197.4 1565.24  1224.1 1563.57  1245.4  1557.3
  1264.6 1555.44    1296 1559.67  1328.4 1562.26  1386.2 1572.83  1408.1 1575.58
#Mann= 6 ,-1 , 0
       0      .1       0   256.2    .035       0   287.2    .045       0
   349.5      .1       0   376.2     .04       0   496.2    .035       0
Bank Sta=287.2,349.5
XS Rating Curve= 0 ,0
Exp/Cntr=0.3,0.1

Type RM Length L Ch R = 1 ,12556   ,554.8,589.1,625
XS GIS Cut Line= 3
     2069041.928      247790.114     2069133.073      247925.531
     2069839.099        248320.8
#Sta/Elev= 30
       0 1625.49    41.5 1616.41    53.4 1612.73    73.1 1604.66     110 1587.16
   128.9 1579.08   141.3 1574.96   154.9  1566.5   164.4 1561.73     168 1558.46
   176.4 1548.28     183 1541.29   188.5  1536.8   193.3 1534.36     198 1533.72
   213.1 1534.91     2321534.398   243.2 1529.99   246.9 1529.46   272.9 1530.16
   280.8 1533.74   284.4 1534.57   325.9 1537.34   363.5  1535.3   423.6 1535.98
   554.3 1542.15     673 1551.63     820 1559.74   878.6 1565.11   972.4 1575.12
#Mann= 6 ,-1 , 0
       0      .1       0  223.23     .04       0     232    .045       0
   284.4     .04       0  393.23     .06       0  443.23    .035       0
#XS Ineff= 2 , 0
                          422.03         1552.96
Permanent Ineff=
       F       F
Bank Sta=232,284.4
XS Rating Curve= 0 ,0
Exp/Cntr=0.3,0.1

Type RM Length L Ch R = 1 ,11967   ,578.7,551.1,507.4
XS GIS Cut Line= 3
     2068838.803      247948.968     2068896.094      248503.656
     2069094.308       248727.05
#Sta/Elev= 30
       0 1587.62    39.8 1577.26    56.3 1570.64      86  1566.2   109.1 1559.25
   138.8  1553.2   145.4 1549.76   181.7 1548.51   201.5 1542.65   227.3 1542.61
   300.4 1534.98   475.61533.697   491.7 1529.12   501.6 1528.36   523.3 1529.92
   531.41535.067   534.6 1538.56   541.2  1541.6   570.4 1541.53   575.1 1542.91
   591.3 1556.65   609.9 1563.53   619.1 1568.73     641 1585.97   649.8 1589.23
   662.9 1598.85   719.2  1607.6   746.3 1613.53   812.1  1634.4   856.3 1645.49
#Mann= 7 ,-1 , 0
       0      .1       0     290    .035       0     390      .1       0
     420     .04       0   475.6    .045       0   531.4     .04       0
  597.64      .1       0
Bank Sta=475.6,531.4
XS Rating Curve= 0 ,0
Exp/Cntr=0.3,0.1

Type RM Length L Ch R = 1 ,11416   ,503.8,507.6,507.1
XS GIS Cut Line= 4
     2068187.761      248482.823     2068310.157      248459.385
     2068763.282      248670.323     2069044.828      248753.092
#Sta/Elev= 30
       0 1596.45      18 1583.12    51.4 1564.34    71.5 1562.07    91.5  1552.3
   124.9 1542.98   175.6 1536.44   244.3 1535.04     252 1533.42   262.4 1527.95
   287.8  1527.2     3011531.226     371 1533.36   450.6 1532.45   483.2 1533.63
   545.9 1531.87   556.1 1532.88   579.4 1538.83   609.9 1541.71   634.6 1548.82
   672.2 1547.25   685.9 1552.85   706.4 1564.73   726.9 1570.44   754.3 1581.26
     768 1590.31   788.5 1601.23   823.1 1617.67   901.3 1645.51   917.9 1649.93
#Mann= 7 ,-1 , 0
       0      .1       0  214.62    .035       0     252    .045       0
     301      .1       0  324.62    .035       0  544.62     .04       0
  754.44      .1       0
Bank Sta=252,301
XS Rating Curve= 0 ,0
Exp/Cntr=0.3,0.1

Type RM Length L Ch R = 1 ,10909   ,792.7,759.8,722.8
XS GIS Cut Line= 3
     2068052.344      248876.052     2068791.928      249188.552
     2068950.782      249178.135
#Sta/Elev= 30
       0 1646.13    15.4  1636.2    34.4 1626.03    45.1 1622.52    59.4 1619.79
    88.1 1610.15   158.2  1579.6   166.2  1575.2   183.2 1572.56   205.7 1557.11
   226.8  1546.8     241 1537.03   248.1 1533.43   301.51530.316   315.8 1527.11
   350.9 1527.59   363.81532.252   398.5 1532.28   417.3 1530.27   486.1 1532.36
   833.3 1531.68     843 1535.85   862.9 1550.18   886.2 1551.42   896.1 1559.62
   908.9 1574.65   917.2 1581.89   938.5 1597.39   948.4 1606.83   962.1 1615.42
#Mann= 6 ,-1 , 0
       0      .1       0   301.5    .045       0   363.8      .1       0
     370    .035       0     800     .04       0   902.9      .1       0
Bank Sta=301.5,363.8
XS Rating Curve= 0 ,0
Exp/Cntr=0.3,0.1

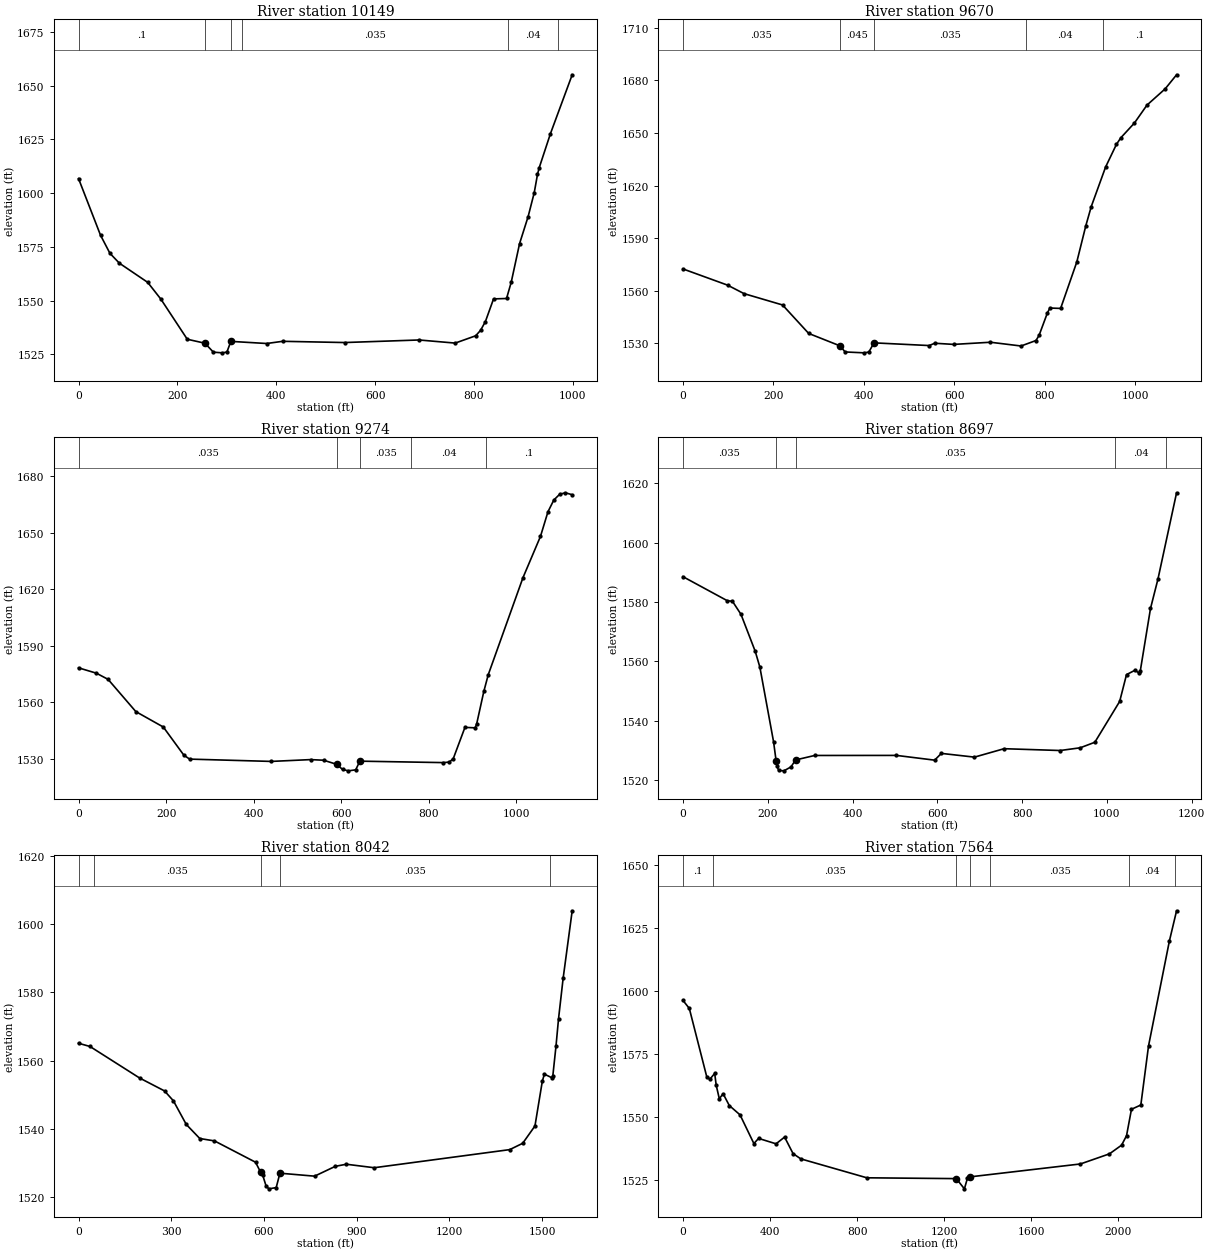
Type RM Length L Ch R = 1 ,10149   ,479.7,478.3,475.5
XS GIS Cut Line= 3
     2068127.865      249774.489     2068815.365      249365.635
     2069013.578      249349.446
#Sta/Elev= 30
       0 1606.74    44.5 1580.39    63.5    1572    82.6  1567.4   139.9 1558.49
   166.6 1550.68     220 1532.03   255.71530.188   272.9 1526.01     291 1525.71
   300.2 1526.07   308.21531.041   380.6 1530.05     413 1531.07   538.5  1530.5
     689 1531.69   762.1 1530.24   803.5 1533.64   813.4 1536.17   823.2 1540.24
   839.7 1550.79     866 1550.98   875.4  1558.5   892.4 1576.55   909.7  1589.1
     922 1600.17   928.6 1608.66   931.9 1611.66   954.9  1627.7   998.8 1655.01
#Mann= 6 ,-1 , 0
       0      .1       0   255.7    .045       0   308.2      .1       0
     330    .035       0  869.89     .04       0  969.89      .1       0
Bank Sta=255.7,308.2
XS Rating Curve= 0 ,0
Exp/Cntr=0.3,0.1

Type RM Length L Ch R = 1 ,9670    ,364.5,396.7,415.1
XS GIS Cut Line= 3
     2068273.995      250107.258     2068502.865      250102.614
     2069214.099      249615.071
#Sta/Elev= 30
       0 1572.47    98.8 1563.21   135.1 1558.38   220.2 1551.92     278 1535.69
     347 1528.63   358.6 1525.13   400.5 1524.63   410.9 1525.07   422.41530.321
   544.5 1528.78   556.5  1530.1   598.7 1529.44   679.8 1530.67   747.4 1528.53
   780.4 1531.65   787.2 1534.55   805.4  1547.2   811.1 1550.17   834.9 1549.95
   870.7 1576.46   890.6 1597.09   902.5 1607.93   934.3 1630.55   958.2 1643.44
   967.9 1647.21     998 1655.64  1025.8 1665.86    1066 1675.12  1091.2 1683.14
#Mann= 5 ,-1 , 0
       0    .035       0     347    .045       0   422.4    .035       0
  758.92     .04       0  928.92      .1       0
Bank Sta=347,422.4
XS Rating Curve= 0 ,0
Exp/Cntr=0.3,0.1

Type RM Length L Ch R = 1 ,9274    ,548.7,576.5,585.8
XS GIS Cut Line= 2
     2068263.578      250174.967     2069375.558      250359.863
#Sta/Elev= 30
       0 1578.35    40.8 1575.51    67.5 1572.24   130.8 1555.18   193.6    1547
   240.4 1532.12   253.7 1530.01     440 1528.79   529.8 1529.75   559.7 1529.42
   589.81527.226   602.9 1524.51   616.2  1523.8   632.9 1524.33   642.31528.927
   832.5 1528.16   846.6 1528.43   855.7 1530.29   882.3 1546.81   905.6 1546.58
   908.9 1548.45   925.5 1565.93   935.5 1574.68  1014.8 1626.09  1054.8 1647.97
  1071.9 1661.01  1085.2  1667.2  1098.5 1670.25  1111.7 1671.06  1127.2 1670.02
#Mann= 5 ,-1 , 0
       0    .035       0   589.8    .045       0   642.3    .035       0
     760     .04       0     930      .1       0
Bank Sta=589.8,642.3
XS Rating Curve= 0 ,0
Exp/Cntr=0.3,0.1

Type RM Length L Ch R = 1 ,8697    ,663.3,654.9,635.9
XS GIS Cut Line= 2
     2068156.511      250313.552     2069101.823      250993.239
#Sta/Elev= 30
       0 1588.52   104.7 1580.41   116.8 1580.23   136.9 1575.83   170.6 1563.33
   181.5 1558.02   213.8 1532.86   219.71526.548   221.9 1524.63   225.9 1523.21
   238.1 1523.08   254.9 1524.41   265.71526.752   310.8 1528.26   503.7 1528.28
   593.7 1526.68   609.5 1528.96   687.6  1527.7   757.5 1530.54   889.9 1529.93
   937.1 1530.85   971.5 1532.71  1030.1 1546.47  1046.2 1555.51  1066.4 1556.99
  1074.9 1556.11  1078.6 1556.64  1102.8  1577.8  1120.4 1587.72  1164.3 1616.79
#Mann= 5 ,-1 , 0
       0    .035       0   219.7    .045       0   265.7    .035       0
    1020     .04       0    1140      .1       0
Bank Sta=219.7,265.7
XS Rating Curve= 0 ,0
Exp/Cntr=0.3,0.1

Type RM Length L Ch R = 1 ,8042    ,472.3,478.2,481.4
XS GIS Cut Line= 3
     2067620.921       250662.51      2067929.08       250970.67
     2069050.037      251276.529
#Sta/Elev= 30
       0 1565.12    37.1 1564.18   197.5 1554.96   278.3 1551.17     307 1548.28
   348.7 1541.36   392.4 1537.24     440 1536.54   572.9  1530.3   589.6 1527.32
   596.4 1526.42   606.6 1523.46   615.6 1522.51   639.7 1522.87   651.8 1527.09
     764 1526.22   831.1  1529.1   866.8 1529.71   956.9 1528.69  1395.6 1533.99
  1437.5 1535.84  1477.2 1540.91    1501 1553.99  1507.6 1556.08  1531.7 1555.04
  1535.1 1555.63  1545.3 1564.28  1553.4  1572.2  1568.4 1584.13  1597.7  1603.9
#Mann= 5 ,-1 , 0
       0      .1       0      50    .035       0   589.6    .045       0
   651.8    .035       0  1525.8     .04       0
Bank Sta=589.6,651.8
XS Rating Curve= 0 ,0
Exp/Cntr=0.3,0.1

Type RM Length L Ch R = 1 ,7564    ,589.2,604,595
XS GIS Cut Line= 2
2066882.17746254251010.4917771732068990.06095722251846.313406369
#Sta/Elev= 30
       0 1596.15    29.4 1592.93   109.3 1565.87   123.9 1564.84   145.9 1567.17
   152.9 1562.47   167.1  1557.1   184.7 1559.09   212.9 1554.42   262.3 1550.71
   325.9 1539.32   347.5 1541.36   427.8 1539.22     467 1541.89   505.9 1535.33
   541.5 1533.24   844.9 1525.73  1255.71525.404  1292.9 1521.35    1307 1525.61
  1320.31526.117  1825.8 1531.22  1959.3 1535.24  2014.9 1538.68  2037.6 1542.42
  2060.3 1552.92  2103.3 1554.62  2138.7 1578.07  2234.7 1619.78  2267.5 1631.69
#Mann= 7 ,-1 , 0
       0      .1       0     140    .035       0  1255.7    .045       0
  1320.3     .04       0    1410    .035       0    2050     .04       0
    2260      .1       0
Bank Sta=1255.7,1320.3
XS Rating Curve= 0 ,0
Exp/Cntr(USF)=0,0
Exp/Cntr=0.3,0.1

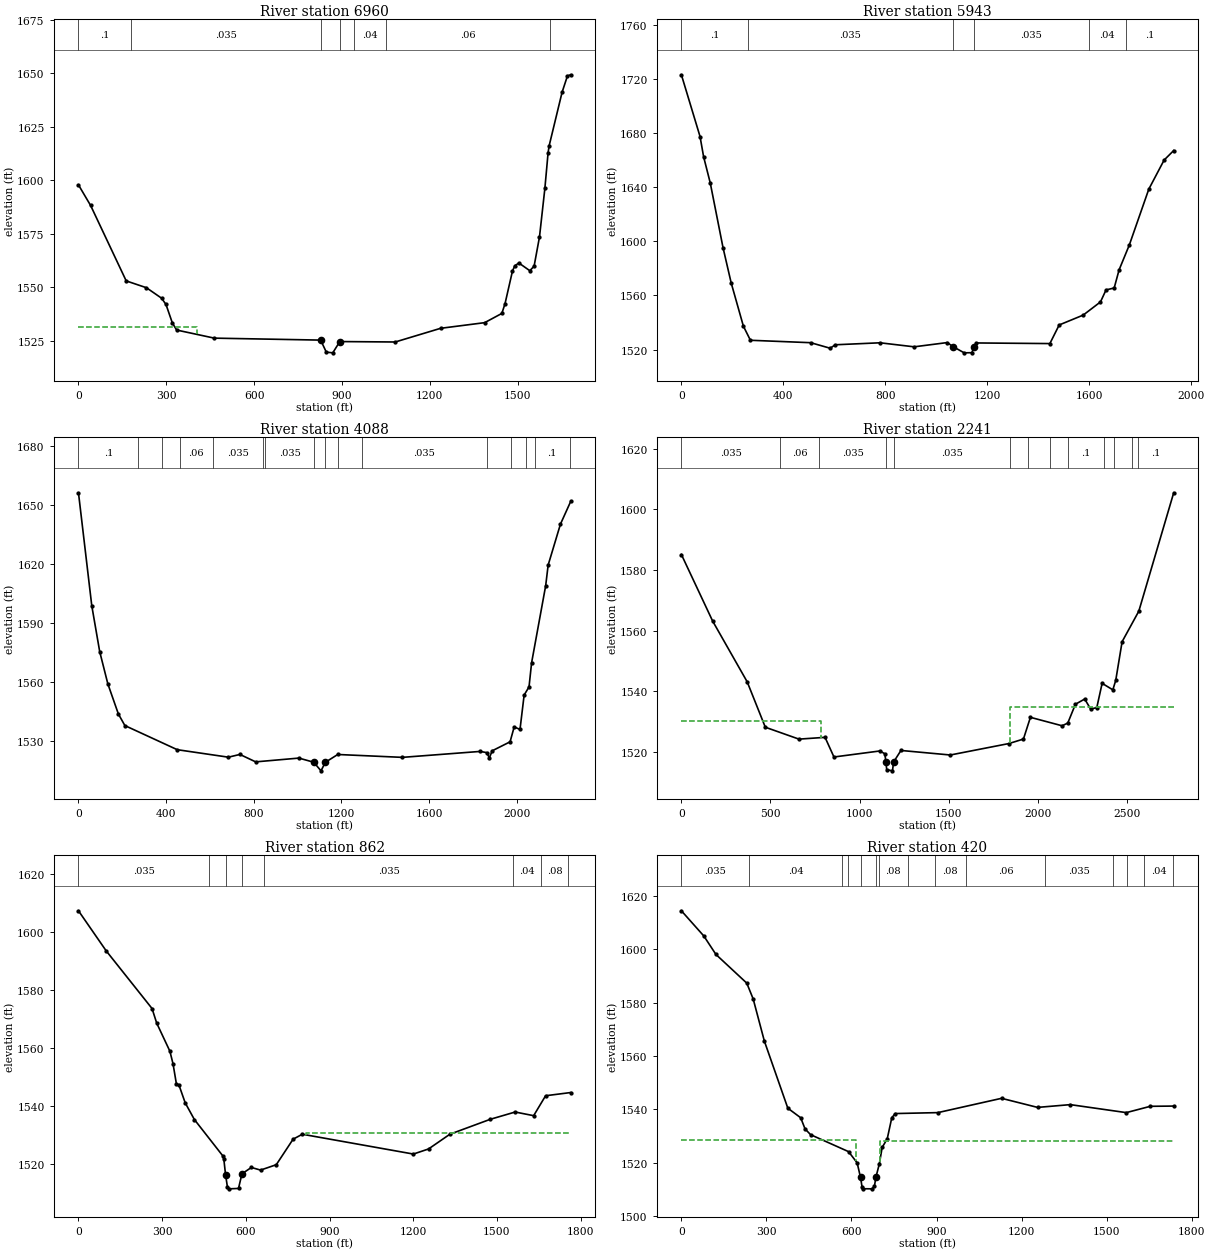
Type RM Length L Ch R = 1 ,6960    ,980.4,1017.4,981
XS GIS Cut Line= 3
      2066835.33      251521.885     2067095.747      251504.524
     2068363.108      252146.885
#Sta/Elev= 30
       0 1597.89    41.5 1588.26   163.1    1553   232.2 1549.81   283.9 1544.92
     299 1541.98   320.7 1533.36   335.4 1530.03   464.2 1526.24   827.41525.323
   846.7  1519.7   868.8 1519.37   892.81524.643  1082.1 1524.44  1237.3 1530.84
  1387.7 1533.48  1446.4  1537.8  1457.3 1542.38  1482.6 1557.57  1490.4 1560.02
  1504.4 1561.39  1541.9 1557.77  1556.6 1559.89    1575 1573.58  1593.4 1596.27
  1604.4 1612.97  1608.1 1616.25  1652.2 1641.21  1670.6 1648.87  1681.9 1649.37
#Mann= 7 ,-1 , 0
       0      .1       0     180    .035       0   827.4    .045       0
   892.8    .035       0     941     .04       0    1051     .06       0
    1611      .1       0
#XS Ineff= 2 , 0
          405.64 1531.35
Permanent Ineff=
       F       F
Bank Sta=827.4,892.8
XS Rating Curve= 0 ,0
Exp/Cntr=0.3,0.1

Type RM Length L Ch R = 1 ,5943    ,1699.7,1854.4,1859.8
XS GIS Cut Line= 4
     2066466.703      252319.064     2066687.761      252472.406
     2068041.928      252706.781     2068207.155      252944.064
#Sta/Elev= 30
       0 1723.14    73.2  1677.5    87.3 1662.47   113.3 1643.17   163.6 1595.19
   195.5 1569.22   243.4 1537.26     271 1526.84   507.7 1525.05     584 1520.95
     604 1523.51   779.7 1524.98   913.6    1522  1043.5 1525.14  1066.4 1522.14
  1110.1 1517.55  1140.2 1517.66 1148.67 1521.94  1156.7 1524.86  1446.4  1524.4
    1483 1538.16  1577.3 1545.46  1645.1  1555.2  1666.9 1564.08  1698.9  1565.5
  1718.1 1578.88  1758.2 1597.24  1834.8 1638.59  1894.9 1660.09  1932.5 1667.13
#Mann= 6 ,-1 , 0
       0      .1       0     260    .035       0  1066.4    .045       0
 1148.67    .035       0 1599.04     .04       0 1743.34      .1       0
Bank Sta=1066.4,1148.67
XS Rating Curve= 0 ,0
Exp/Cntr=0.3,0.1

Type RM Length L Ch R = 1 ,4088    ,1804.4,1847.2,1822.1
XS GIS Cut Line= 3
     2066310.157      252402.961     2066301.476      252615.635
     2067313.058      254380.696
#Sta/Elev= 30
       0 1656.16    60.7 1598.79    96.9 1575.45   134.1 1559.04   182.2 1543.73
   211.8 1537.86   450.8  1525.6   684.3 1521.79   736.9 1523.18   808.9 1519.41
  1006.1 1521.33  1073.8 1519.23  1107.1 1514.85  1126.7 1519.18  1183.5 1523.16
  1478.4  1521.7  1833.9 1524.72  1864.3 1524.09  1875.5  1521.4  1888.3 1525.02
  1970.1  1529.6  1988.9 1537.18  2015.4 1535.88  2034.3 1553.38  2056.6  1557.5
  2068.3 1569.74  2132.6 1608.93  2143.9 1619.42  2200.1 1640.24  2247.2 1651.85
#Mann= 16 ,-1 , 0
       0      .1       0  272.85     .06       0  382.85    .035       0
  462.85     .06       0  612.85    .035       0  842.85     .06       0
  852.85    .035       0  1073.8    .045       0  1126.7    .035       0
 1182.85      .1       0 1292.85    .035       0 1862.85     .04       0
 1972.85     .06       0 2042.85    .035       0 2082.85      .1       0
 2242.85    .035       0
Bank Sta=1073.8,1126.7
XS Rating Curve= 0 ,0
Exp/Cntr=0.3,0.1

Type RM Length L Ch R = 1 ,2241    ,1353.9,1378.8,1379.9
XS GIS Cut Line= 4
     2065238.108      253188.552     2065702.518      253279.698
     2066310.453      254701.876      2066879.03      255179.307
#Sta/Elev= 30
       0 1585.12   175.4 1563.14   369.3 1543.07   470.9 1528.09   659.8 1524.16
   806.1 1524.75     856 1518.26  1113.6 1520.25  1141.4 1519.33 1147.47 1516.75
  1152.1 1514.07  1184.3 1513.69    1191 1516.62    1232 1520.42  1508.9 1518.92
  1838.4 1522.71  1919.3 1524.19  1958.4 1531.36  2136.2 1528.57  2168.1 1529.47
    2211 1535.68    2263  1537.4  2296.7 1534.07  2330.9 1534.59  2360.8 1542.58
  2420.9 1540.44  2437.2 1543.57  2472.9 1556.33  2566.6  1566.4  2762.4  1605.5
#Mann= 13 ,-1 , 0
       0    .035       0  553.27     .06       0  773.27    .035       0
 1147.47    .045       0    1191    .035       0 1843.27     .04       0
 1943.27     .06       0 2069.94     .07       0 2169.94      .1       0
 2369.94     .07       0 2429.94      .1       0 2529.94     .07       0
 2559.94      .1       0
#XS Ineff= 2 , 0
          780.72  1530.1 1845.76         1534.93
Permanent Ineff=
       F       F
Bank Sta=1147.47,1191
XS Rating Curve= 0 ,0
Exp/Cntr=0.3,0.1

Type RM Length L Ch R = 1 ,862     ,400,442.6,466.8
XS GIS Cut Line= 3
     2064893.968      253445.294     2065110.113      253753.453
     2065238.405      255135.904
#Sta/Elev= 30
       0 1607.33    99.4 1593.51   263.7 1573.64   280.6 1568.57   327.8  1558.9
     339 1554.56   351.3 1547.51   359.8 1547.38   382.6 1541.12   415.5 1535.37
   517.6 1522.82   520.9 1521.86   527.5 1516.15   534.1 1512.04   540.7 1511.48
   573.7 1511.62     5861516.659   619.8 1518.85   652.7 1517.94   709.1  1519.8
   769.4  1528.6   802.5  1530.3  1200.5 1523.47  1254.8 1525.22  1331.5 1530.31
  1476.5 1535.46  1565.4 1537.96  1631.7  1536.7  1674.5 1543.57  1764.8 1544.68
#Mann= 8 ,-1 , 0
       0    .035       0   466.4      .1       0   527.5    .045       0
     586      .1       0   666.4    .035       0  1556.4     .04       0
  1656.4     .08       0  1756.4      .1       0
#XS Ineff= 2 , 0
                          814.63         1530.61
Permanent Ineff=
       F       F
Bank Sta=527.5,586
XS Rating Curve= 0 ,0
Exp/Cntr=0.5,0.3

Type RM Length L Ch R = 1 ,420     ,61.5,52.4,59.5
XS GIS Cut Line= 5
     2064825.348       253414.68     2064846.181      253850.444
     2064674.306      254048.361     2064693.403      254171.625
     2065001.426      255031.738
#Sta/Elev= 30
       0 1614.52    79.2 1605.05   121.9 1598.12   230.7 1587.35   253.3  1581.4
   292.7  1565.6   375.5 1540.39   420.8 1536.81   436.3  1532.6   455.8 1530.45
   589.7 1524.08   620.1 1519.86   631.9 1514.39   637.5 1510.76   641.8 1510.15
   672.1 1510.11   680.9 1511.04     686  1514.4   698.4 1519.52   708.3 1525.68
   726.1 1528.86   742.3 1536.85   754.8 1538.38   904.7 1538.73  1129.4  1544.1
  1256.5 1540.69  1371.9 1541.73  1569.5 1538.73  1654.2  1541.1  1736.7 1541.19
#Mann= 15 ,-1 , 0
       0    .035       0     240     .04       0  566.26    .035       0
  586.26     .06       0   631.9    .045       0     686     .06       0
  696.26     .08       0  798.39      .1       0  893.13     .08       0
 1003.13     .06       0 1283.13    .035       0 1523.13     .04       0
 1573.13    .035       0 1633.13     .04       0 1733.13    .035       0
#XS Ineff= 2 , 0
          616.38 1528.55  699.31         1528.14
Permanent Ineff=
       F       F
Bank Sta=631.9,686
XS Rating Curve= 0 ,0
Exp/Cntr=0.5,0.3

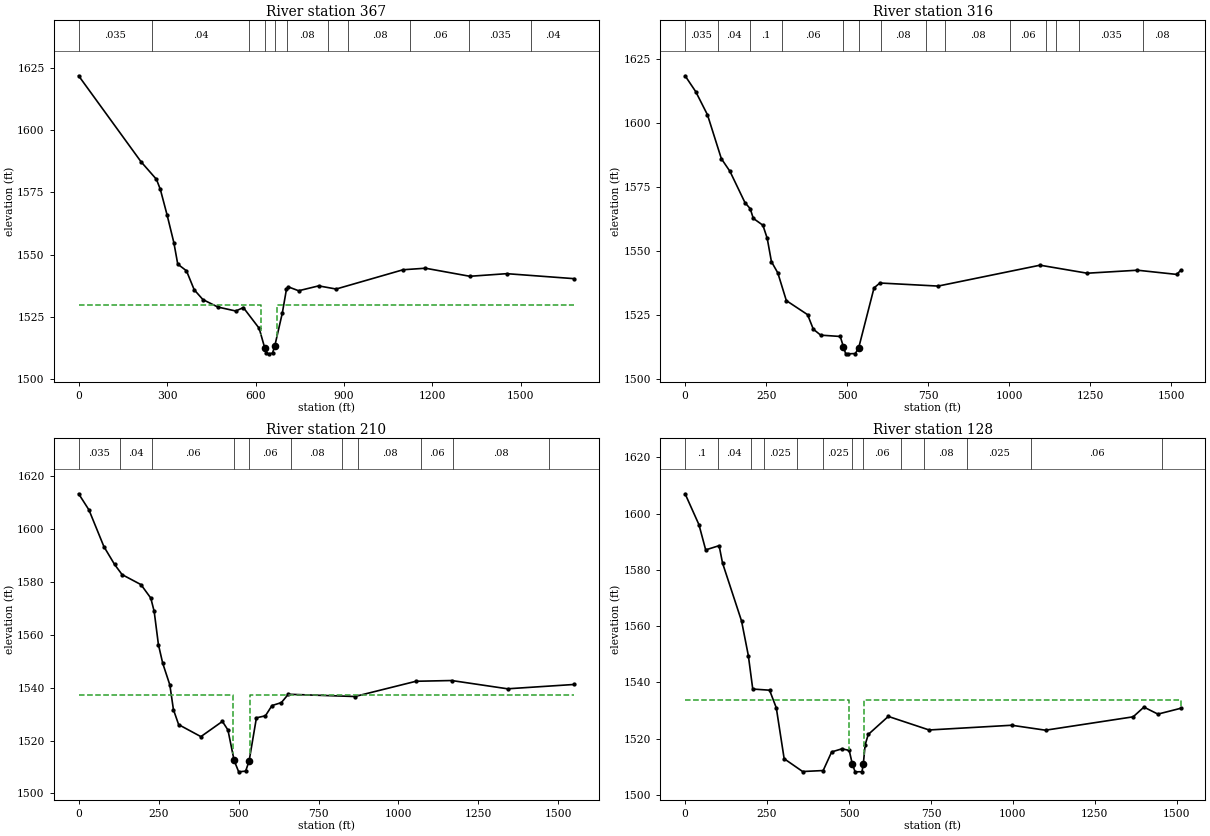
Type RM Length L Ch R = 1 ,367     ,74.7,51.4,28
XS GIS Cut Line= 5
      2064766.32      253400.791     2064787.153      253836.555
     2064612.023      254043.558     2064648.481      254166.127
     2064905.071      254971.842
#Sta/Elev= 30
       0 1621.92   211.9 1587.31   263.9 1580.29   277.1 1576.25   300.1 1565.93
   323.1 1554.78   336.2 1546.17   365.8 1543.49     392 1535.87   421.6 1531.92
   472.3 1528.92   533.1 1527.32   558.7 1528.71   612.3 1520.38     631 1512.59
   636.3 1510.28   644.8  1510.1   657.7 1510.38  665.45 1513.33   690.8 1526.44
     705  1536.1   710.6 1537.06   746.2 1535.47   814.2 1537.43   873.4 1536.16
  1100.7 1543.92  1176.4 1544.53  1326.9 1541.29  1452.3 1542.34  1680.9 1540.33
#Mann= 11 ,-1 , 0
       0    .035       0     250     .04       0  576.26     .06       0
     631    .045       0  665.45     .06       0  706.26     .08       0
  845.29      .1       0  915.29     .08       0 1125.29     .06       0
 1325.29    .035       0 1535.29     .04       0
#XS Ineff= 2 , 0
           619.1 1529.83  672.44         1529.72
Permanent Ineff=
       F       F
Bank Sta=631,665.45
XS Rating Curve= 0 ,0
Exp/Cntr=0.5,0.3

Type RM Length L Ch R = 1 ,316     ,118.8,105.8,69.8
XS GIS Cut Line= 5
     2064623.959      253451.139     2064646.528      253822.666
     2064604.384      254028.974     2064683.551      254288.002
     2064834.759        254945.8
#Sta/Elev= 30
       0 1618.49    32.8  1612.3    69.1 1603.24   111.8 1586.15   138.4 1581.19
   184.8 1568.96   200.8 1566.65   210.4 1562.85     240 1560.17   253.3 1555.07
   266.3 1545.97     286 1541.57   312.3 1530.76   377.8 1525.28   395.5 1519.61
   418.3 1517.28   478.6 1516.77   488.6 1512.64   495.3 1510.06   502.9 1509.99
   525.2 1510.11   535.5 1512.35   582.8 1535.72   600.8 1537.63   780.4 1536.43
  1094.9 1544.58  1240.3 1541.45  1395.4 1542.62  1516.6 1540.98  1528.6 1542.55
#Mann= 14 ,-1 , 0
       0    .035       0     100     .04       0     200      .1       0
     300     .06       0   488.6    .045       0   535.5     .06       0
  602.78     .08       0  742.78      .1       0  802.78     .08       0
 1003.64     .06       0 1113.64     .08       0 1143.64     .06       0
 1213.64    .035       0 1413.64     .08       0
Bank Sta=488.6,535.5
XS Rating Curve= 0 ,0
Exp/Cntr=0.5,0.3

Type RM Length L Ch R = 1 ,210     ,87.7,81.5,90
XS GIS Cut Line= 6
     2064492.014      253429.437     2064434.723      253720.236
     2064495.487      253801.833      2064597.44      254014.391
     2064689.106      254338.696     2064743.613       254914.55
#Sta/Elev= 30
       0 1613.42    32.2 1607.33      79 1593.43   112.4 1586.67   135.9 1582.83
   194.9 1579.04   225.6 1573.95   236.2 1568.91   249.5 1556.32   262.9 1549.28
   285.2 1541.06   296.4 1531.73   312.7 1526.05   382.3 1521.51   449.5 1527.27
   466.8 1524.03  486.09 1512.53   500.4 1508.18   522.3 1508.45   533.2 1512.38
   555.9 1528.63   584.1 1529.39   604.5 1533.26   633.9 1534.39   655.6 1537.54
   863.7 1536.69  1054.9 1542.46  1166.4 1542.74  1341.1 1539.61  1549.4 1541.25
#Mann= 11 ,-1 , 0
       0    .035       0     130     .04       0     230     .06       0
  486.09    .045       0   533.2     .06       0  663.87     .08       0
  823.58      .1       0  873.58     .08       0 1070.94     .06       0
 1170.94     .08       0 1470.94     .06       0
#XS Ineff= 2 , 0
             482 1537.31  536.68         1537.45
Permanent Ineff=
       F       F
Bank Sta=486.09,533.2
XS Rating Curve= 0 ,0
Exp/Cntr=0.5,0.3

Type RM Length L Ch R = 1 ,128     ,150.8,161.2,171.5
XS GIS Cut Line= 6
     2064421.268      253459.819     2064336.632      253748.448
     2064521.094      254008.864     2064597.049      254271.451
      2064610.07      254373.448     2064634.238      254888.508
#Sta/Elev= 30
       0 1607.03    42.3 1596.04    62.8 1587.08   103.8 1588.59   114.1 1582.45
   172.2 1561.81   192.9 1549.54   206.4 1537.62   257.7 1537.21   278.2 1530.94
   302.2 1512.85   358.6  1508.3   421.2 1508.65   447.1 1515.27   478.7 1516.38
   500.7 1515.79  510.17 1510.95   518.7 1508.19   539.6 1508.23   543.6  1510.9
   549.3 1517.81   558.7 1521.47   619.9 1527.89   744.4 1523.07   996.2 1524.75
  1099.5 1522.99  1366.9 1527.75  1399.7  1531.2  1442.4 1528.71  1511.7 1530.77
#Mann= 13 ,-1 , 0
       0      .1       0     100     .04       0     200     .06       0
     240    .025       0  340.78      .1       0  420.78    .025       0
  510.17    .045       0   543.6     .06       0  659.91    .025       0
  729.91     .08       0  859.91    .025       0 1056.09     .06       0
 1456.09    .025       0
#XS Ineff= 2 , 0
           498.9 1533.62  546.18         1533.59
Permanent Ineff=
       F       F
Bank Sta=510.17,543.6
XS Rating Curve= 0 ,0
Exp/Cntr=0.5,0.3
LCMann Table=0

Chan Stop Cuts=-1
Use User Specified Reach Order=0
Composite Channel Slope=5